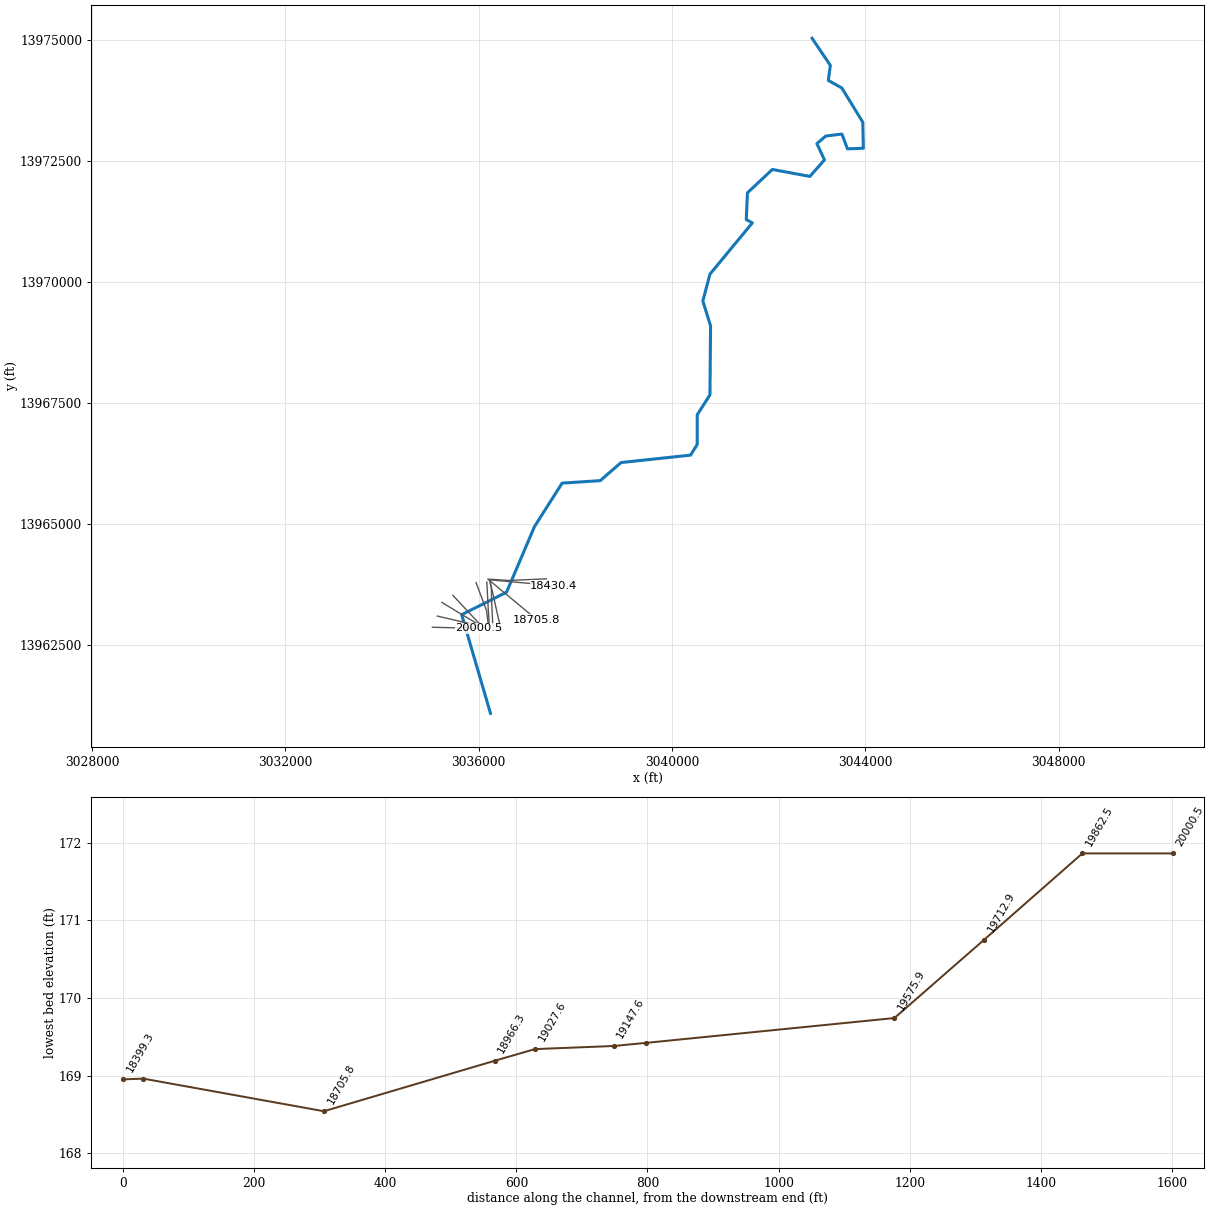
--- J131-00-00.PRJ (project) ---

Proj Title=J131-00-00
Current Plan=p02
Default Exp/Contr=.3,.1
English Units
Geom File=g01
Flow File=f01
Flow File=f02
Plan File=p01
Plan File=p02
Y Axis Title=Elevation
X Axis Title(PF)=Main Channel Distance
X Axis Title(XS)=Station
BEGIN DESCRIPTION:
Spring Creek
Boggs Gully
HCFCD Unit J131-00-00
Flood Hazard Model
10, 2, 1, 0.2% Event
Filename J131-00-00.prj
Prepared by: Halff Associates, Inc.        Date: 03/24/2004
Reviewed by:                  Date:
STATUS Final RAS
END DESCRIPTION:
DSS Export Rating Curves= 0
DSS Export Rating Curve Sorted= 0
DSS Export Volume Flow Curves= 0
DXF OffsetX= 0
DXF OffsetY= 0
DXF ScaleX= 1
DXF ScaleY= 10

--- J131-00-00.p02 (plan) ---

Plan Title=Floodway
Version=Version 3.0.1  Mar 2001
Short Identifier=Floodway0607
Geom File=g01
Flow File=f02
Subcritical Flow
K Sum by GR= 0
Std Step Tol= 0.01
Critical Tol= 0.01
Num of Std Step Trials= 20
Max Error Tol= 0.3
Flow Tol Ratio= 0.001
Split Flow NTrial= 30
Split Flow Tol= 0.02
Split Flow Ratio= 0.02
Log Output Level= 0
Friction Slope Method= 1
Unsteady Friction Slope Method= 2
Parabolic Critical Depth
Global Vel Dist= 0 , 0 , 0
Global Log Level= 0
CheckData=True
Encroach Param=-1 ,0,0, 2
Encroach River=J131-00-00
Encroach Reach=Reach - 1
Encroach Node=20000.5
       1  4962.3  5043.4
Encroach Node=19862.5
       1  4962.3  5043.4
Encroach Node=19712.9
       1  4956.5  5045.5
Encroach Node=19575.9
       1  4956.5  5045.5
Encroach Node=19196.8
       1  4956.5  5045.5
Encroach Node=19147.6
       1  4964.7  5037.4
Encroach Node=19087.6
       1  4964.7  5037.4
Encroach Node=19027.6
       1  4964.7  5037.4
Encroach Node=18966.3
       1  4945.2  5044.1
Encroach Node=18705.8
       1  4945.2  5044.1
Encroach Node=18430.4
       1  4969.2  5035.9
Encroach Node=18399.3
       1  4969.2  5042.9
Encroach Node=18310.3
       1  4969.2  5042.9
Encroach Node=18221.3
       1  4969.2  5042.9
Encroach Node=18198.5
       1 4956.39 5040.09
Encroach Node=17823.9
       1    4949  5049.7
Encroach Node=17543.0
       1  4958.6  5032.2
Encroach Node=17295.4
       1  4958.6  5032.2
Encroach Node=16949.6
       1  4958.6  5032.2
Encroach Node=16925.6
       1    4972    5033
Encroach Node=16852.6
       1    4972    5033
Encroach Node=16779.6
       1    4972    5033
Encroach Node=16747.1
       1 4961.31  5033.4
Encroach Node=16580.5
       1 4960.38  5033.4
Encroach Node=16467.4
       14292.7144359.052
Encroach Node=16451.4
       14292.7144359.052
Encroach Node=16435.4
       14292.7144359.052
Encroach Node=16345.1
       1 4967.88 5062.13
Encroach Node=16177.0
       1 4966.12 5062.95
Encroach Node=15744.7
       1  4953.5 5048.89
Encroach Node=15677.2
       1  4953.5 5049.71
Encroach Node=15644.2
       1  4953.5 5049.71
Encroach Node=15611.2
       1  4953.5 5049.71
Encroach Node=15555.0
       1  4942.2 5040.68
Encroach Node=15290.4
       1 4941.73 5042.09
Encroach Node=15017.6
       1  4957.7  5051.6
Encroach Node=14712.7
       1  4957.7  5051.6
Encroach Node=14383.2
       1  4942.3    5044
Encroach Node=14092.8
       1  4942.3    5044
Encroach Node=13925.1
       1  4942.3    5044
Encroach Node=13666.7
       1 4941.76 5022.16
Encroach Node=13656.2
       1 4941.76 5022.16
Encroach Node=13645.7
       1 4941.76 5022.16
Encroach Node=13609.5
       1  4959.2 5034.23
Encroach Node=13349.2
       1  4934.2  5029.6
Encroach Node=13180.3
       1  4934.2  5029.6
Encroach Node=12963.7
       1  4934.2  5029.6
Encroach Node=12758.0
       1  4934.2  5029.6
Encroach Node=12015.9
       1  4934.2  5029.6
Encroach Node=11219.5
       1  4944.2  5044.9
Encroach Node=10822.9
       1  4944.2  5044.9
Encroach Node=10643.0
       1  4942.5  5054.2
Encroach Node=10614.0
       1  4942.5  5054.2
Encroach Node=10585.0
       1  4942.5  5054.2
Encroach Node=10430.7
       1  4977.7  5065.9
Encroach Node=9942.3
       1  4977.7  5065.9
Encroach Node=9502.6
       1  4968.7  5054.5
Encroach Node=9063.9
       1    4950    5035
Encroach Node=8780.6
       1    4970    5045
Encroach Node=8516.4
       1 4956.38    5030
Encroach Node=8237.7
       1    4965    5043
Encroach Node=7916.6
       1    4972    5045
Encroach Node=7252.7
       1    4965    5045
Encroach Node=6908.5
       1    4930    5040
Encroach Node=6559.8
       1    4982    5050
Encroach Node=6351.7
       1    4954    5065
Encroach Node=6154.9
       1    4948    5070
Encroach Node=5866.2
       1    4950    5040
Encroach Node=5557.5
       1    4955    5032
Encroach Node=5302.3
       1    4935    5040
Encroach Node=5170.9
       1  4933.7  5064.9
Encroach Node=5153.4
       1  4933.7  5064.9
Encroach Node=5135.9
       1  4933.7  5064.9
Encroach Node=5039.4
       1    4940    5045
Encroach Node=4849.0
       1    4930    5075
Encroach Node=4606.7
       1    4865    5030
Encroach Node=4157.4
       1    4966    5041
Encroach Node=3894.0
       1    4966    5030
Encroach Node=3630.2
       1    4970    5120
Encroach Node=3310.1
       1    4959  5043.5
Encroach Node=3151.5
       1    4947  5043.5
Encroach Node=2912.5
       1    4912    5027
Encroach Node=2857.6
       1    4950    5035
Encroach Node=2829.6
       1    4970    5035
Encroach Node=2801.6
       1    4970    5035
Encroach Node=2663.1
       1    4933    5020
Encroach Node=2446.1
       1  4977.8    5050
Encroach Node=2201.0
       1    4973    5031
Encroach Node=1912.1
       1  4970.7    5045
Encroach Node=1513.6
       1  4970.7    5055
Encroach Node=913.5
       1    4945    5050
Encroach Node=307.3
       1    4935    5050
Encroach Reach=J131-00-00_0003
Encroach Node=20000.5
       1  4962.3  5043.4
Encroach Node=19862.5
       1  4962.3  5043.4
Encroach Node=19712.9
       1  4956.5  5045.5
Encroach Node=19575.9
       1  4956.5  5045.5
Encroach Node=19196.8
       1  4956.5  5045.5
Encroach Node=19147.6
       1  4964.7  5037.4
Encroach Node=19087.6
       1  4964.7  5037.4
Encroach Node=19027.6
       1  4964.7  5037.4
Encroach Node=18966.3
       1  4945.2  5044.1
Encroach Node=18705.8
       1  4945.2  5044.1
Encroach Node=18430.4
       1  4969.2  5035.9
Encroach Node=18399.3
       1  4969.2  5042.9
Encroach Node=18310.3
       1  4969.2  5042.9
Encroach Node=18221.3
       1  4969.2  5042.9
Encroach Node=18198.5
       1 4956.39 5040.09
Encroach Node=17823.9
       1    4949  5049.7
Encroach Node=17543.0
       1  4958.6  5032.2
Encroach Node=17295.4
       1  4958.6  5032.2
Encroach Node=16949.6
       1  4958.6  5032.2
Encroach Node=16925.6
       1    4972    5033
Encroach Node=16852.6
       1    4972    5033
Encroach Node=16779.6
       1    4972    5033
Encroach Node=16747.1
       1 4961.31  5033.4
Encroach Node=16580.5
       1 4960.38  5033.4
Encroach Node=16467.4
       14292.7144359.052
Encroach Node=16451.4
       14292.7144359.052
Encroach Node=16435.4
       14292.7144359.052
Encroach Node=16345.1
       1 4967.88 5062.13
Encroach Node=16177.0
       1 4966.12 5062.95
Encroach Node=15744.7
       1  4953.5 5048.89
Encroach Node=15677.2
       1  4953.5 5049.71
Encroach Node=15644.2
       1  4953.5 5049.71
Encroach Node=15611.2
       1  4953.5 5049.71
Encroach Node=15555.0
       1  4942.2 5040.68
Encroach Node=15290.4
       1 4941.73 5042.09
Encroach Node=15017.6
       1  4957.7  5051.6
Encroach Node=14712.7
       1  4957.7  5051.6
Encroach Node=14383.2
       1  4942.3    5044
Encroach Node=14092.8
       1  4942.3    5044
Encroach Node=13925.1
       1  4942.3    5044
Encroach Node=13666.7
       1 4941.76 5022.16
Encroach Node=13656.2
       1 4941.76 5022.16
Encroach Node=13645.7
       1 4941.76 5022.16
Encroach Node=13609.5
       1  4959.2 5034.23
Encroach Node=13349.2
       1  4934.2  5029.6
Encroach Node=13180.3
       1  4934.2  5029.6
Encroach Node=12963.7
       1  4934.2  5029.6
Encroach Node=12758.0
       1  4934.2  5029.6
Encroach Node=12015.9
       1  4934.2  5029.6
Encroach Node=11219.5
       1  4944.2  5044.9
Encroach Node=10822.9
       1  4944.2  5044.9
Encroach Node=10643.0
       1  4942.5  5054.2
Encroach Node=10614.0
       1  4942.5  5054.2
Encroach Node=10585.0
       1  4942.5  5054.2
Encroach Node=10430.7
       1  4977.7  5065.9
Encroach Node=9942.3
       1  4977.7  5065.9
Encroach Node=9502.6
       1  4968.7  5054.5
Encroach Node=9063.9
       1    4950    5035
Encroach Node=8780.6
       1    4970    5045
Encroach Node=8516.4
       1 4956.38    5030
Encroach Node=8237.7
       1    4965    5043
Encroach Node=7916.6
       1    4972    5045
Encroach Node=7252.7
       1    4965    5045
Encroach Node=6908.5
       1    4930    5040
Encroach Node=6559.8
       1    4982    5050
Encroach Node=6351.7
       1    4954    5065
Encroach Node=6154.9
       1    4948    5070
Encroach Node=5866.2
       1    4950    5040
Encroach Node=5557.5
       1    4955    5032
Encroach Node=5302.3
       1    4935    5040
Encroach Node=5170.9
       1  4933.7  5064.9
Encroach Node=5153.4
       1  4933.7  5064.9
Encroach Node=5135.9
       1  4933.7  5064.9
Encroach Node=5039.4
       1    4940    5045
Encroach Node=4849.0
       1    4930    5075
Encroach Node=4606.7
       1    4865    5030
Encroach Node=4157.4
       1    4966    5041
Encroach Node=3894.0
       1    4966    5030
Encroach Node=3630.2
       1    4970    5120
Encroach Node=3310.1
       1    4959  5043.5
Encroach Node=3151.5
       1    4947  5043.5
Encroach Node=2912.5
       1    4912    5027
Encroach Node=2857.6
       1    4950    5035
Encroach Node=2829.6
       1    4970    5035
Encroach Node=2801.6
       1    4970    5035
Encroach Node=2663.1
       1    4933    5020
Encroach Node=2446.1
       1  4977.8    5050
Encroach Node=2201.0
       1    4973    5031
Encroach Node=1912.1
       1  4970.7    5045
Encroach Node=1513.6
       1  4970.7    5055
Encroach Node=913.5
       1    4945    5050
Encroach Node=307.3
       1    4935    5050
Computation Interval=1HOUR
Output Interval=1HOUR
Run HTab= 0
Run UNet= 0
Run PostProcess= 0
UNET Theta= 1
UNET ZTol= 0.02
UNET ZSATol= 0.1
UNET MxIter= 20
UNET MaxInSteps= 20
UNET DtIC= 0
UNET DtMin= 0
UNET MaxCRTS= 20
UNET WFStab= 2
UNET SFStab= 1
UNET WFX= 1
UNET SFX= 1
UNET Convert EG Bridges=-1
UNET Use Existing IB Tables=-1
Instantaneous Interval=1HOUR
Write IC File= 0
Write Velocity= 0
Write Detailed= 0

--- J131-00-00.p01 (plan) ---

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Plan Title=FEMA Effective June 2007
Short Identifier=FEMAeff0607
Geom File=g01
Flow File=f01
Encroach Param=-1 ,0,0, 0

--- J131-00-00.f02 (steady flow) ---

Flow Title=Floodway
Version=Version 3.0.1  Mar 2001
Number of Profiles= 2
Profile Names=1PCT_100yr, 1PCTFloodway_100yrFW
River Rch & RM=J131-00-00,J131-00-00_0003,20000.5
     360     360
River Rch & RM=J131-00-00,J131-00-00_0003,19862.5
     450     450
River Rch & RM=J131-00-00,J131-00-00_0003,19712.9
     550     550
River Rch & RM=J131-00-00,J131-00-00_0003,19575.9
     600     600
River Rch & RM=J131-00-00,J131-00-00_0003,19196.8
     640     640
River Rch & RM=J131-00-00,J131-00-00_0003,18966.3
     680     680
River Rch & RM=J131-00-00,J131-00-00_0003,18705.8
     730     730
River Rch & RM=J131-00-00,J131-00-00_0003,18430.4
     770     770
River Rch & RM=J131-00-00,J131-00-00_0003,18198.5
     840     840
River Rch & RM=J131-00-00,J131-00-00_0003,17823.9
     900     900
River Rch & RM=J131-00-00,J131-00-00_0003,17543.0
     950     950
River Rch & RM=J131-00-00,J131-00-00_0003,17295.4
    1040    1040
River Rch & RM=J131-00-00,J131-00-00_0003,16949.6
    1090    1090
River Rch & RM=J131-00-00,J131-00-00_0003,16747.1
    1130    1130
River Rch & RM=J131-00-00,J131-00-00_0003,16580.5
    1200    1200
River Rch & RM=J131-00-00,J131-00-00_0003,16345.1
    1250    1250
River Rch & RM=J131-00-00,J131-00-00_0003,16177.0
    1310    1310
River Rch & RM=J131-00-00,J131-00-00_0003,15744.7
    1350    1350
River Rch & RM=J131-00-00,J131-00-00_0003,15290.4
    1390    1390
River Rch & RM=J131-00-00,J131-00-00_0003,15017.6
    1420    1420
River Rch & RM=J131-00-00,J131-00-00_0003,14712.7
    1470    1470
River Rch & RM=J131-00-00,J131-00-00_0003,14383.2
    1500    1500
River Rch & RM=J131-00-00,J131-00-00_0003,14092.8
    1560    1560
River Rch & RM=J131-00-00,J131-00-00_0003,13925.1
    1610    1610
River Rch & RM=J131-00-00,J131-00-00_0003,13349.2
    1690    1690
River Rch & RM=J131-00-00,J131-00-00_0003,12758.0
    1810    1810
River Rch & RM=J131-00-00,J131-00-00_0003,12015.9
    1940    1940
River Rch & RM=J131-00-00,J131-00-00_0003,11219.5
    2010    2010
River Rch & RM=J131-00-00,J131-00-00_0003,10822.9
    2080    2080
River Rch & RM=J131-00-00,J131-00-00_0003,10430.7
    2170    2170
River Rch & RM=J131-00-00,J131-00-00_0003,9942.3
    2260    2260
River Rch & RM=J131-00-00,J131-00-00_0003,9502.6
    2350    2350
River Rch & RM=J131-00-00,J131-00-00_0003,9063.9
    2410    2410
River Rch & RM=J131-00-00,J131-00-00_0003,8780.6
    2530    2530
River Rch & RM=J131-00-00,J131-00-00_0003,8237.7
    2600    2600
River Rch & RM=J131-00-00,J131-00-00_0003,7252.7
    3000    3000
River Rch & RM=J131-00-00,J131-00-00_0003,5866.2
    3100    3100
River Rch & RM=J131-00-00,J131-00-00_0003,4606.7
    3210    3210
River Rch & RM=J131-00-00,J131-00-00_0003,3151.5
    3280    3280
River Rch & RM=J131-00-00,J131-00-00_0003,2201.0
    3441    3441
Boundary for River Rch & Prof#=J131-00-00,J131-00-00_0003, 1
Up Type= 0
Dn Type= 3
Dn Slope=.004
Boundary for River Rch & Prof#=J131-00-00,J131-00-00_0003, 2
Up Type= 0
Dn Type= 1
Dn Known WS=140.34
DSS Import GetInterval= 0
DSS Import GetPeak= 0
DSS Import FillOption= 0

--- J131-00-00.f01 (steady flow) ---

Flow Title=FEMA Effective June 2007
Version=Version 3.0.1  Mar 2001
Number of Profiles= 4
Profile Names=10PCT_10yr, 2PCT_50yr, 1PCT_100yr, 0.2PCT_500yr
River Rch & RM=J131-00-00,J131-00-00_0003,20000.5
     190     300     360     520
River Rch & RM=J131-00-00,J131-00-00_0003,19862.5
     240     380     450     660
River Rch & RM=J131-00-00,J131-00-00_0003,19712.9
     290     470     550     810
River Rch & RM=J131-00-00,J131-00-00_0003,19575.9
     320     510     600     890
River Rch & RM=J131-00-00,J131-00-00_0003,19196.8
     330     540     640     930
River Rch & RM=J131-00-00,J131-00-00_0003,18966.3
     360     580     680     990
River Rch & RM=J131-00-00,J131-00-00_0003,18705.8
     380     620     730    1060
River Rch & RM=J131-00-00,J131-00-00_0003,18430.4
     400     650     770    1120
River Rch & RM=J131-00-00,J131-00-00_0003,18198.5
     440     710     840    1220
River Rch & RM=J131-00-00,J131-00-00_0003,17823.9
     470     760     900    1310
River Rch & RM=J131-00-00,J131-00-00_0003,17543.0
     490     810     950    1380
River Rch & RM=J131-00-00,J131-00-00_0003,17295.4
     530     870    1040    1500
River Rch & RM=J131-00-00,J131-00-00_0003,16949.6
     560     920    1090    1570
River Rch & RM=J131-00-00,J131-00-00_0003,16747.1
     580     950    1130    1640
River Rch & RM=J131-00-00,J131-00-00_0003,16580.5
     620    1010    1200    1730
River Rch & RM=J131-00-00,J131-00-00_0003,16345.1
     640    1050    1250    1800
River Rch & RM=J131-00-00,J131-00-00_0003,16177.0
     670    1100    1310    1890
River Rch & RM=J131-00-00,J131-00-00_0003,15744.7
     700    1140    1350    1950
River Rch & RM=J131-00-00,J131-00-00_0003,15290.4
     710    1160    1390    2000
River Rch & RM=J131-00-00,J131-00-00_0003,15017.6
     740    1200    1420    2050
River Rch & RM=J131-00-00,J131-00-00_0003,14712.7
     760    1230    1470    2120
River Rch & RM=J131-00-00,J131-00-00_0003,14383.2
     780    1270    1500    2170
River Rch & RM=J131-00-00,J131-00-00_0003,14092.8
     810    1320    1560    2260
River Rch & RM=J131-00-00,J131-00-00_0003,13925.1
     840    1350    1610    2320
River Rch & RM=J131-00-00,J131-00-00_0003,13349.2
     880    1430    1690    2450
River Rch & RM=J131-00-00,J131-00-00_0003,12758.0
     950    1520    1810    2620
River Rch & RM=J131-00-00,J131-00-00_0003,12015.9
    1020    1640    1940    2820
River Rch & RM=J131-00-00,J131-00-00_0003,11219.5
    1060    1700    2010    2920
River Rch & RM=J131-00-00,J131-00-00_0003,10822.9
    1100    1760    2080    3030
River Rch & RM=J131-00-00,J131-00-00_0003,10430.7
    1160    1840    2170    3160
River Rch & RM=J131-00-00,J131-00-00_0003,9942.3
    1200    1910    2260    3290
River Rch & RM=J131-00-00,J131-00-00_0003,9502.6
    1260    1990    2350    3430
River Rch & RM=J131-00-00,J131-00-00_0003,9063.9
    1290    2040    2410    3510
River Rch & RM=J131-00-00,J131-00-00_0003,8780.6
    1360    2140    2530    3690
River Rch & RM=J131-00-00,J131-00-00_0003,8237.7
    1400    2200    2600    3800
River Rch & RM=J131-00-00,J131-00-00_0003,7252.7
    1650    2580    3000    4440
River Rch & RM=J131-00-00,J131-00-00_0003,5866.2
    1690    2650    3100    4560
River Rch & RM=J131-00-00,J131-00-00_0003,4606.7
    1750    2740    3210    4710
River Rch & RM=J131-00-00,J131-00-00_0003,3151.5
    1780    2800    3280    4820
River Rch & RM=J131-00-00,J131-00-00_0003,2201.0
    1860    2915    3441    5024
Boundary for River Rch & Prof#=J131-00-00,J131-00-00_0003, 1
Up Type= 0
Dn Type= 3
Dn Slope=.004
Boundary for River Rch & Prof#=J131-00-00,J131-00-00_0003, 2
Up Type= 0
Dn Type= 3
Dn Slope=.004
Boundary for River Rch & Prof#=J131-00-00,J131-00-00_0003, 3
Up Type= 0
Dn Type= 3
Dn Slope=.004
Boundary for River Rch & Prof#=J131-00-00,J131-00-00_0003, 4
Up Type= 0
Dn Type= 3
Dn Slope=.004
DSS Import GetInterval= 0
DSS Import GetPeak= 0
DSS Import FillOption= 0

--- J131-00-00.g01 (geometry) ---

Geom Title=J131-00-00 June 2007
Version=Version 3.0.1  Mar 2001

River Reach=J131-00-00      ,J131-00-00_0003
Reach XY= 30
    3036242.9626   13961089.8569    3035646.5676   13963129.2589
    3036574.9675   13963593.4402    3037152.8947   13964948.9069
    3037724.5416   13965847.5611    3038512.7477    13965898.839
    3038943.8036   13966272.4341    3040382.0239     13966426.37
    3040518.5886    13966644.803    3040520.0826   13967260.5393
    3040782.8687    13967672.473    3040795.4178     13969096.75
    3040635.5376    13969610.691    3040782.8815   13970165.9499
    3041659.4557    13971225.456    3041533.7515   13971293.1209
    3041558.4796   13971846.7153    3042074.0938    13972329.157
    3042849.5848   13972185.0249    3043151.6674   13972526.0441
    3042995.1925   13972863.4951    3043179.5269   13973020.1179
    3043512.6074   13973060.4354    3043627.1915   13972754.8799
    3043956.0214   13972767.4121    3043944.0867   13973305.1192
    3043510.8185    13974012.311    3043231.5225   13974168.6712
    3043273.2966    13974479.597    3042895.8548   13975038.2499

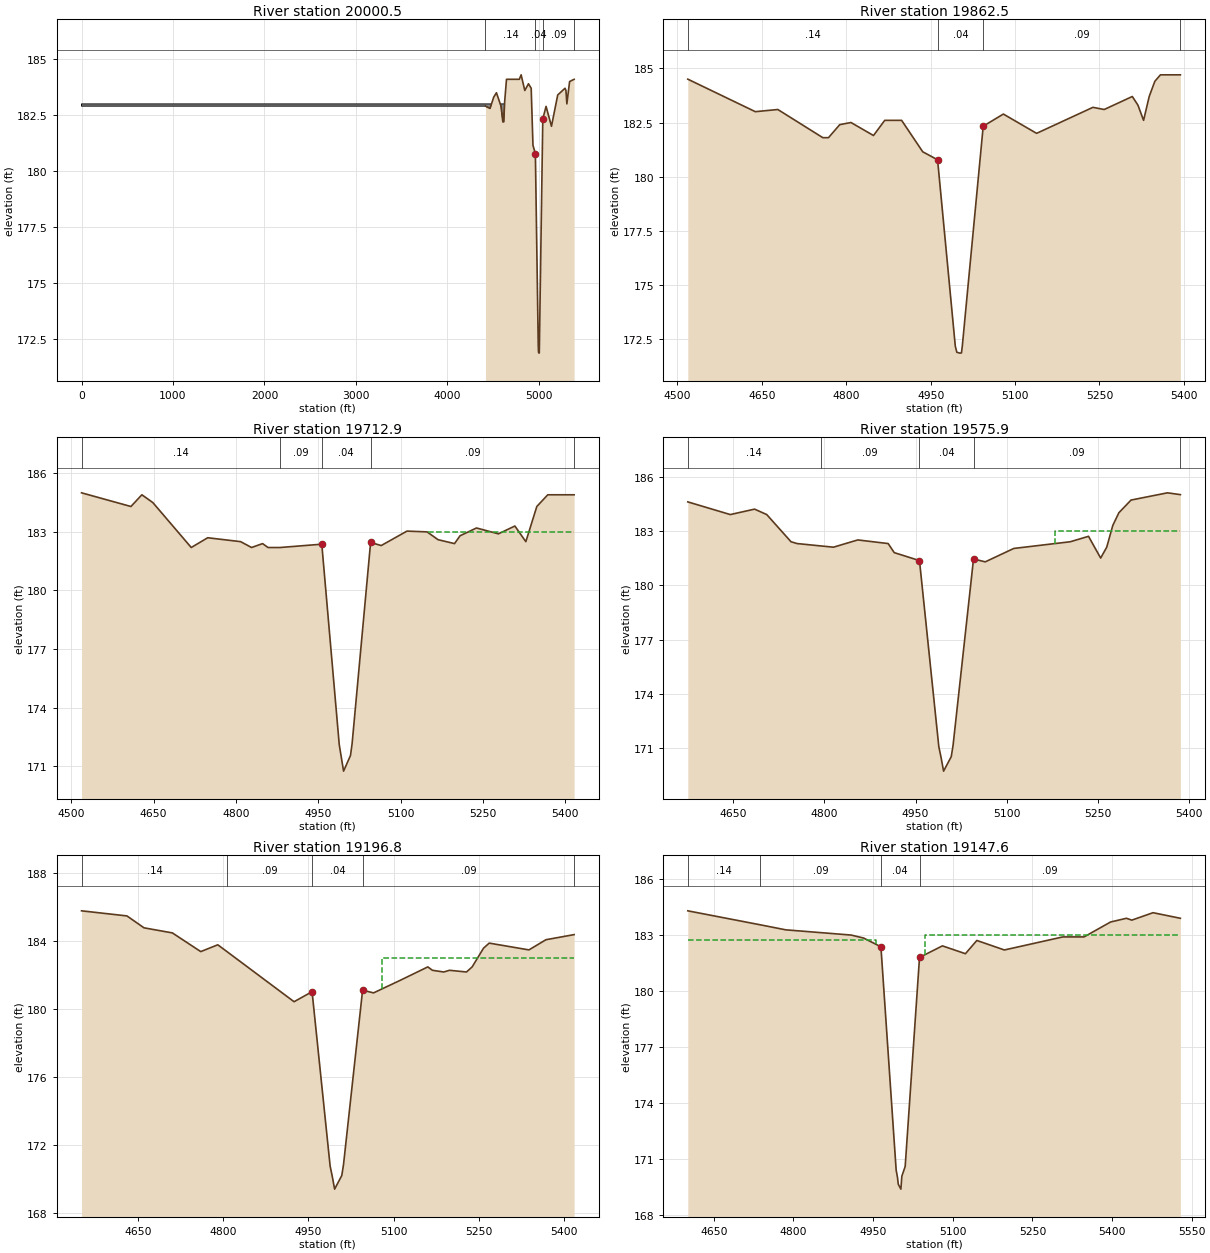
Type RM Length L Ch R = 1 ,20000.5 ,148.77,138,129.53
BEGIN DESCRIPTION:
Cross Section XS62
END DESCRIPTION:
XS GIS Cut Line= 2
    3035041.2341   13962869.6398    3036010.1629   13962844.5616
#Sta/Elev= 30
  4416.5   182.9  4466.5   182.8  4506.5   183.3  4536.5   183.5  4586.5   182.9
  4606.5   182.2  4616.5   182.2  4626.5   183.1  4646.5   184.1  4786.5   184.1
  4806.5   184.3  4846.5   183.6  4886.5   183.9  4916.5   183.7  4935.9  181.15
  4962.3  180.78  4993.8  172.18  4996.5   171.9  5002.1  171.86  5004.7  171.87
  5006.2  172.17  5043.4  182.33  5079.2  182.89  5138.3     182  5206.5   183.4
  5286.5   183.7  5296.5   183.6  5306.5     183  5336.5     184  5385.8   184.1
#Mann= 4 ,-1 , 0
  4416.5     .14       0  4962.3     .04       0  5043.4     .09       0
  5385.8      .2       0
#Block Obstruct= 2 , 0
       0    4630     183               0
Bank Sta=4962.3,5043.4
XS Rating Curve= 0
Exp/Cntr=.3,.1

Type RM Length L Ch R = 1 ,19862.5 ,166.44,149.6,132
BEGIN DESCRIPTION:
Cross Section XS61
END DESCRIPTION:
XS GIS Cut Line= 2
    3035143.8266   13963099.9028    3035996.4839   13962901.5574
#Sta/Elev= 29
  4518.4   184.5  4638.4     183  4678.4   183.1  4758.4   181.8  4768.4   181.8
  4788.4   182.4  4808.4   182.5  4848.4   181.9  4868.4   182.6  4898.4   182.6
  4935.9  181.15  4962.3  180.78  4993.8  172.18  4996.5   171.9  5002.1  171.86
  5004.7  171.87  5006.2  172.17  5043.4  182.33  5079.2  182.89  5138.3     182
  5238.4   183.2  5258.4   183.1  5308.4   183.7  5318.4   183.3  5328.4   182.6
  5338.4   183.7  5348.4   184.4  5358.4   184.7  5393.8   184.7
#Mann= 4 ,-1 , 0
  4518.4     .14       0  4962.3     .04       0  5043.4     .09       0
  5393.8      .2       0
#XS Ineff= 2 , 0
       0                    5300       0   183.5
Permanent Ineff=
       F       F
Bank Sta=4962.3,5043.4
XS Rating Curve= 0
Exp/Cntr=.3,.1

Type RM Length L Ch R = 1 ,19712.9 ,154.81,137,119.94
BEGIN DESCRIPTION:
Cross Section XS60.5
END DESCRIPTION:
XS GIS Cut Line= 2
    3035237.6797   13963382.2221    3036006.7431   13962918.6562
#Sta/Elev= 30
  4518.5     185  4608.5   184.3  4628.5   184.9  4648.5   184.5  4718.5   182.2
  4748.5   182.7  4808.5   182.5  4828.5   182.2  4848.5   182.4  4858.5   182.2
  4880.4   182.2  4956.5  182.37  4988.3  172.11  4996.2  170.75  5008.8  171.55
  5011.8  172.17  5045.5  182.46  5064.8   182.3  5111.8  183.04  5148.5     183
  5168.5   182.6  5198.5   182.4  5208.5   182.8  5238.5   183.2  5278.5   182.9
  5308.5   183.3  5328.5   182.5  5348.5   184.3  5368.5   184.9  5416.5   184.9
#Mann= 5 ,-1 , 0
  4518.5     .14       0  4880.4     .09       0  4956.5     .04       0
  5045.5     .09       0  5416.5      .2       0
#XS Ineff= 2 , 0
       0                    5150       0     183
Permanent Ineff=
       F       F
Bank Sta=4956.5,5045.5
XS Rating Curve= 0
Exp/Cntr=.3,.1

Type RM Length L Ch R = 1 ,19575.9 ,401.03,379.1,359.15
BEGIN DESCRIPTION:
Cross Section XS60
END DESCRIPTION:
XS GIS Cut Line= 2
    3035466.1865   13963527.5037    3036020.0619   13962934.6622
#Sta/Elev= 30
  4574.9   184.6  4644.9   183.9  4684.9   184.2  4704.9   183.9  4744.9   182.4
  4754.9   182.3  4793.5  182.17  4814.9   182.1  4830.8  182.26  4854.9   182.5
  4904.9   182.3  4914.9   181.8  4956.5  181.36  4988.3   171.1  4992.3  170.45
  4996.2  169.74  5008.8  170.54  5011.8  171.16  5045.5  181.45  5064.8  181.29
  5111.8  182.03  5204.9   182.4  5234.9   182.7  5254.9   181.5  5264.9   182.1
  5274.9   183.3  5284.9     184  5304.9   184.7  5364.9   185.1  5386.2     185
#Mann= 5 ,-1 , 0
  4574.9     .14       0  4793.5     .09       0  4956.5     .04       0
  5045.5     .09       0  5386.2      .2       0
#XS Ineff= 2 , 0
       0                    5180       0     183
Permanent Ineff=
       F       F
Bank Sta=4956.5,5045.5
XS Rating Curve= 0
Exp/Cntr=.3,.1

Type RM Length L Ch R = 1 ,19196.8 ,51.7,49.2,46.6
BEGIN DESCRIPTION:
Cross Section XS59
END DESCRIPTION:
XS GIS Cut Line= 3
    3035944.5113   13963791.5908    3036162.0098   13963212.9915
    3036192.6261   13962965.2784
#Sta/Elev= 29
  4550.4   185.8  4630.4   185.5  4660.4   184.8  4710.4   184.5  4760.4   183.4
  4790.4   183.8    4807  183.39  4822.6     183  4924.8  180.45  4956.5  181.04
  4988.3  170.78  4992.3  170.13  4996.2  169.42  5008.8  170.22  5011.8  170.84
  5045.5  181.13  5064.8  180.97  5111.8  181.71  5160.4   182.5  5168.5   182.3
  5188.5   182.2  5198.5   182.3  5228.5   182.2  5238.5   182.5  5258.5   183.6
  5268.5   183.9  5338.5   183.5  5368.5   184.1  5418.1   184.4
#Mann= 5 ,-1 , 0
  4550.4     .14       0    4807     .09       0  4956.5     .04       0
  5045.5     .09       0  5418.1      .2       0
#XS Ineff= 2 , 0
       0                    5080       0     183
Permanent Ineff=
       F       F
Bank Sta=4956.5,5045.5
XS Rating Curve= 0
Exp/Cntr=.5,.3

Type RM Length L Ch R = 1 ,19147.6 ,120,120,120
BEGIN DESCRIPTION:
Upstream Section of Bridge/Culvert/Weir
END DESCRIPTION:
XS GIS Cut Line= 3
    3036167.5764   13963803.0497    3036198.1927   13963207.4249
    3036222.4294   13962876.8289
#Sta/Elev= 24
  4600.9  184.31  4737.4  183.56  4785.5  183.29  4908.6  183.01  4932.1  182.85
  4964.7  182.38  4993.4   170.4  4995.9  170.01  4997.4  169.64  5002.3  169.38
  5004.1  170.07  5010.4   170.6  5037.4  181.81  5080.5  182.43  5123.9  182.01
  5145.4  182.72  5197.3  182.21  5307.3  182.91  5347.3  182.91  5397.3  183.71
  5427.3  183.91  5437.3  183.81  5477.3  184.21  5528.8  183.91
#Mann= 4 ,-1 , 0
  4600.9     .14       0  4737.4     .09       0  4964.7     .04       0
  5037.4     .09       0
#XS Ineff= 2 , 0
       0  4954.7  182.72  5047.4       0     183
Permanent Ineff=
       F       F
Bank Sta=4964.7,5037.4
XS Rating Curve= 0
Exp/Cntr=.5,.3

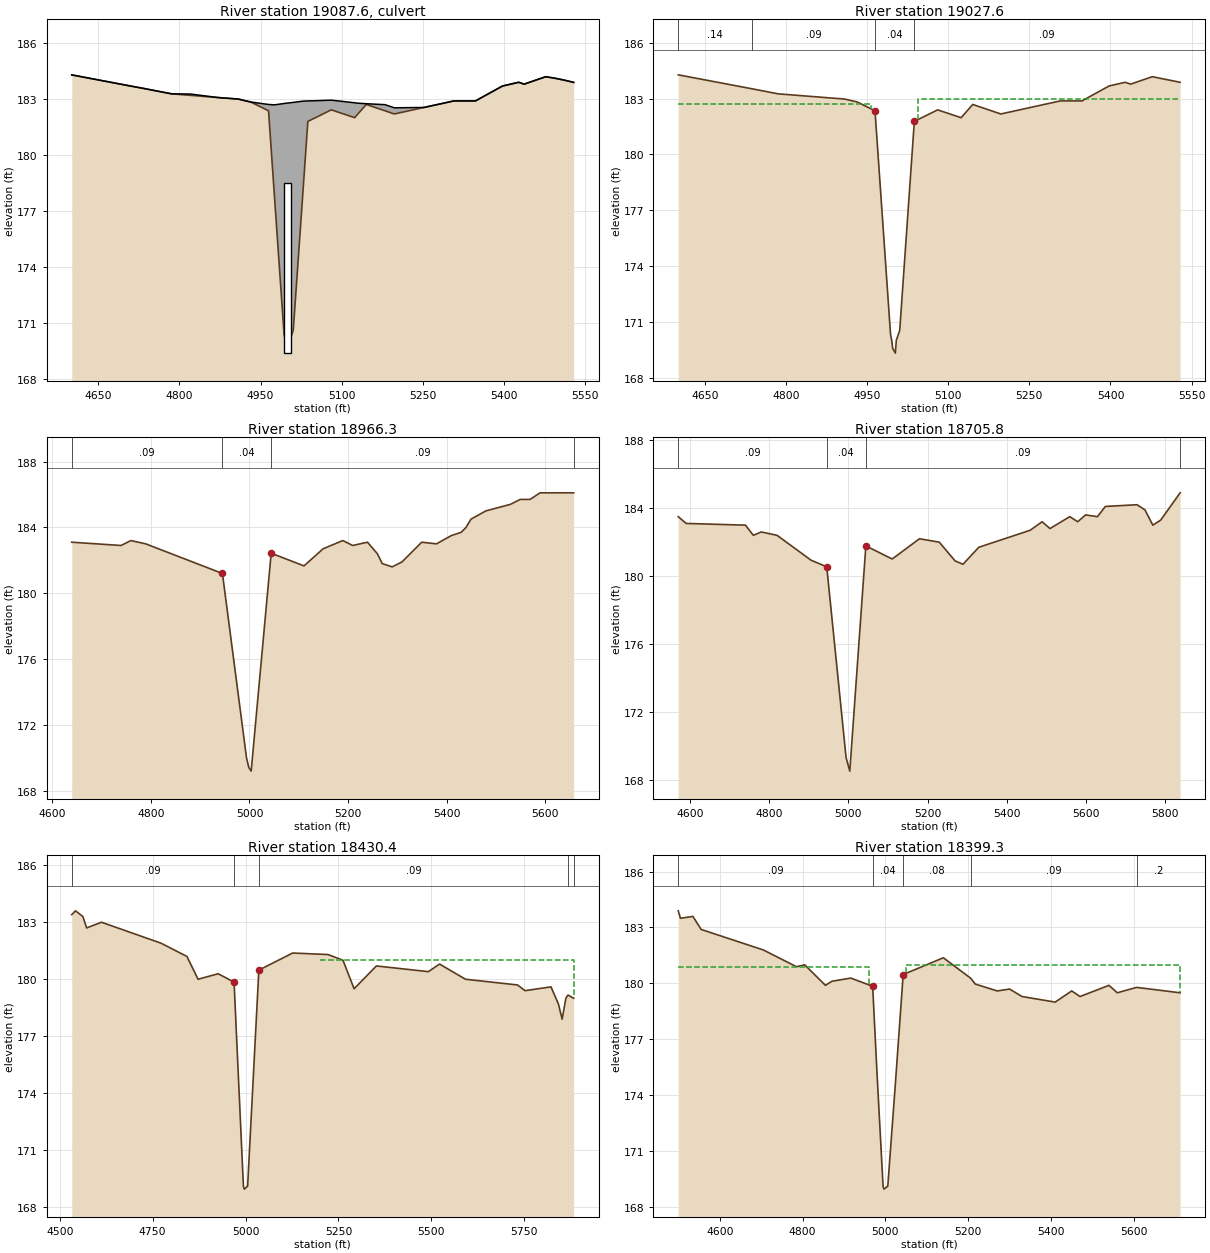
Type RM Length L Ch R = 2 ,19087.6 ,,,
BEGIN DESCRIPTION:
BAKER
Structure ID: J131-00-00-08
END DESCRIPTION:
Bridge Culvert--1,0,-1,-1, 0
Deck Dist Width WeirC Skew NumUp NumDn MinLoCord MaxHiCord MaxSubmerge Is_Ogee
10,100,3,0, 48, 48, , , .95, 0, 1,1,,
  4600.9  4605.7  4705.7  4737.4  4765.7  4785.5    4820  4871.7  4908.6  4923.1
  4932.1  4964.7  4974.5  4978.4 4992.79  4992.9 4993.01  4993.4  4995.9  4997.4
  5002.3  5004.1  5010.4  5023.5  5029.4  5037.4 5049.99  5050.1 5050.21  5080.5
    5081  5123.9  5129.3  5145.4    5180  5197.3  5252.2  5282.2  5307.3  5347.3
  5382.2  5397.3  5427.3  5437.3  5477.3  5497.2  5512.2  5528.8
   184.3  184.28  183.73  183.56   183.4  183.29  183.28  183.09  183.01  182.91
  182.85  182.72   182.7  182.71  182.77  182.77  182.77  182.77  182.78  182.79
   182.8  182.81  182.83  182.88   182.9  182.91  182.92  182.92  182.92  182.95
  182.95  182.81  182.79  182.76  182.71  182.54  182.56  182.75  182.91  182.91
  183.47  183.71  183.91  183.81  184.21  184.11  184.02   183.9
   184.3  184.27  183.72  183.55  183.39  183.28   183.2  183.08     183   182.9
  182.84  182.37  178.26  176.63  170.64   170.6  170.55  170.39     170  169.63
  169.37  170.06  170.59  176.02  178.47   181.8  181.98  181.98  181.98  182.42
  182.42     182  182.18  182.71  182.37   182.2  182.55  182.74   182.9   182.9
  183.46   183.7   183.9   183.8   184.2   184.1  184.01   183.9
  4600.9  4605.7  4705.7  4737.4  4765.7  4785.5    4820  4871.7  4908.6  4923.1
  4932.1  4964.7  4974.5  4978.4 4992.79  4992.9 4993.01  4993.4  4995.9  4997.4
  5002.3  5004.1  5010.4  5023.5  5029.4  5037.4 5049.99  5050.1 5050.21  5080.5
    5081  5123.9  5129.3  5145.4    5180  5197.3  5252.2  5282.2  5307.3  5347.3
  5382.2  5397.3  5427.3  5437.3  5477.3  5497.2  5512.2  5528.8
   184.3  184.28  183.73  183.56   183.4  183.29  183.28  183.09  183.01  182.91
  182.85  182.72   182.7  182.71  182.77  182.77  182.77  182.77  182.78  182.79
   182.8  182.81  182.83  182.88   182.9  182.91  182.92  182.92  182.92  182.95
  182.95  182.81  182.79  182.76  182.71  182.54  182.56  182.75  182.91  182.91
  183.47  183.71  183.91  183.81  184.21  184.11  184.02   183.9
   184.3  184.27  183.72  183.55  183.39  183.28   183.2  183.08     183   182.9
  182.84  182.37  178.26  176.63  170.64   170.6  170.55  170.39     170  169.63
  169.37  170.06  170.59  176.02  178.47   181.8  181.98  181.98  181.98  182.42
  182.42     182  182.18  182.71  182.37   182.2  182.55  182.74   182.9   182.9
  183.46   183.7   183.9   183.8   184.2   184.1  184.01   183.9
BR Coef= 1 , 0 , 0 ,1.25, 0 ,,,.8,-1,2,0,
WSPro=,,,, 1 ,,,, 0 ,,,, 0 ,,,,-1 ,-1 ,-1 , 0 , 0 , 0 , 0 , 0
Culvert=2,9.1,12.3,100,.015,.4,1,8,1,169.41,5000,169.15,5000,Culvert #1  , 0 ,10
Culvert Bottom n=.015
BR U #Sta/Elev= 48
  4600.9  184.31  4605.7  184.28  4705.7  183.73  4737.4  183.56  4765.7   183.4
  4785.5  183.29    4820  183.21  4871.7  183.09  4908.6  183.01  4923.1  182.91
  4932.1  182.85  4964.7  182.38  4974.5  178.27  4978.4  176.64 4992.79  170.65
  4992.9  170.61 4993.01  170.56  4993.4   170.4  4995.9  170.01  4997.4  169.64
  5002.3  169.38  5004.1  170.07  5010.4   170.6  5023.5  176.03  5029.4  178.48
  5037.4  181.81 5049.99  181.99  5050.1  181.99 5050.21  181.99  5080.5  182.43
    5081  182.43  5123.9  182.01  5129.3  182.19  5145.4  182.72    5180  182.38
  5197.3  182.21  5252.2  182.56  5282.2  182.75  5307.3  182.91  5347.3  182.91
  5382.2  183.47  5397.3  183.71  5427.3  183.91  5437.3  183.81  5477.3  184.21
  5497.2  184.11  5512.2  184.02  5528.8  183.91
BR U #Mann= 4
  4600.9     .14  4737.4     .09  4964.7    .035  5037.4     .09
BR D #Sta/Elev= 48
  4600.9  184.27  4605.7  184.24  4705.7  183.69  4737.4  183.52  4765.7  183.36
  4785.5  183.25    4820  183.17  4871.7  183.05  4908.6  182.97  4923.1  182.87
  4932.1  182.81  4964.7  182.34  4974.5  178.23  4978.4   176.6 4992.79  170.61
  4992.9  170.57 4993.01  170.52  4993.4  170.36  4995.9  169.97  4997.4   169.6
  5002.3  169.34  5004.1  170.03  5010.4  170.56  5023.5  175.99  5029.4  178.44
  5037.4  181.77 5049.99  181.95  5050.1  181.95 5050.21  181.95  5080.5  182.39
    5081  182.39  5123.9  181.97  5129.3  182.15  5145.4  182.68    5180  182.34
  5197.3  182.17  5252.2  182.52  5282.2  182.71  5307.3  182.87  5347.3  182.87
  5382.2  183.43  5397.3  183.67  5427.3  183.87  5437.3  183.77  5477.3  184.17
  5497.2  184.07  5512.2  183.98  5528.8  183.87
BR D #Mann= 4
  4600.9     .14  4737.4     .09  4964.7    .035  5037.4     .09
BC Design=,, 0 ,, 0 ,,,,,,

Type RM Length L Ch R = 1 ,19027.6 ,61.3,61.3,61.3
BEGIN DESCRIPTION:
Downstream Section of Bridge/Culvert/Weir
END DESCRIPTION:
XS GIS Cut Line= 4
    3036226.7238   13963833.4145    3036260.8404   13963671.3608
    3036265.0296     13963438.46    3036290.2077   13962909.7205
#Sta/Elev= 24
  4600.9  184.27  4737.4  183.52  4785.5  183.25  4908.6  182.97  4932.1  182.81
  4964.7  182.34  4993.4  170.36  4995.9  169.97  4997.4   169.6  5002.3  169.34
  5004.1  170.03  5010.4  170.56  5037.4  181.77  5080.5  182.39  5123.9  181.97
  5145.4  182.68  5197.3  182.17  5307.3  182.87  5347.3  182.87  5397.3  183.67
  5427.3  183.87  5437.3  183.77  5477.3  184.17  5528.8  183.87
#Mann= 4 ,-1 , 0
  4600.9     .14       0  4737.4     .09       0  4964.7     .04       0
  5037.4     .09       0
#XS Ineff= 2 , 0
       0 4958.03  182.72 5044.07       0     183
Permanent Ineff=
       F       F
Bank Sta=4964.7,5037.4
XS Rating Curve= 0
Exp/Cntr=.5,.3

Type RM Length L Ch R = 1 ,18966.3 ,218.22,260.5,313.29
BEGIN DESCRIPTION:
Cross Section XS58
END DESCRIPTION:
XS GIS Cut Line= 2
    3036237.1588   13963808.6163    3036459.8222   13962814.9805
#Sta/Elev= 30
  4639.5   183.1  4739.5   182.9  4759.5   183.2  4789.5     183  4945.2   181.2
  4994.1  169.99  4998.6  169.42  5003.5  169.19  5044.1  182.43  5110.7  181.66
  5149.5   182.7  5189.5   183.2  5209.5   182.9  5239.5   183.1  5259.5   182.4
  5269.5   181.8  5289.5   181.6  5309.5   181.9  5349.5   183.1  5379.5     183
  5409.5   183.5  5429.5   183.7  5439.5     184  5449.5   184.5  5479.5     185
  5529.5   185.4  5549.5   185.7  5569.5   185.7  5589.5   186.1  5657.8   186.1
#Mann= 4 ,-1 , 0
  4639.5     .09       0  4945.2     .04       0  5044.1     .09       0
  5657.8      .2       0
Bank Sta=4945.2,5044.1
XS Rating Curve= 0
Exp/Cntr=.3,.1

Type RM Length L Ch R = 1 ,18705.8 ,236.84,275.4,313.11
BEGIN DESCRIPTION:
Cross Section XS57
END DESCRIPTION:
XS GIS Cut Line= 2
     3036220.459   13963839.2325     3037197.395   13963029.2941
#Sta/Elev= 30
  4569.7   183.5  4589.7   183.1  4739.7     183  4759.7   182.4  4779.7   182.6
  4819.7   182.4  4905.5  180.94  4945.2  180.55  4994.1  169.34  5003.5  168.54
  5044.1  181.78  5110.7  181.01  5179.7   182.2  5229.7     182  5269.7   180.9
  5289.7   180.7  5329.7   181.7  5459.7   182.7  5489.7   183.2  5509.7   182.8
  5559.7   183.5  5579.7   183.2  5599.7   183.6  5629.7   183.5  5649.7   184.1
  5729.7   184.2  5749.7   183.9  5769.7     183  5789.7   183.3  5838.7   184.9
#Mann= 4 ,-1 , 0
  4569.7     .09       0  4945.2     .04       0  5044.1     .09       0
  5838.7      .2       0
#Block Obstruct= 2 , 0
       0                    5230       0     181
Bank Sta=4945.2,5044.1
XS Rating Curve= 0
Exp/Cntr=.3,.1

Type RM Length L Ch R = 1 ,18430.4 ,31.1,31.1,31.1
BEGIN DESCRIPTION:
Cross Section XS56
END DESCRIPTION:
XS GIS Cut Line= 2
    3036207.9891   13963851.0969    3037553.6566   13963730.6841
#Sta/Elev= 30
  4532.3   183.4  4542.3   183.6  4562.3   183.3  4572.3   182.7  4612.3     183
  4772.3   181.9  4842.3   181.2  4872.3     180  4926.4  180.29  4969.2  179.85
  4994.4   169.1  4996.7  168.96  5005.7  169.12  5035.9  180.48  5126.9  181.38
  5222.3   181.3  5262.3     181  5292.3   179.5  5352.3   180.7  5492.3   180.4
  5522.3   180.8  5592.3     180  5732.3   179.7  5752.3   179.4  5822.3   179.6
  5842.3   178.7  5852.3   177.9  5862.3     179  5868.1  179.17  5883.3     179
#Mann= 5 ,-1 , 0
  4532.3     .09       0  4969.2     .04       0  5035.9     .09       0
  5868.1     .08       0  5883.3      .2       0
#XS Ineff= 2 , 0
       0                    5200       0     181
Permanent Ineff=
       F       F
Bank Sta=4969.2,5035.9
XS Rating Curve= 0
Exp/Cntr=.5,.3

Type RM Length L Ch R = 1 ,18399.3 ,178,178,178
BEGIN DESCRIPTION:
Upstream Section of Bridge/Culvert/Weir
END DESCRIPTION:
XS GIS Cut Line= 4
    3036188.2932   13963864.0699    3036626.7258   13963836.1673
    3036686.4074   13963838.7527    3037398.3975   13963869.5971
#Sta/Elev= 30
  4499.8  183.89  4505.2  183.49  4535.2  183.59  4555.2  182.89  4705.2  181.79
  4785.2  180.89  4805.2  180.99  4855.2  179.89    4871  180.11  4916.4  180.28
  4969.2  179.84    4980  175.06  4994.4  169.09  4996.7  168.95  5005.7  169.11
  5024.3  174.68  5042.9  180.47  5139.9  181.37    5206  180.27  5216.8  179.96
  5269.8  179.59  5299.8  179.69  5329.8  179.29  5409.8  178.99  5449.8  179.59
  5469.8  179.29  5539.8  179.89  5559.8  179.49  5606.5  179.78  5711.5  179.49
#Mann= 5 ,-1 , 0
  4499.8     .09       0  4969.2     .04       0  5042.9     .08       0
    5206     .09       0  5606.5      .2       0
#XS Ineff= 2 , 0
       0    4960  180.89    5050       0     181
Permanent Ineff=
       F       F
Bank Sta=4969.2,5042.9
XS Rating Curve= 0
Exp/Cntr=.5,.3