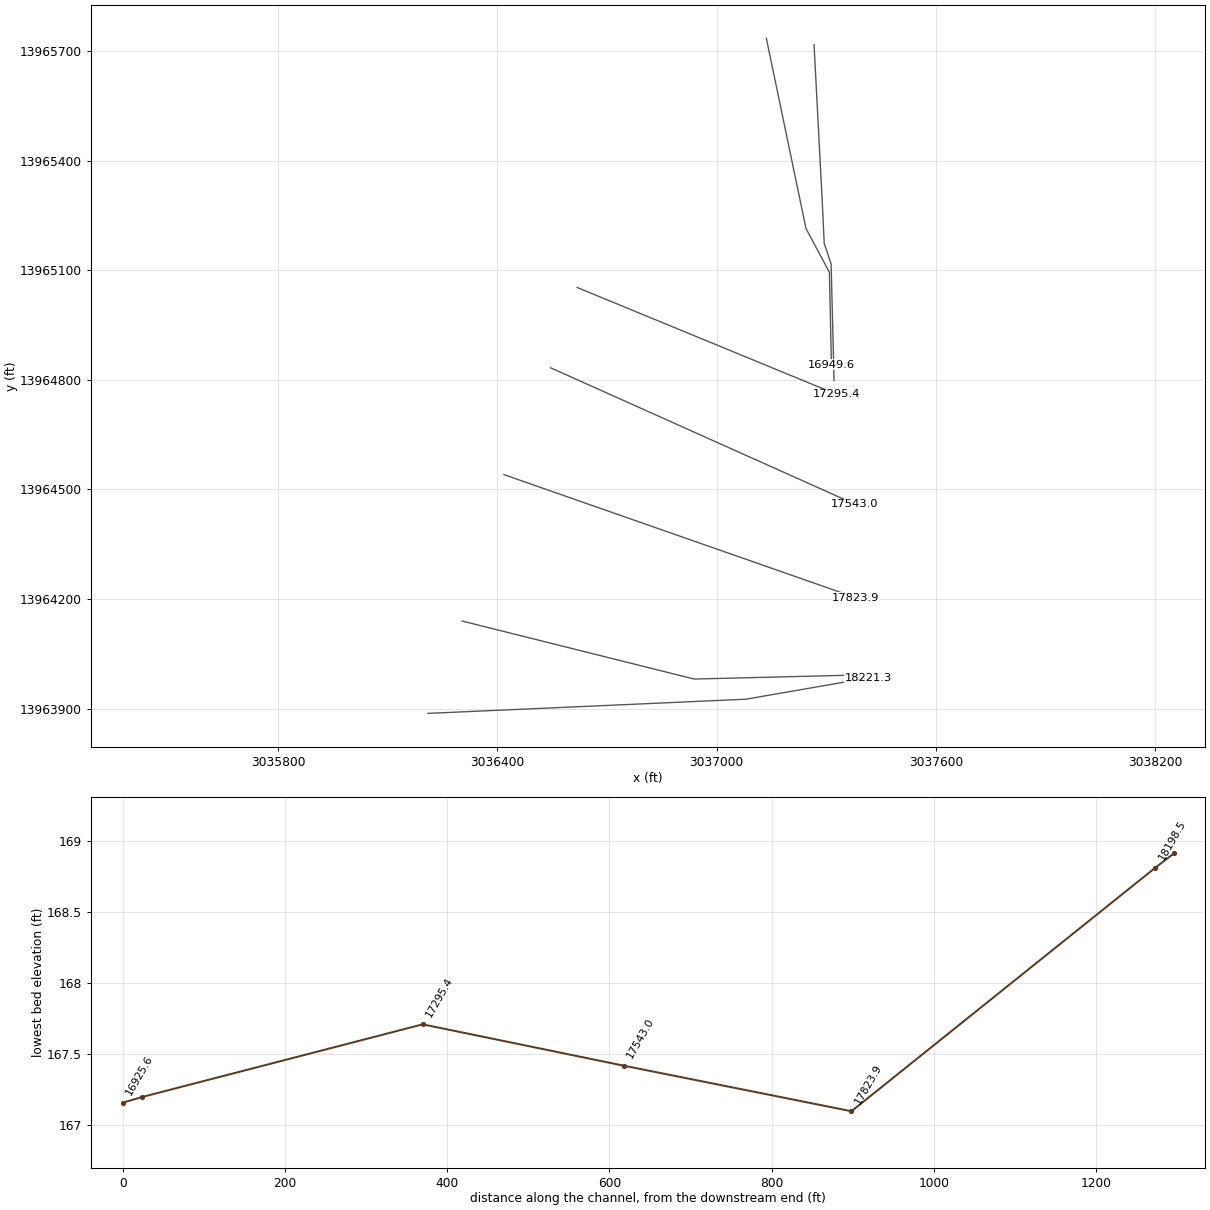
HEC-RAS study J131-00-00.PRJ: J131-00-00

--- J131-00-00.g01 (geometry) --- (continued)

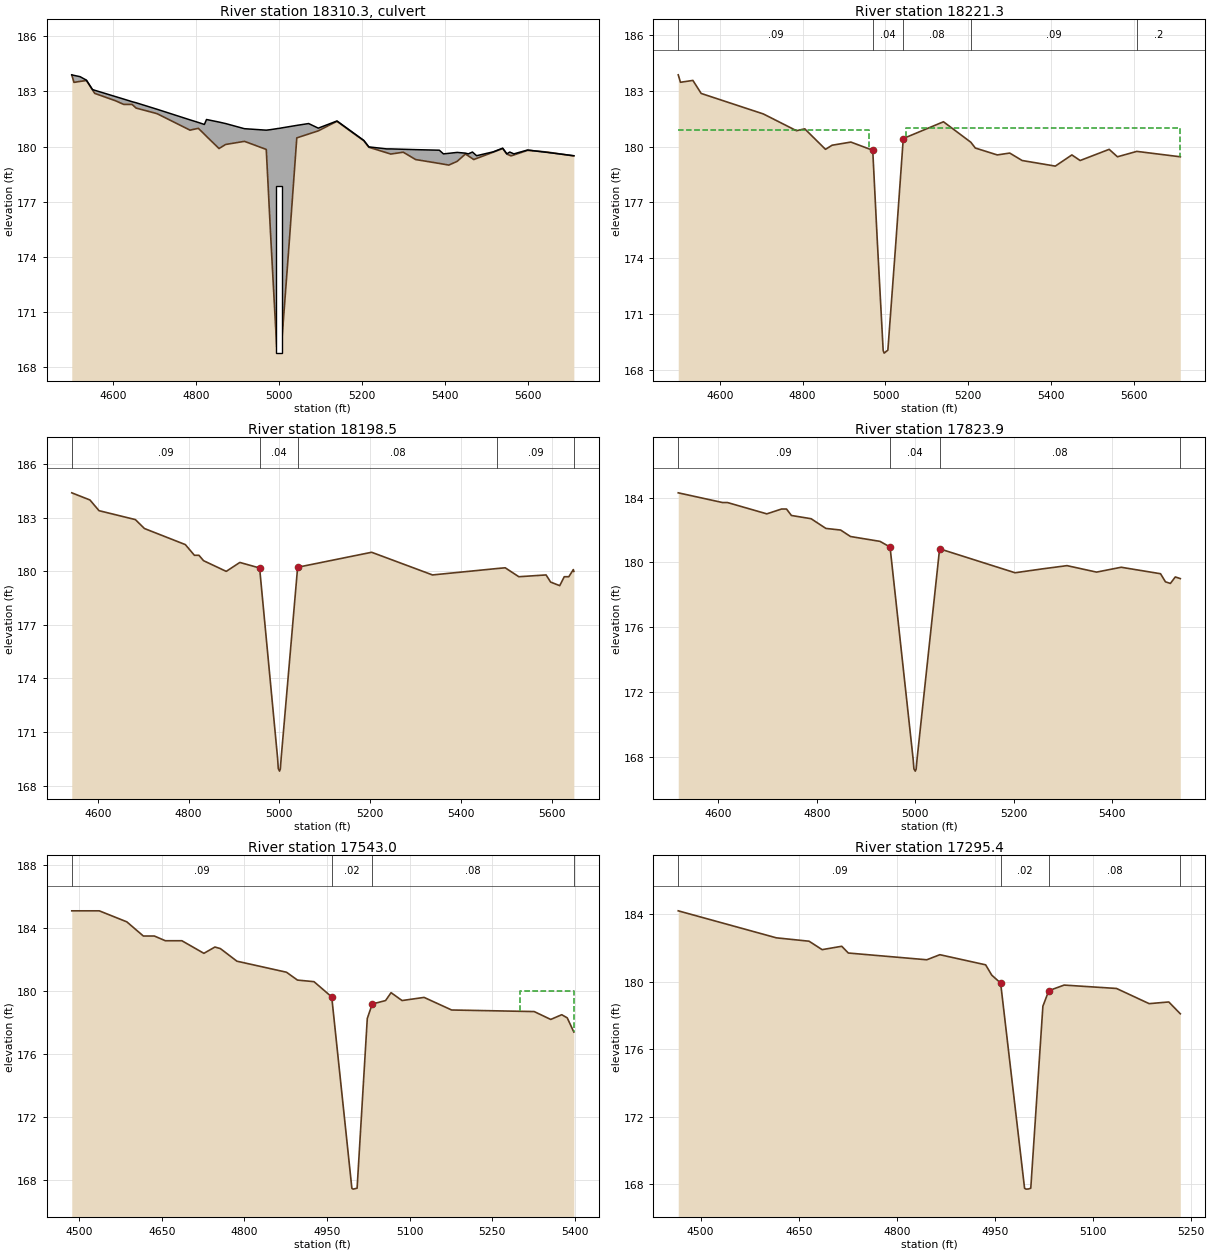
Type RM Length L Ch R = 2 ,18310.3 ,,,
BEGIN DESCRIPTION:
HUFFSMITH ROAD
Structure ID: J131-00-00-07
END DESCRIPTION:
Bridge Culvert--1,0,-1,-1, 0
Deck Dist Width WeirC Skew NumUp NumDn MinLoCord MaxHiCord MaxSubmerge Is_Ogee
10,158,3,0, 51, 51, , , .95, 0, 1,1,,
  4499.8  4505.2  4519.8  4535.2  4549.8  4555.2  4625.2  4645.2  4655.2  4705.2
  4785.2  4805.2  4819.8    4825  4855.2    4871  4916.4  4969.2    4980  4994.4
  4996.7  5001.6  5005.7  5024.3  5042.9  5071.4  5094.7  5139.9  5204.8  5216.8
  5259.8  5269.8  5299.8  5329.8  5386.8  5396.8  5409.8  5429.8  5449.8  5456.8
  5466.8  5469.8  5476.8  5516.8  5539.8  5549.8  5556.8  5559.8  5566.8  5599.8
  5711.5
   183.9  183.87   183.8  183.61   183.1  183.06  182.58  182.44  182.38  182.03
  181.45  181.31   181.2  181.47  181.33  181.25  180.97  180.89  180.92  180.97
  180.98  180.99  181.01  181.08  181.15  181.25     181  181.39  180.33  179.98
  179.87  179.87  179.85  179.83   179.8   179.6  179.63  179.68  179.64   179.6
   179.7  179.64   179.5  179.71  179.91   179.6   179.7  179.67   179.6  179.81
   179.5
   183.9   183.5  183.55   183.6  183.09   182.9   182.3   182.3   182.1   181.8
   180.9     181  180.68  180.56   179.9  180.12  180.29  179.85  175.07   169.1
  168.96  168.97  169.12  174.69  180.48  180.69  180.86  181.38  180.32  179.97
   178.7   179.6   179.7   179.3  179.09  179.05     179   179.2   179.6   179.5
  179.35   179.3  179.36   179.7   179.9   179.6  179.53   179.5  179.55   179.8
   179.5
  4499.8  4505.2  4519.8  4535.2  4549.8  4555.2  4625.2  4645.2  4655.2  4705.2
  4785.2  4805.2  4819.8    4825  4855.2    4871  4916.4  4969.2    4980  4994.4
  4996.7  5001.6  5005.7  5024.3  5042.9  5071.4  5094.7  5139.9  5204.8  5216.8
  5259.8  5269.8  5299.8  5329.8  5386.8  5396.8  5409.8  5429.8  5449.8  5456.8
  5466.8  5469.8  5476.8  5516.8  5539.8  5549.8  5556.8  5559.8  5566.8  5599.8
  5711.5
   183.9  183.87   183.8  183.61   183.1  183.06  182.58  182.44  182.38  182.03
  181.45  181.31   181.2  181.47  181.33  181.25  180.97  180.89  180.92  180.97
  180.98  180.99  181.01  181.08  181.15  181.25     181  181.39  180.33  179.98
  179.87  179.87  179.85  179.83   179.8   179.6  179.63  179.68  179.64   179.6
   179.7  179.64   179.5  179.71  179.91   179.6   179.7  179.67   179.6  179.81
   179.5
   183.9   183.5  183.55   183.6  183.09   182.9   182.3   182.3   182.1   181.8
   180.9     181  180.68  180.56   179.9  180.12  180.29  179.85  175.07   169.1
  168.96  168.97  169.12  174.69  180.48  180.69  180.86  181.38  180.32  179.97
   178.7   179.6   179.7   179.3  179.09  179.05     179   179.2   179.6   179.5
  179.35   179.3  179.36   179.7   179.9   179.6  179.53   179.5  179.55   179.8
   179.5
BR Coef= 1 , 0 , 0 ,1.25, 0 ,,,.8,-1,2,0,
WSPro=,,,, 1 ,,,, 0 ,,,, 0 ,,,,-1 ,-1 ,-1 , 0 , 0 , 0 , 0 , 0
Culvert=2,9.1,12.8,158,.015,.4,1,8,1,168.76,5000,168.58,5000,Culvert #1  , 0 ,10
Culvert Bottom n=.015
BR U #Sta/Elev= 74
  4499.8  183.89  4505.2  183.49  4519.8  183.54  4535.2  183.59  4549.8  183.08
  4555.2  182.89  4605.2  182.49  4625.2  182.29  4645.2  182.29  4655.2  182.09
  4705.2  181.79  4709.8  181.74  4785.2  180.89  4805.2  180.99  4819.8  180.67
    4825  180.55  4855.2  179.89    4871  180.11  4873.5  180.12  4916.4  180.28
  4925.3  180.21 4957.29  179.94  4957.4  179.94 4957.51  179.94  4969.2  179.84
  4969.6  179.66    4980  175.06  4994.4  169.09  4996.7  168.95  5001.6  168.96
  5005.7  169.11 5016.09  172.22  5016.2  172.25 5016.31  172.29  5016.6  172.37
  5024.3  174.68  5042.9  180.47  5071.4  180.68  5094.7  180.85  5123.1  181.18
  5139.9  181.37    5177  180.76  5186.8   180.6  5204.8  180.31    5206  180.27
  5216.8  179.96  5269.8  179.59  5299.8  179.69  5329.8  179.29  5386.8  179.08
  5396.8  179.04  5409.8  178.99  5429.8  179.19  5436.8  179.33  5449.8  179.59
  5456.8  179.49  5466.8  179.34  5469.8  179.29  5476.8  179.35  5516.8  179.69
  5539.8  179.89  5549.8  179.59  5556.8  179.52  5559.8  179.49  5566.8  179.54
  5599.8  179.79  5606.5  179.78  5606.8  179.78  5636.8  179.72  5649.8  179.69
  5676.8   179.6  5695.3  179.54  5709.8  179.49  5711.5  179.49
BR U #Mann= 5
  4499.8     .09  4969.2    .035  5042.9     .08    5206     .09  5606.5      .2
BR D #Sta/Elev= 74
  4499.8  183.85  4505.2  183.45  4519.8   183.5  4535.2  183.55  4549.8  183.04
  4555.2  182.85  4605.2  182.45  4625.2  182.25  4645.2  182.25  4655.2  182.05
  4705.2  181.75  4709.8   181.7  4785.2  180.85  4805.2  180.95  4819.8  180.63
    4825  180.51  4855.2  179.85    4871  180.07  4873.5  180.08  4916.4  180.24
  4925.3  180.17 4957.29   179.9  4957.4   179.9 4957.51   179.9  4969.2   179.8
  4969.6  179.62    4980  175.02  4994.4  169.05  4996.7  168.91  5001.6  168.92
  5005.7  169.07 5016.09  172.18  5016.2  172.21 5016.31  172.25  5016.6  172.33
  5024.3  174.64  5042.9  180.43  5071.4  180.64  5094.7  180.81  5123.1  181.14
  5139.9  181.33    5177  180.72  5186.8  180.56  5204.8  180.27    5206  180.23
  5216.8  179.92  5269.8  179.55  5299.8  179.65  5329.8  179.25  5386.8  179.04
  5396.8     179  5409.8  178.95  5429.8  179.15  5436.8  179.29  5449.8  179.55
  5456.8  179.45  5466.8   179.3  5469.8  179.25  5476.8  179.31  5516.8  179.65
  5539.8  179.85  5549.8  179.55  5556.8  179.48  5559.8  179.45  5566.8   179.5
  5599.8  179.75  5606.5  179.74  5606.8  179.74  5636.8  179.68  5649.8  179.65
  5676.8  179.56  5695.3   179.5  5709.8  179.45  5711.5  179.45
BR D #Mann= 5
  4499.8     .09  4969.2    .035  5042.9     .08    5206     .09  5606.5      .2
BC Design=,, 0 ,, 0 ,,,,,,

Type RM Length L Ch R = 1 ,18221.3 ,22.8,22.8,22.8
BEGIN DESCRIPTION:
Downstream Section of Bridge/Culvert/Weir
END DESCRIPTION:
XS GIS Cut Line= 4
    3036210.1801   13963887.2257    3036787.1752   13963912.8149
    3037080.4358   13963926.0248    3037416.0111   13963984.2796
#Sta/Elev= 30
  4499.8  183.85  4505.2  183.45  4535.2  183.55  4555.2  182.85  4705.2  181.75
  4785.2  180.85  4805.2  180.95  4855.2  179.85    4871  180.07  4916.4  180.24
  4969.2   179.8    4980  175.02  4994.4  169.05  4996.7  168.91  5005.7  169.07
  5024.3  174.64  5042.9  180.43  5139.9  181.33    5206  180.23  5216.8  179.92
  5269.8  179.55  5299.8  179.65  5329.8  179.25  5409.8  178.95  5449.8  179.55
  5469.8  179.25  5539.8  179.85  5559.8  179.45  5606.5  179.74  5711.5  179.45
#Mann= 5 ,-1 , 0
  4499.8     .09       0  4969.2     .04       0  5042.9     .08       0
    5206     .09       0  5606.5      .2       0
#XS Ineff= 2 , 0
       0    4960  180.89    5050       0     181
Permanent Ineff=
       F       F
Bank Sta=4969.2,5042.9
XS Rating Curve= 0
Exp/Cntr=.5,.3

Type RM Length L Ch R = 1 ,18198.5 ,380.99,374.6,368.28
BEGIN DESCRIPTION:
Cross Section XS55
END DESCRIPTION:
XS GIS Cut Line= 3
    3036303.9578   13964139.8282    3036938.5487   13963981.1805
    3037389.4423   13963992.3137
#Sta/Elev= 30
  4542.9   184.4  4582.9     184  4602.9   183.4  4682.9   182.9  4702.9   182.4
  4792.9   181.5  4812.9   180.9  4822.9   180.9  4832.9   180.6  4882.9     180
  4912.9   180.5 4956.39  180.19    4996  169.53  4997.5  168.95  5000.3  168.81
    5002  168.93    5004  169.59 5040.09  180.23    5203  181.07    5337   179.8
  5479.3  180.16    5497   180.2    5527   179.7    5587   179.8    5597   179.4
    5617   179.2    5627   179.7    5637   179.7    5647   180.1  5648.1     180
#Mann= 5 ,-1 , 0
  4542.9     .09       0 4956.39     .04       0 5040.09     .08       0
  5479.3     .09       0  5648.1      .2       0
Bank Sta=4956.39,5040.09
XS Rating Curve= 0
Exp/Cntr=.3,.1

Type RM Length L Ch R = 1 ,17823.9 ,285.41,280.9,274.82
BEGIN DESCRIPTION:
Cross Section XS54
END DESCRIPTION:
XS GIS Cut Line= 2
    3036418.0728   13964540.6225    3037381.0924    13964203.844
#Sta/Elev= 29
  4518.6   184.3  4608.6   183.7  4618.6   183.7  4698.6     183  4728.6   183.3
  4738.6   183.3  4748.6   182.9  4788.6   182.7  4818.6   182.1  4848.6     182
  4868.6   181.6  4928.6   181.3    4949  180.95    4996  167.82  4997.5  167.24
  5000.3   167.1    5002  167.22    5004  167.88  5049.7  180.84    5203  179.36
  5258.6   179.6  5308.6   179.8  5368.6   179.4  5418.6   179.7  5498.6   179.3
  5508.6   178.8  5518.6   178.7  5528.6   179.1  5538.8     179
#Mann= 4 ,-1 , 0
  4518.6     .09       0    4949     .04       0  5049.7     .08       0
  5538.8      .2       0
Bank Sta=4949,5049.7
XS Rating Curve= 0
Exp/Cntr=.3,.1

Type RM Length L Ch R = 1 ,17543.0 ,245.97,247.6,249.56
BEGIN DESCRIPTION:
Cross Section XS53
END DESCRIPTION:
XS GIS Cut Line= 2
    3036546.1043   13964832.8683    3037378.3091    13964459.907
#Sta/Elev= 30
  4486.4   185.1  4536.4   185.1  4586.4   184.4  4616.4   183.5  4636.4   183.5
  4656.4   183.2  4686.4   183.2  4726.4   182.4  4746.4   182.8  4756.4   182.7
  4786.4   181.9  4876.4   181.2  4896.4   180.7  4926.4   180.6  4958.6  179.63
  4995.2  167.47  4997.6  167.42  5004.7  167.48  5023.2  178.26  5032.2  179.18
  5056.4   179.4  5066.4   179.9  5086.4   179.4  5126.4   179.6  5176.4   178.8
  5326.4   178.7  5356.4   178.2  5376.4   178.5  5386.4   178.3  5398.4   177.4
#Mann= 4 ,-1 , 0
  4486.4     .09       0  4958.6     .02       0  5032.2     .08       0
  5398.4      .2       0
#XS Ineff= 2 , 0
       0                    5300       0     180
Permanent Ineff=
       F       F
Bank Sta=4958.6,5032.2
XS Rating Curve= 0
Exp/Cntr=.3,.1

Type RM Length L Ch R = 1 ,17295.4 ,404.62,345.8,289.62
BEGIN DESCRIPTION:
Cross Section XS52
END DESCRIPTION:
XS GIS Cut Line= 2
      3036618.47   13965052.7485    3037328.2098   13964760.5027
#Sta/Elev= 24
  4465.7   184.2  4615.7   182.6  4665.7   182.4  4685.7   181.9  4715.7   182.1
  4725.7   181.7  4845.7   181.3  4865.7   181.6  4935.7     181    4945  180.39
  4958.6  179.92  4995.2  167.76  4997.6  167.71  5001.2  167.72  5002.9  167.74
  5004.7  167.77  5023.2  178.55  5025.2  178.75  5032.2  179.47  5055.7   179.8
  5135.7   179.6  5185.7   178.7  5215.7   178.8  5233.3   178.1
#Mann= 4 ,-1 , 0
  4465.7     .09       0  4958.6     .02       0  5032.2     .08       0
  5233.3      .2       0
Bank Sta=4958.6,5032.2
XS Rating Curve= 0
Exp/Cntr=.3,.1

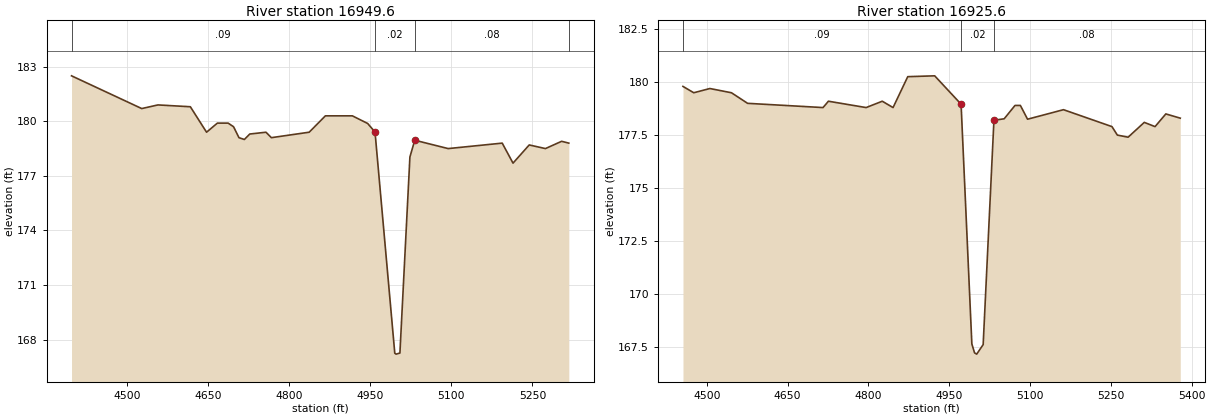
Type RM Length L Ch R = 1 ,16949.6 ,52.3,24,22.4
BEGIN DESCRIPTION:
Cross Section XS51
END DESCRIPTION:
XS GIS Cut Line= 4
    3037136.1626   13965734.6554     3037244.711   13965214.1795
    3037308.7268   13965094.4979    3037314.2933   13964841.2182
#Sta/Elev= 30
  4396.7   182.5  4526.7   180.7  4556.7   180.9  4616.7   180.8  4646.7   179.4
  4666.7   179.9  4686.7   179.9  4696.7   179.7  4706.7   179.1  4716.7     179
  4726.7   179.3  4756.7   179.4  4766.7   179.1  4836.7   179.4  4866.7   180.3
  4916.7   180.3    4945  179.88  4958.6  179.41  4995.2  167.25  4997.6   167.2
  5004.7  167.26  5023.2  178.04  5032.2  178.96  5094.1   178.5  5194.1   178.8
  5214.1   177.7  5244.1   178.7  5274.1   178.5  5304.1   178.9  5317.4   178.8
#Mann= 4 ,-1 , 0
  4396.7     .09       0  4958.6     .02       0  5032.2     .08       0
  5317.4      .2       0
Bank Sta=4958.6,5032.2
XS Rating Curve= 0
Exp/Cntr=.5,.3

Type RM Length L Ch R = 1 ,16925.6 ,146,146,146
BEGIN DESCRIPTION:
Upstream Section of Bridge/Culvert/Weir
END DESCRIPTION:
XS GIS Cut Line= 5
    3037266.7346   13965717.2026    3037289.0114    13965291.159
    3037294.5795    13965173.533    3037313.4365   13965117.0696
    3037321.4846   13964797.8302
#Sta/Elev= 30
  4455.7  179.81  4475.7  179.51  4505.7  179.71  4545.7  179.51  4575.7  179.01
  4715.7  178.81  4725.7  179.11  4795.7  178.81  4825.7  179.11  4845.7  178.81
    4873  180.27    4923  180.31    4972  178.97    4992  167.64    4997  167.22
    5001  167.16    5013  167.61    5033  178.21    5052  178.28  5072.1  178.91
  5082.1  178.91  5095.4  178.26  5162.1  178.71  5252.1  177.91  5262.1  177.51
  5282.1  177.41  5312.1  178.11  5332.1  177.91  5352.1  178.51  5378.9  178.31
#Mann= 3 ,-1 , 0
  4455.7     .09       0    4972     .02       0    5033     .08       0
#XS Ineff= 2 , 0
       0    4962     179    5043       0   177.9
Permanent Ineff=
       F       F
Bank Sta=4972,5033
XS Rating Curve= 0
Exp/Cntr=.5,.3