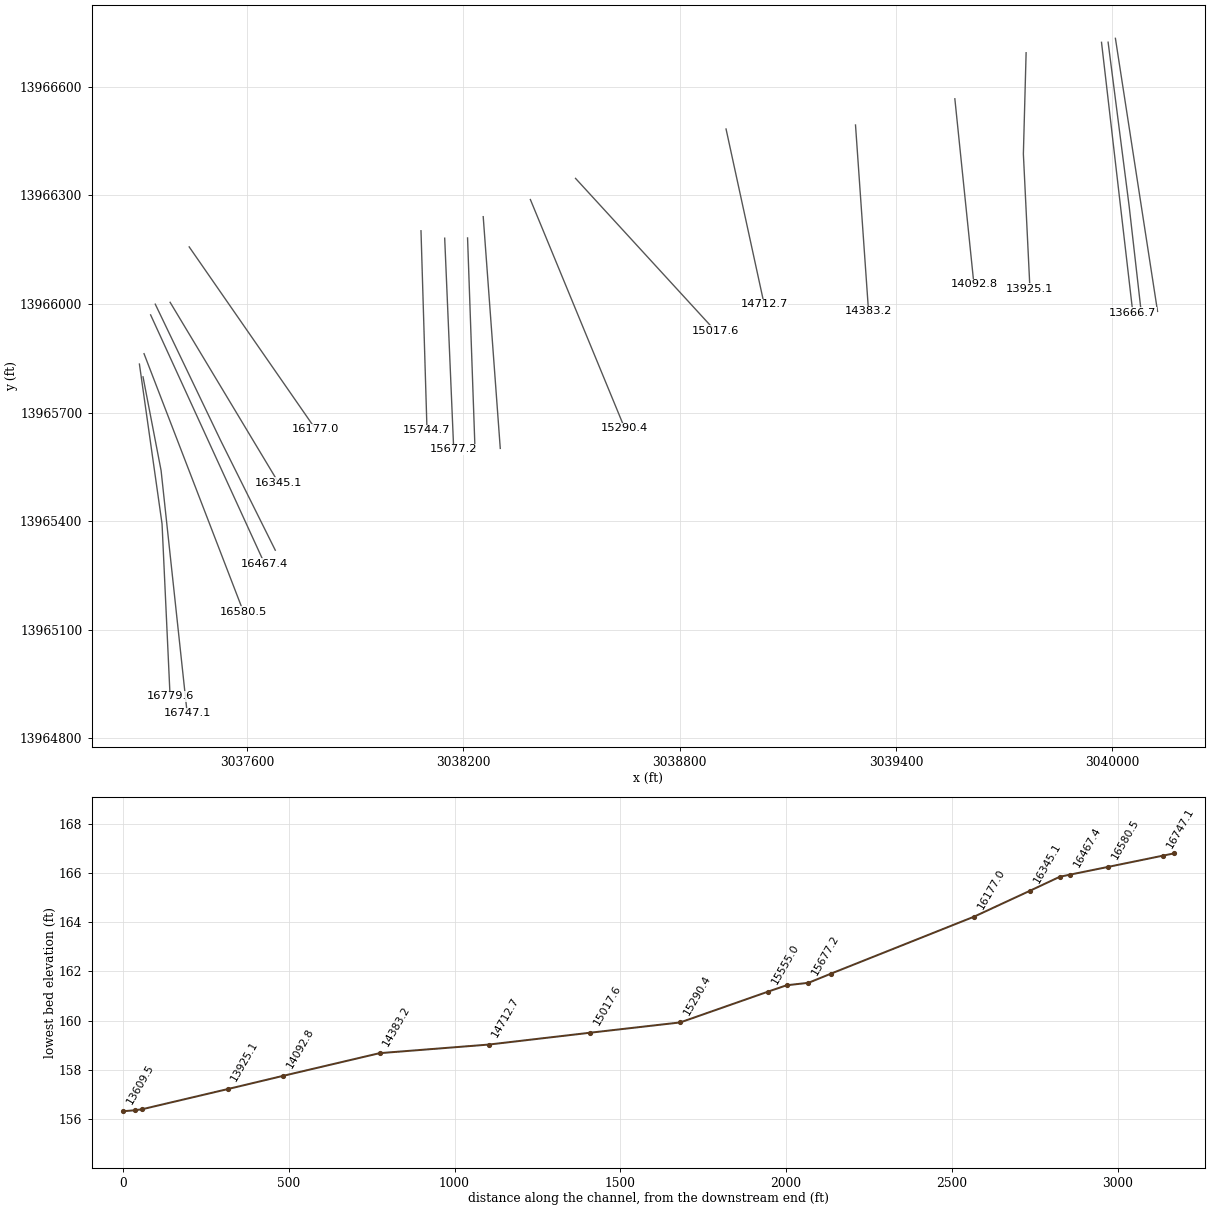
HEC-RAS study J131-00-00.PRJ: J131-00-00

--- J131-00-00.g01 (geometry) --- (continued)

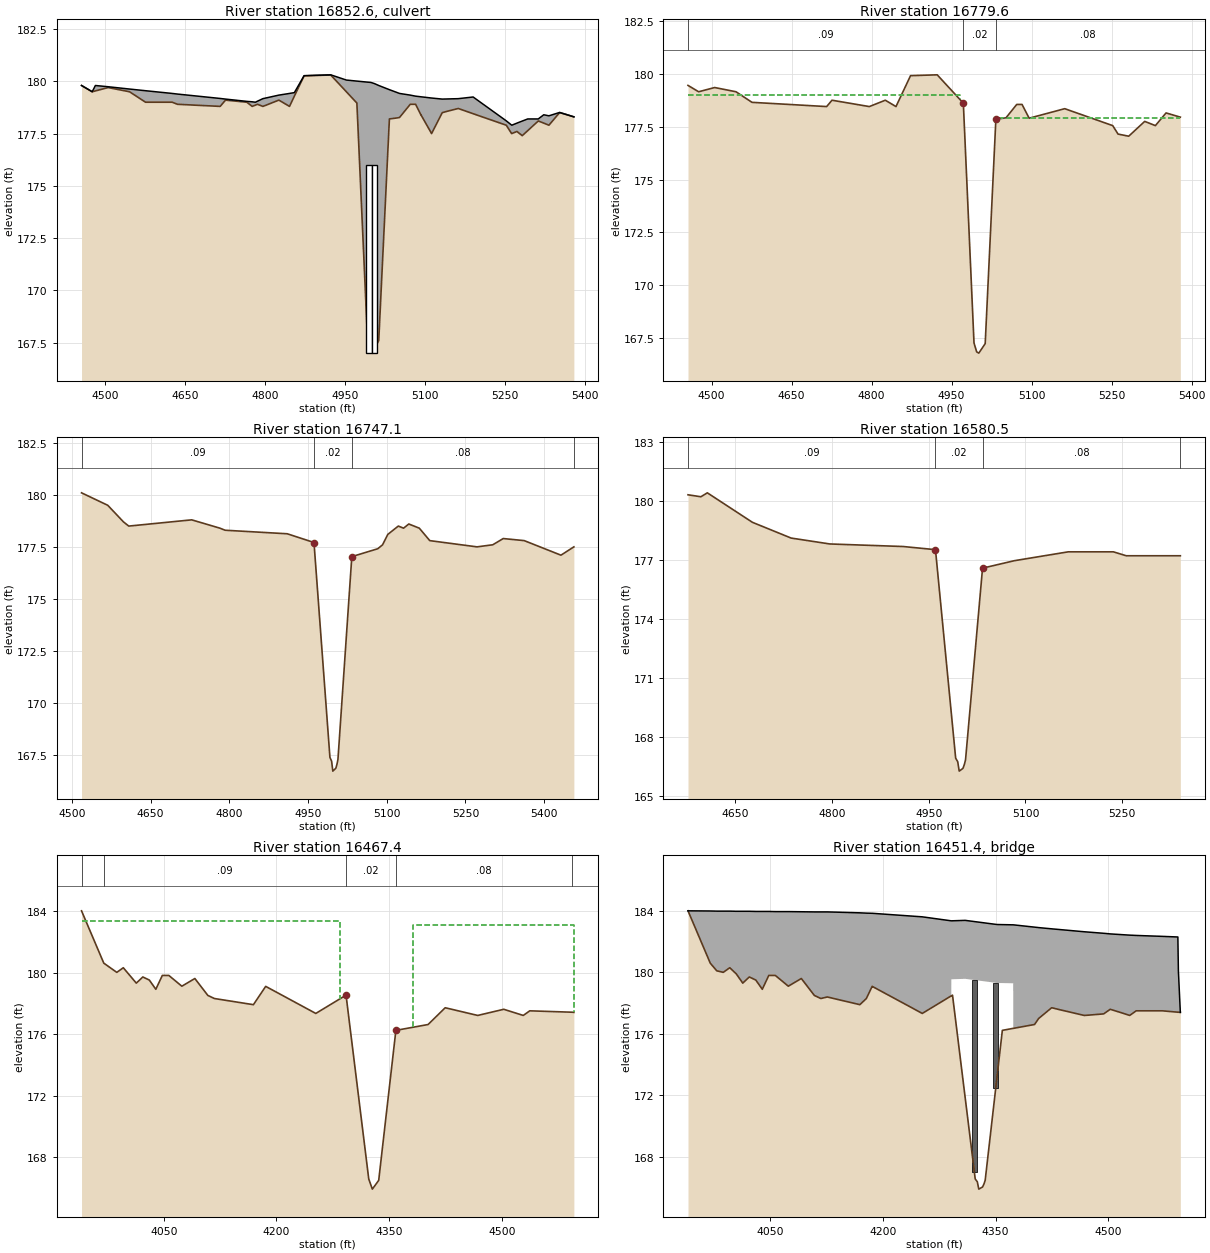
Type RM Length L Ch R = 2 ,16852.6 ,,,
BEGIN DESCRIPTION:
ULRICH ROAD
Structure ID: J131-00-00-06
END DESCRIPTION:
Bridge Culvert--1,0,-1,-1, 0
Deck Dist Width WeirC Skew NumUp NumDn MinLoCord MaxHiCord MaxSubmerge Is_Ogee
10,126,3,0, 45, 45, , , .95, 0, 1,1,,
  4455.7  4475.7  4481.7  4505.7  4545.7  4575.7  4625.7  4635.7  4715.7  4725.7
  4765.7  4775.7  4781.7  4785.7  4795.7  4825.7  4845.7  4854.8    4873    4923
  4952.3    4972    4992    4997    4999    5005    5013    5033    5052  5072.1
  5082.1  5112.1  5132.1  5162.1    5190  5252.1  5262.4  5272.1  5282.1  5292.4
  5312.1  5322.4  5332.1  5352.1  5378.9
   179.8   179.5   179.8  179.74  179.63  179.55  179.42  179.39  179.18  179.15
  179.04  179.02     179  179.05  179.17  179.34  179.42  179.46  180.27  180.31
  180.06  180.01  179.96  179.95  179.94  179.89   179.8   179.6  179.42  179.34
  179.29   179.2  179.15  179.17  179.25  178.11   177.9     178   178.1   178.2
   178.2   178.4  178.35  178.51   178.3
   179.8   179.5  179.54   179.7   179.5     179     179   178.9   178.8   179.1
     179   178.8  178.86   178.9   178.8   179.1   178.8  179.29  180.26   180.3
   179.5  178.96  167.63  167.21  167.16  167.21   167.6   178.2  178.27   178.9
   178.9   177.5   178.5   178.7  178.45   177.9   177.5   177.6   177.4  177.64
   178.1     178   177.9   178.5   178.3
  4455.7  4475.7  4481.7  4505.7  4545.7  4575.7  4625.7  4635.7  4715.7  4725.7
  4765.7  4775.7  4781.7  4785.7  4795.7  4825.7  4845.7  4854.8    4873    4923
  4952.3    4972    4992    4997    4999    5005    5013    5033    5052  5072.1
  5082.1  5112.1  5132.1  5162.1    5190  5252.1  5262.4  5272.1  5282.1  5292.4
  5312.1  5322.4  5332.1  5352.1  5378.9
   179.8   179.5   179.8  179.74  179.63  179.55  179.42  179.39  179.18  179.15
  179.04  179.02     179  179.05  179.17  179.34  179.42  179.46  180.27  180.31
  180.06  180.01  179.96  179.95  179.94  179.89   179.8   179.6  179.42  179.34
  179.29   179.2  179.15  179.17  179.25  178.11   177.9     178   178.1   178.2
   178.2   178.4  178.35  178.51   178.3
  179.48  179.18  179.22  179.38  179.18  178.68  178.68  178.58  178.48  178.78
  178.68  178.48  178.54  178.58  178.48  178.78  178.48  178.97  179.94  179.98
  179.18  178.64  167.31  166.89  166.84  166.89  167.28  177.88  177.95  178.58
  178.58  177.18  178.18  178.38  178.13  177.58  177.18  177.28  177.08  177.32
  177.78  177.68  177.58  178.18  177.98
BR Coef= 1 , 0 , 0 ,1.25, 0 ,,,.8,-1,2,0,
WSPro=,,,, 1 ,,,, 0 ,,,, 0 ,,,,-1 ,-1 ,-1 , 0 , 0 , 0 , 0 , 0
Culvert=2,9,10,126,.015,.4,1,8,1,167,4994.5,166.93,4994.5,Culvert #1  , 0 ,10
Culvert Bottom n=.015
Culvert=2,9,10,126,.015,.4,1,8,1,167,5005.5,166.94,5005.5,Culvert #2  , 0 ,10
Culvert Bottom n=.015
BR U #Sta/Elev= 64
  4455.7   179.8  4475.7   179.5  4481.7  179.54  4505.7   179.7  4545.7   179.5
  4575.7     179  4625.7     179  4635.7   178.9  4715.7   178.8  4725.7   179.1
  4765.7     179  4775.7   178.8  4781.7  178.86  4785.7   178.9  4795.7   178.8
    4802  178.86  4825.7   179.1  4845.7   178.8  4854.8  179.29    4873  180.26
    4908  180.29    4923   180.3  4952.3   179.5    4972  178.96    4992  167.63
 4992.39   167.6  4992.5  167.59 4992.61  167.58    4997  167.21    4999  167.16
  4999.9  167.16    5001  167.15    5005  167.21    5013   167.6    5033   178.2
  5047.9  178.25    5052  178.27  5072.1   178.9  5082.1   178.9    5092   178.4
 5092.09   178.4  5092.2  178.39 5092.31  178.39  5095.4  178.25  5112.1   177.5
  5132.1   178.5  5142.1  178.57  5162.1   178.7    5190  178.45  5252.1   177.9
  5252.4  177.89  5262.1   177.5  5262.4   177.5  5272.1   177.6  5282.1   177.4
  5292.4  177.64  5312.1   178.1  5312.4   178.1  5322.4     178  5332.1   177.9
  5352.1   178.5    5353   178.5  5362.4  178.43  5378.9   178.3
BR U #Mann= 3
  4455.7     .09    4972    .015    5033     .08
BR U Banks=4972,5033
BR D #Sta/Elev= 64
  4455.7  179.48  4475.7  179.18  4481.7  179.22  4505.7  179.38  4545.7  179.18
  4575.7  178.68  4625.7  178.68  4635.7  178.58  4715.7  178.48  4725.7  178.78
  4765.7  178.68  4775.7  178.48  4781.7  178.54  4785.7  178.58  4795.7  178.48
    4802  178.54  4825.7  178.78  4845.7  178.48  4854.8  178.97    4873  179.94
    4908  179.97    4923  179.98  4952.3  179.18    4972  178.64    4992  167.31
 4992.39  167.28  4992.5  167.27 4992.61  167.26    4997  166.89    4999  166.84
  4999.9  166.84    5001  166.83    5005  166.89    5013  167.28    5033  177.88
  5047.9  177.93    5052  177.95  5072.1  178.58  5082.1  178.58    5092  178.08
 5092.09  178.08  5092.2  178.07 5092.31  178.07  5095.4  177.93  5112.1  177.18
  5132.1  178.18  5142.1  178.25  5162.1  178.38    5190  178.13  5252.1  177.58
  5252.4  177.57  5262.1  177.18  5262.4  177.18  5272.1  177.28  5282.1  177.08
  5292.4  177.32  5312.1  177.78  5312.4  177.78  5322.4  177.68  5332.1  177.58
  5352.1  178.18    5353  178.18  5362.4  178.11  5378.9  177.98
BR D #Mann= 3
  4455.7     .09    4972    .015    5033     .08
BR D Banks=4972,5033
BC Design=,, 0 ,, 0 ,,,,,,

Type RM Length L Ch R = 1 ,16779.6 ,32.5,32.5,32.5
BEGIN DESCRIPTION:
Downstream Section of Bridge/Culvert/Weir
END DESCRIPTION:
XS GIS Cut Line= 3
    3037301.4637   13965834.0214    3037364.2588   13965392.5308
    3037386.5625   13964915.7885
#Sta/Elev= 30
  4455.7  179.45  4475.7  179.15  4505.7  179.35  4545.7  179.15  4575.7  178.65
  4715.7  178.45  4725.7  178.75  4795.7  178.45  4825.7  178.75  4845.7  178.45
    4873  179.91    4923  179.95    4972  178.61    4992  167.28    4997  166.86
    5001   166.8    5013  167.25    5033  177.85    5052  177.92  5072.1  178.55
  5082.1  178.55  5095.4   177.9  5162.1  178.35  5252.1  177.55  5262.1  177.15
  5282.1  177.05  5312.1  177.75  5332.1  177.55  5352.1  178.15  5378.9  177.95
#Mann= 3 ,-1 , 0
  4455.7     .09       0    4972     .02       0    5033     .08       0
#XS Ineff= 2 , 0
       0 4965.33     179 5039.67       0   177.9
Permanent Ineff=
       F       F
Bank Sta=4972,5033
XS Rating Curve= 0
Exp/Cntr=.5,.3

Type RM Length L Ch R = 1 ,16747.1 ,129.34,166.6,196.52
BEGIN DESCRIPTION:
Cross Section XS50
END DESCRIPTION:
XS GIS Cut Line= 3
      3037311.51   13965798.6712    3037361.6093   13965539.8249
     3037433.975   13964869.0511
#Sta/Elev= 30
  4518.3   180.1  4568.3   179.5  4598.3   178.7  4608.3   178.5  4728.3   178.8
    4782   178.4    4792   178.3  4910.3  178.13 4961.31  177.71  4991.7  167.37
  4994.9  167.19  4997.2  166.71    5003  166.85  5005.1  167.04    5007  167.28
  5033.4  177.03  5082.9  177.41    5092   177.6    5102   178.1    5122   178.5
    5132   178.4    5142   178.6    5162   178.4    5182   177.8    5272   177.5
    5302   177.6    5322   177.9    5362   177.8    5432   177.1  5456.6   177.5
#Mann= 4 ,-1 , 0
  4518.3     .09       0 4961.31     .02       0  5033.4     .08       0
  5456.6      .2       0
Bank Sta=4961.31,5033.4
XS Rating Curve= 0
Exp/Cntr=.3,.1

Type RM Length L Ch R = 1 ,16580.5 ,78.88,113.1,86.58
BEGIN DESCRIPTION:
Cross Section XS49
END DESCRIPTION:
XS GIS Cut Line= 2
    3037314.2933   13965862.6869    3037589.8394   13965150.1638
#Sta/Elev= 21
  4576.4   180.3  4596.4   180.2  4606.4   180.4  4676.4   178.9  4736.4   178.1
  4796.4   177.8  4910.3  177.67 4960.38  177.51  4991.7  166.91  4994.9  166.73
  4997.2  166.25    5003  166.39  5005.1  166.58    5007  166.82  5033.4  176.57
  5082.9  176.95  5166.4   177.4  5236.4   177.4  5256.4   177.2  5336.4   177.2
  5340.3   177.2
#Mann= 4 ,-1 , 0
  4576.4     .09       0 4960.38     .02       0  5033.4     .08       0
  5340.3      .2       0
Bank Sta=4960.38,5033.4
XS Rating Curve= 0
Exp/Cntr=.5,.3

Type RM Length L Ch R = 1 ,16467.4 ,32,32,32
BEGIN DESCRIPTION:
Upstream Section of Bridge/Culvert/Weir
END DESCRIPTION:
XS GIS Cut Line= 2
    3037332.5706   13965969.9223    3037648.7611   13965282.3914
#Sta/Elev= 30
3940.589  184.033970.207  180.633987.527  180.033996.188  180.334013.508  179.33
4022.168  179.734030.828  179.534039.489  178.934048.149  179.834056.809  179.83
 4074.13  179.13 4091.45  179.634108.771  178.534117.431  178.334169.393  177.93
 4185.76  179.124252.444  177.364292.714  178.554322.939   166.64327.702  165.94
4336.189  166.514359.052  176.26 4401.92  176.644424.697  177.734467.999  177.23
4502.639  177.63 4528.62  177.23 4537.28  177.534593.398  177.444595.997  177.43
#Mann= 5 ,-1 , 0
3940.589      .2       03970.207     .09       04292.714     .02       0
4359.052     .08       04593.398      .2       0
#XS Ineff= 2 , 0
       04285.094   183.44382.088       0   183.1
Permanent Ineff=
       F       F
Bank Sta=4292.714,4359.052
XS Rating Curve= 0
Skew Angle= 30
Exp/Cntr=.5,.3

Type RM Length L Ch R = 3 ,16451.4 ,,,
BEGIN DESCRIPTION:
MKT RAILROAD
Structure ID: J131-00-00-05
END DESCRIPTION:
Bridge Culvert--1,0,-1,-1, 0
Deck Dist Width WeirC Skew NumUp NumDn MinLoCord MaxHiCord MaxSubmerge Is_Ogee
10,12,2.6,30, 39, 39, , , .95, 0, 1,1,,
3940.5893970.2073978.8673987.5273996.1884004.8484013.5084022.1684030.8284039.489
4048.1494056.809 4074.13 4091.454108.7714117.4314126.0914169.3934178.053 4185.76
4252.4444291.0784291.1564309.6024351.9514373.5064373.602 4401.924407.3764424.697
4467.9994493.9794502.639 4528.62 4537.284571.9214592.7064593.3984595.997
     184  183.99  183.98  183.98  183.98  183.97  183.97  183.97  183.96  183.96
  183.96  183.95  183.95  183.94  183.93  183.93  183.93  183.87  183.85  183.84
  183.61  183.35  183.35  183.38  183.11  183.09  183.09  182.94  182.91  182.83
  182.64  182.54   182.5  182.42   182.4  182.34   182.3   180.1   177.4
     184   180.6   180.1     180   180.3   179.9   179.3   179.7   179.5   178.9
   179.8   179.8   179.1   179.6   178.5   178.3   178.4   177.9   178.3  179.09
  177.33  178.47  179.55  179.58  179.31  179.29  176.36  176.61     177   177.7
   177.2   177.3   177.6   177.2   177.5   177.5  177.41  177.41   177.4
3940.5893970.2073978.8673987.5273996.1884004.8484013.5084022.1684030.8284039.489
4048.1494056.809 4074.13 4091.454108.7714117.4314126.0914169.3934178.053 4185.76
4252.4444291.0784291.1564309.6024351.9514373.5064373.602 4401.924407.3764424.697
4467.9994493.9794502.639 4528.62 4537.284571.9214592.7064593.3984595.997
     184  183.99  183.98  183.98  183.98  183.97  183.97  183.97  183.96  183.96
  183.96  183.95  183.95  183.94  183.93  183.93  183.93  183.87  183.85  183.84
  183.61  183.35  183.35  183.38  183.11  183.09  183.09  182.94  182.91  182.83
  182.64  182.54   182.5  182.42   182.4  182.34   182.3   180.1   177.4
     184   180.6   180.1     180   180.3   179.9   179.3   179.7   179.5   178.9
   179.8   179.8   179.1   179.6   178.5   178.3   178.4   177.9   178.3  179.09
  177.33  178.47  179.55  179.58  179.31  179.29  176.36  176.61     177   177.7
   177.2   177.3   177.6   177.2   177.5   177.5  177.41  177.41   177.4
Pier Skew= 30
Pier Skew, UpSta & Num, DnSta & Num=  ,4321.727, 2 ,4321.727, 2 , 0 , 0 , 0 ,,
    6.87    6.87
  165.88  180.51
    6.87    6.87
  165.88  180.51
Pier Skew, UpSta & Num, DnSta & Num=  ,4350.305, 2 ,4350.305, 2 , 0 , 0 , 0 ,,
    6.87    6.87
  171.31  180.32
    6.87    6.87
  171.31  180.32
Abutment Skew #Up #Dn= , 2 , 2
4290.9824321.467
  179.55  167.15
4290.9824321.467
  179.55  167.15
Abutment Skew #Up #Dn= , 2 , 2
4351.9514373.679
   173.2  179.29
4351.9514373.679
   173.2  179.29
BR Coef= 1 , 1 , 1 ,1.25, 0 ,,,.8,0,2,0,
WSPro=,,,, 1 ,,,, 0 ,,,, 0 ,,,,-1 ,-1 ,-1 , 0 , 0 , 0 , 0 , 0
BR U #Sta/Elev= 65
3940.589     1843970.207   180.63978.867   180.13987.527     1803996.188   180.3
4004.848   179.94013.508   179.34022.168   179.74030.828   179.54039.489   178.9
4048.149   179.84056.809   179.8 4074.13   179.1 4091.45   179.64108.771   178.5
4117.431   178.34126.091   178.44144.105  178.194169.393   177.94178.053   178.3
4185.068  179.02 4185.76  179.094225.598  178.044252.444  177.334268.033  177.79
4290.281  178.454290.376  178.454290.472  178.454290.982  178.474291.078  178.47
4291.156  178.474292.714  178.524309.602  171.844321.467  167.154322.939  166.57
 4325.71  166.394327.702  165.914332.725  166.054334.544  166.244336.189  166.48
4351.951   173.24352.384  173.394359.052  176.234373.506  176.364373.602  176.36
4373.688  176.364374.719  176.374374.814  176.374374.909  176.374395.079  176.55
 4401.92  176.614407.376     1774424.697   177.74435.695  177.574467.999   177.2
4473.974  177.224493.979   177.34502.639   177.64516.496  177.39 4528.62   177.2
 4537.28   177.54571.921   177.54592.706  177.414593.398  177.414595.997   177.4
BR U #Mann= 5
3940.589      .23970.207     .094292.714    .0154359.052     .084593.398      .2
BR U Banks=4292.714,4359.052
BR D #Sta/Elev= 65
3940.589     1843970.207   180.63978.867   180.13987.527     1803996.188   180.3
4004.848   179.94013.508   179.34022.168   179.74030.828   179.54039.489   178.9
4048.149   179.84056.809   179.8 4074.13   179.1 4091.45   179.64108.771   178.5
4117.431   178.34126.091   178.44144.105  178.194169.393   177.94178.053   178.3
4185.068  179.02 4185.76  179.094225.598  178.044252.444  177.334268.033  177.79
4290.281  178.454290.376  178.454290.472  178.454290.982  178.474291.078  178.47
4291.156  178.474292.714  178.524309.602  171.844321.467  167.154322.939  166.57
 4325.71  166.394327.702  165.914332.725  166.054334.544  166.244336.189  166.48
4351.951   173.24352.384  173.394359.052  176.234373.506  176.364373.602  176.36
4373.688  176.364374.719  176.374374.814  176.374374.909  176.374395.079  176.55
 4401.92  176.614407.376     1774424.697   177.74435.695  177.574467.999   177.2
4473.974  177.224493.979   177.34502.639   177.64516.496  177.39 4528.62   177.2
 4537.28   177.54571.921   177.54592.706  177.414593.398  177.414595.997   177.4
BR D #Mann= 5
3940.589      .23970.207     .094292.714    .0154359.052     .084593.398      .2
BR D Banks=4292.714,4359.052
BC Design=,, 0 ,, 0 ,,,,,,

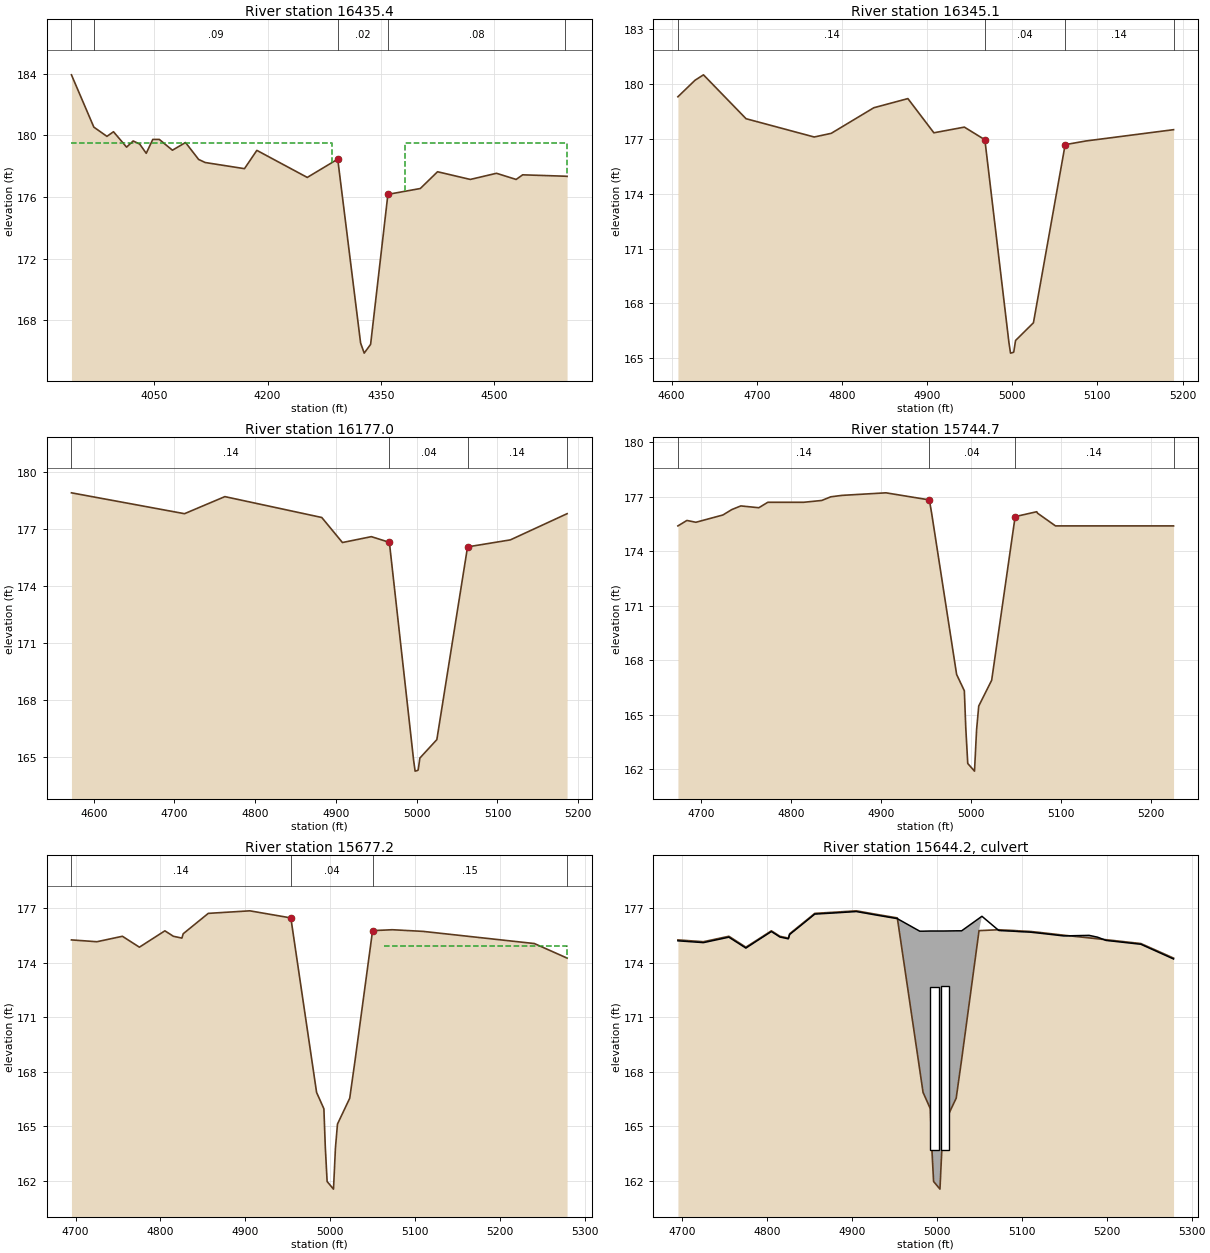
Type RM Length L Ch R = 1 ,16435.4 ,90.3,90.3,90.3
BEGIN DESCRIPTION:
Downstream Section of Bridge/Culvert/Weir
END DESCRIPTION:
XS GIS Cut Line= 3
     3037345.452   13965999.4962     3037526.583    13965623.301
    3037678.3119   13965319.8432
#Sta/Elev= 30
3940.589  183.943970.207  180.543987.527  179.943996.188  180.244013.508  179.24
4022.168  179.644030.828  179.444039.489  178.844048.149  179.744056.809  179.74
 4074.13  179.04 4091.45  179.544108.771  178.444117.431  178.244169.393  177.84
 4185.76  179.034252.444  177.274292.714  178.464322.939  166.514327.702  165.85
4336.189  166.424359.052  176.17 4401.92  176.554424.697  177.644467.999  177.14
4502.639  177.54 4528.62  177.14 4537.28  177.444593.398  177.354595.997  177.34
#Mann= 5 ,-1 , 0
3940.589      .2       03970.207     .09       04292.714     .02       0
4359.052     .08       04593.398      .2       0
#XS Ineff= 2 , 0
       04285.094   179.54382.088       0   179.5
Permanent Ineff=
       F       F
Bank Sta=4292.714,4359.052
XS Rating Curve= 0
Skew Angle= 30
Exp/Cntr=.5,.3

Type RM Length L Ch R = 1 ,16345.1 ,157.71,168.1,168.58
BEGIN DESCRIPTION:
Cross Section XS48
END DESCRIPTION:
XS GIS Cut Line= 2
     3037386.659   13966004.6349    3037687.2547   13965506.4253
#Sta/Elev= 20
  4607.5   179.3  4627.5   180.2  4637.5   180.5  4687.5   178.1  4767.5   177.1
  4787.5   177.3  4837.5   178.7  4877.5   179.2    4908  177.33  4943.8  177.64
 4967.88  176.95  4996.1  165.87    4998  165.28  5000.6  165.31  5001.8  165.34
  5003.9  165.97  5024.9  166.94 5062.13  176.68  5086.2  176.88  5189.4   177.5
#Mann= 4 ,-1 , 0
  4607.5     .14       0 4967.88     .04       0 5062.13     .14       0
  5189.4      .2       0
Bank Sta=4967.88,5062.13
XS Rating Curve= 0
Exp/Cntr=.3,.1

Type RM Length L Ch R = 1 ,16177.0 ,461.05,432.3,382.09
BEGIN DESCRIPTION:
Cross Section XS47
END DESCRIPTION:
XS GIS Cut Line= 2
    3037439.5415    13966157.716    3037790.2365   13965653.9399
#Sta/Elev= 16
  4572.4   178.9  4712.4   177.8  4762.4   178.7  4882.4   177.6    4908  176.28
  4943.8  176.59 4966.12  176.29  4996.1  164.82    4998  164.23  5000.6  164.26
  5001.8  164.29  5003.9  164.92  5024.9  165.89 5062.95  176.05    5116  176.42
  5186.2   177.8
#Mann= 4 ,-1 , 0
  4572.4     .14       0 4966.12     .04       0 5062.95     .14       0
  5186.2      .2       0
Bank Sta=4966.12,5062.95
XS Rating Curve= 0
Exp/Cntr=.3,.1

Type RM Length L Ch R = 1 ,15744.7 ,67.4,67.5,69.82
BEGIN DESCRIPTION:
Cross Section XS46
END DESCRIPTION:
XS GIS Cut Line= 2
    3038082.4823   13966202.2487    3038099.1821   13965651.1566
#Sta/Elev= 28
  4673.8   175.4  4683.8   175.7  4693.8   175.6  4723.8     176  4733.8   176.3
  4743.8   176.5  4763.8   176.4  4773.8   176.7  4813.8   176.7  4833.8   176.8
  4843.8     177  4856.3  177.08  4905.2  177.22  4953.5  176.83 4956.15  176.06
  4983.8  167.23  4992.4  166.33    4994  164.28  4996.2  162.33  5003.7  161.91
    5006  164.18  5008.4  165.49  5022.8  166.91 5048.89  175.91  5072.9  176.18
  5073.8   176.1  5093.8   175.4  5225.1   175.4
#Mann= 4 ,-1 , 0
  4673.8     .14       0  4953.5     .04       0 5048.89     .14       0
  5225.1      .2       0
Bank Sta=4953.5,5048.89
XS Rating Curve= 0
Exp/Cntr=.5,.3

Type RM Length L Ch R = 1 ,15677.2 ,66,66,66
BEGIN DESCRIPTION:
Upstream Section of Bridge/Culvert/Weir
END DESCRIPTION:
XS GIS Cut Line= 2
    3038148.2108   13966181.7685    3038173.1919   13965598.8754
#Sta/Elev= 25
  4695.2  175.25  4725.2  175.15  4755.2  175.45  4775.2  174.85  4805.2  175.75
  4815.2  175.45  4825.2  175.35  4826.8  175.59  4856.3  176.71  4905.2  176.85
  4953.5  176.46  4983.8  166.86  4992.4  165.96    4994  163.91  4996.2  161.96
  5003.7  161.54    5006  163.81  5008.4  165.12  5022.8  166.54  5029.2  168.66
 5049.71  175.76  5072.9  175.81    5109  175.72  5240.2  175.05  5278.7  174.25
#Mann= 4 ,-1 , 0
  4695.2     .14       0  4953.5     .04       0 5049.71     .15       0
  5278.7      .2       0
#XS Ineff= 2 , 0
       0  4943.5   174.8  5063.1       0   174.9
Permanent Ineff=
       F       F
Bank Sta=4953.5,5049.71
XS Rating Curve= 0
Exp/Cntr=.5,.3

Type RM Length L Ch R = 2 ,15644.2 ,,,
BEGIN DESCRIPTION:
RUDOLPH ROAD
Structure ID: J131-00-00-04
END DESCRIPTION:
Bridge Culvert--1,0,-1,-1, 0
Deck Dist Width WeirC Skew NumUp NumDn MinLoCord MaxHiCord MaxSubmerge Is_Ogee
10,46,3,0, 40, 40, , , .95, 0, 1,1,,
  4695.2  4725.2  4755.2  4775.2  4789.3  4805.2  4809.3  4815.2  4825.2  4826.8
  4849.3  4856.3  4881.7  4905.2  4929.5  4953.5  4979.9  4983.8  4992.4    4994
  4996.2  5003.7    5006  5008.4  5022.8  5029.2  5053.1  5072.9  5075.5  5089.3
  5099.3    5109  5119.3  5149.3  5179.3  5189.3  5199.3  5209.3  5240.2  5278.7
   175.2   175.1   175.4   174.8  175.23  175.71  175.59  175.41  175.31  175.55
   176.4  176.67  176.74  176.81  176.61  176.42  175.73  175.73  175.74  175.74
  175.74  175.74  175.74  175.74  175.75  175.75  176.55  175.77  175.76  175.73
   175.7  175.68  175.63  175.47   175.5   175.4  175.22  175.17  175.01   174.2
   175.2   175.1   175.4   174.8  175.22   175.7  175.58   175.4   175.3  175.54
  176.39  176.66  176.73   176.8   176.6  176.41  168.05  166.81  165.91  163.86
  161.91  161.49  163.76  165.07  166.49  168.61  176.54  175.76  175.75  175.72
  175.69  175.67  175.62  175.46  175.31  175.26  175.21  175.16     175   174.2
  4695.2  4725.2  4755.2  4775.2  4789.3  4805.2  4809.3  4815.2  4825.2  4826.8
  4849.3  4856.3  4881.7  4905.2  4929.5  4953.5  4979.9  4983.8  4992.4    4994
  4996.2  5003.7    5006  5008.4  5022.8  5029.2  5053.1  5072.9  5075.5  5089.3
  5099.3    5109  5119.3  5149.3  5179.3  5189.3  5199.3  5209.3  5240.2  5278.7
   175.2   175.1   175.4   174.8  175.23  175.71  175.59  175.41  175.31  175.55
   176.4  176.67  176.74  176.81  176.61  176.42  175.73  175.73  175.74  175.74
  175.74  175.74  175.74  175.74  175.75  175.75  176.55  175.77  175.76  175.73
   175.7  175.68  175.63  175.47   175.5   175.4  175.22  175.17  175.01   174.2
   175.2   175.1   175.4   174.8  175.22   175.7  175.58   175.4   175.3  175.54
  176.39  176.66  176.73   176.8   176.6  176.41  168.05  166.81  165.91  163.86
  161.91  161.49  163.76  165.07  166.49  168.61  176.54  175.76  175.75  175.72
  175.69  175.67  175.62  175.46  175.31  175.26  175.21  175.16     175   174.2
BR Coef= 1 , 0 , 0 ,1.25, 0 ,,,.8,-1,2,0,
WSPro=,,,, 1 ,,,, 0 ,,,, 0 ,,,,-1 ,-1 ,-1 , 0 , 0 , 0 , 0 , 0
Culvert=2,9,10,46,.015,.4,1,8,1,163.67,4997.2,163.6,4997.2,Culvert #1  , 0 ,10
Culvert Bottom n=.015
Culvert=2,9,10,46,.015,.4,1,8,1,163.69,5009.9,163.6,5009.9,Culvert #2  , 0 ,10
Culvert Bottom n=.015
BR U #Sta/Elev= 40
  4695.2  175.25  4725.2  175.15  4755.2  175.45  4775.2  174.85  4789.3  175.27
  4805.2  175.75  4809.3  175.63  4815.2  175.45  4825.2  175.35  4826.8  175.59
  4849.3  176.44  4856.3  176.71  4881.7  176.78  4905.2  176.85  4929.5  176.65
  4953.5  176.46  4979.9   168.1  4983.8  166.86  4992.4  165.96    4994  163.91
  4996.2  161.96  5003.7  161.54    5006  163.81  5008.4  165.12  5022.8  166.54
  5029.2  168.66 5049.71  175.76  5072.9  175.81  5075.5   175.8  5089.3  175.77
  5099.3  175.74    5109  175.72  5119.3  175.67  5149.3  175.51  5179.3  175.36
  5189.3  175.31  5199.3  175.26  5209.3  175.21  5240.2  175.05  5278.7  174.25
BR U #Mann= 3
  4695.2     .14  4953.5    .035 5049.71     .15
BR D #Sta/Elev= 40
  4695.2  175.15  4725.2  175.05  4755.2  175.35  4775.2  174.75  4789.3  175.17
  4805.2  175.65  4809.3  175.53  4815.2  175.35  4825.2  175.25  4826.8  175.49
  4849.3  176.34  4856.3  176.61  4881.7  176.68  4905.2  176.75  4929.5  176.55
  4953.5  176.36  4979.9     168  4983.8  166.76  4992.4  165.86    4994  163.81
  4996.2  161.86  5003.7  161.44    5006  163.71  5008.4  165.02  5022.8  166.44
  5029.2  168.56 5049.71   175.8  5072.9  175.71  5075.5   175.7  5089.3  175.67
  5099.3  175.64    5109  175.62  5119.3  175.57  5149.3  175.41  5179.3  175.26
  5189.3  175.21  5199.3  175.16  5209.3  175.11  5240.2  174.95  5278.7  174.15
BR D #Mann= 3
  4695.2     .14  4953.5    .035 5049.71     .15
BC Design=,, 0 ,, 0 ,,,,,,

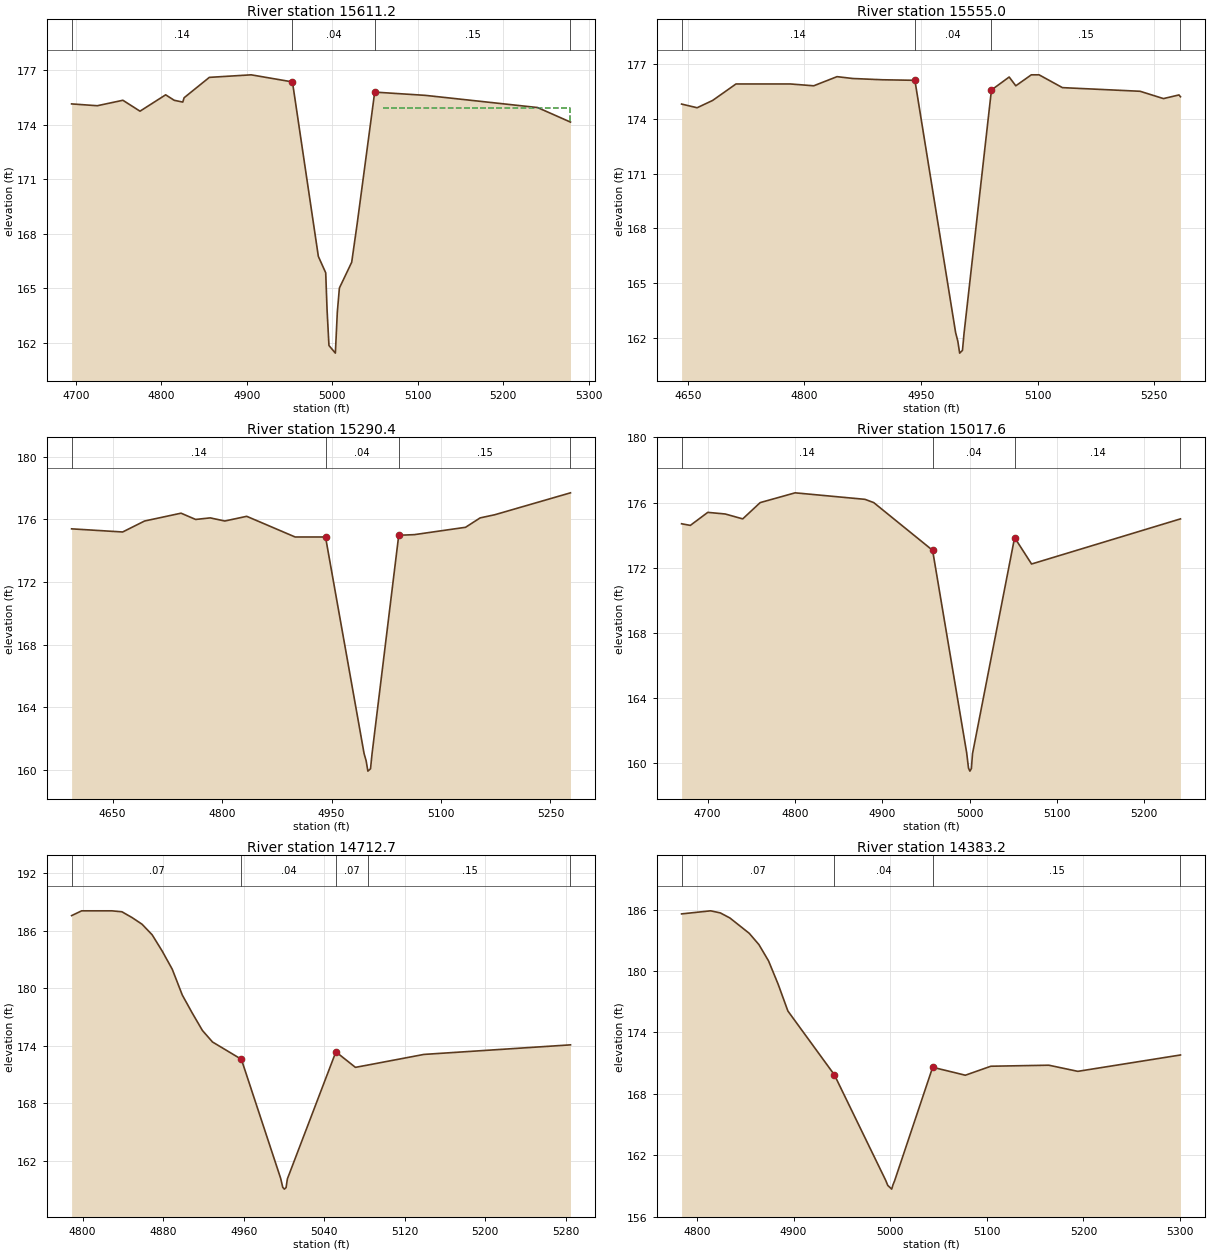
Type RM Length L Ch R = 1 ,15611.2 ,56.2,56.2,56.2
BEGIN DESCRIPTION:
Downstream Section of Bridge/Culvert/Weir
END DESCRIPTION:
XS GIS Cut Line= 2
    3038211.6357   13966182.4265    3038232.2783   13965599.2734
#Sta/Elev= 24
  4695.2  175.15  4725.2  175.05  4755.2  175.35  4775.2  174.75  4805.2  175.65
  4815.2  175.35  4825.2  175.25  4826.8  175.49  4856.3  176.61  4905.2  176.75
  4953.5  176.36  4983.8  166.76  4992.4  165.86    4994  163.81  4996.2  161.86
  5003.7  161.44    5006  163.71  5008.4  165.02  5022.8  166.44  5029.2  168.56
 5049.71   175.8    5109  175.62  5240.2  174.95  5278.7  174.15
#Mann= 4 ,-1 , 0
  4695.2     .14       0  4953.5     .04       0 5049.71     .15       0
  5278.7      .2       0
#XS Ineff= 2 , 0
       0 4946.83   174.8 5059.77       0   174.9
Permanent Ineff=
       F       F
Bank Sta=4953.5,5049.71
XS Rating Curve= 0
Exp/Cntr=.5,.3

Type RM Length L Ch R = 1 ,15555.0 ,241.9,264.6,288.87
BEGIN DESCRIPTION:
Cross Section XS45
END DESCRIPTION:
XS GIS Cut Line= 2
    3038255.0465   13966241.2148    3038302.3625   13965601.0573
#Sta/Elev= 25
    4642   174.8    4662   174.6    4682     175    4712   175.9    4782   175.9
    4812   175.8    4842   176.3    4862   176.2  4900.1  176.13  4942.2   176.1
  4994.6   162.3  4997.4  161.84  4999.8  161.18  5003.4  161.33  5005.4  162.25
 5040.68  175.57  5063.5  176.28    5072   175.8    5092   176.4    5102   176.4
    5132   175.7    5232   175.5    5262   175.1    5282   175.3  5283.9   175.2
#Mann= 4 ,-1 , 0
    4642     .14       0  4942.2     .04       0 5040.68     .15       0
  5283.9      .2       0
Bank Sta=4942.2,5040.68
XS Rating Curve= 0
Exp/Cntr=.3,.1

Type RM Length L Ch R = 1 ,15290.4 ,247.34,272.8,298.73
BEGIN DESCRIPTION:
Cross Section XS44
END DESCRIPTION:
XS GIS Cut Line= 2
    3038385.8613   13966288.5308    3038647.4909   13965656.7232
#Sta/Elev= 21
  4593.7   175.4  4663.7   175.2  4693.7   175.9  4743.7   176.4  4763.7     176
  4783.7   176.1  4803.7   175.9  4833.7   176.2  4900.1  174.88 4941.73  174.88
  4994.6  161.05  4997.4  160.59  4999.8  159.93  5003.4  160.08  5005.4     161
 5042.09  174.99  5063.5  175.03  5133.7   175.5  5153.7   176.1  5173.7   176.3
  5277.5   177.7
#Mann= 4 ,-1 , 0
  4593.7     .14       0 4941.73     .04       0 5042.09     .15       0
  5277.5      .2       0
Bank Sta=4941.73,5042.09
XS Rating Curve= 0
Exp/Cntr=.3,.1

Type RM Length L Ch R = 1 ,15017.6 ,339.28,304.9,263.41
BEGIN DESCRIPTION:
Cross Section XS43
END DESCRIPTION:
XS GIS Cut Line= 2
    3038511.1095     13966346.98    3038897.9873   13965926.7027
#Sta/Elev= 19
  4670.3   174.7  4680.3   174.6  4700.3   175.4  4720.3   175.3  4740.3     175
  4760.3     176  4800.3   176.6  4880.3   176.2  4890.3     176  4957.7  173.07
  4996.7  160.64  4998.8   159.7  5000.4  159.51  5002.1  159.67  5003.4  160.58
  5051.6  173.85    5071  172.23  5075.4   172.3  5241.5     175
#Mann= 4 ,-1 , 0
  4670.3     .14       0  4957.7     .04       0  5051.6     .14       0
  5241.5      .2       0
Bank Sta=4957.7,5051.6
XS Rating Curve= 0
Exp/Cntr=.3,.1

Type RM Length L Ch R = 1 ,14712.7 ,334.76,329.5,318.73
BEGIN DESCRIPTION:
Cross Section XS42
END DESCRIPTION:
XS GIS Cut Line= 2
    3038928.6036   13966483.3614    3039034.3687   13965999.0683
#Sta/Elev= 24
    4789   187.6    4799   188.1    4829   188.1    4839     188    4849   187.4
    4859   186.7    4869   185.6    4879   183.9    4889     182    4899   179.3
    4909   177.4    4919   175.6    4929   174.4  4957.7  172.59  4996.7  160.16
  4998.8  159.22  5000.4  159.03  5002.1  159.19  5003.4   160.1  5051.6  173.37
    5071  171.75  5083.8     172    5139   173.1  5284.7   174.1
#Mann= 5 ,-1 , 0
    4789     .07       0  4957.7     .04       0  5051.6     .07       0
  5083.8     .15       0  5284.7      .2       0
Bank Sta=4957.7,5051.6
XS Rating Curve= 0
Exp/Cntr=.3,.1

Type RM Length L Ch R = 1 ,14383.2 ,286.83,290.4,291.27
BEGIN DESCRIPTION:
Cross Section XS41
END DESCRIPTION:
XS GIS Cut Line= 2
    3039287.6484   13966494.4945    3039323.8312   13965979.5852
#Sta/Elev= 22
  4784.2   185.6  4814.2   185.9  4824.2   185.7  4834.2   185.2  4854.2   183.7
  4864.2   182.6  4874.2     181  4884.2   178.7  4894.2   176.1  4942.3  169.86
  4995.5  159.52  4997.5  159.05  5001.6  158.68  5002.9   159.1  5004.6  159.49
    5044   170.6  5073.1  169.93  5077.8  169.82  5104.2   170.7  5164.2   170.8
  5194.2   170.2  5300.4   171.8
#Mann= 4 ,-1 , 0
  4784.2     .07       0  4942.3     .04       0    5044     .15       0
  5300.4      .2       0
Bank Sta=4942.3,5044
XS Rating Curve= 0
Exp/Cntr=.3,.1

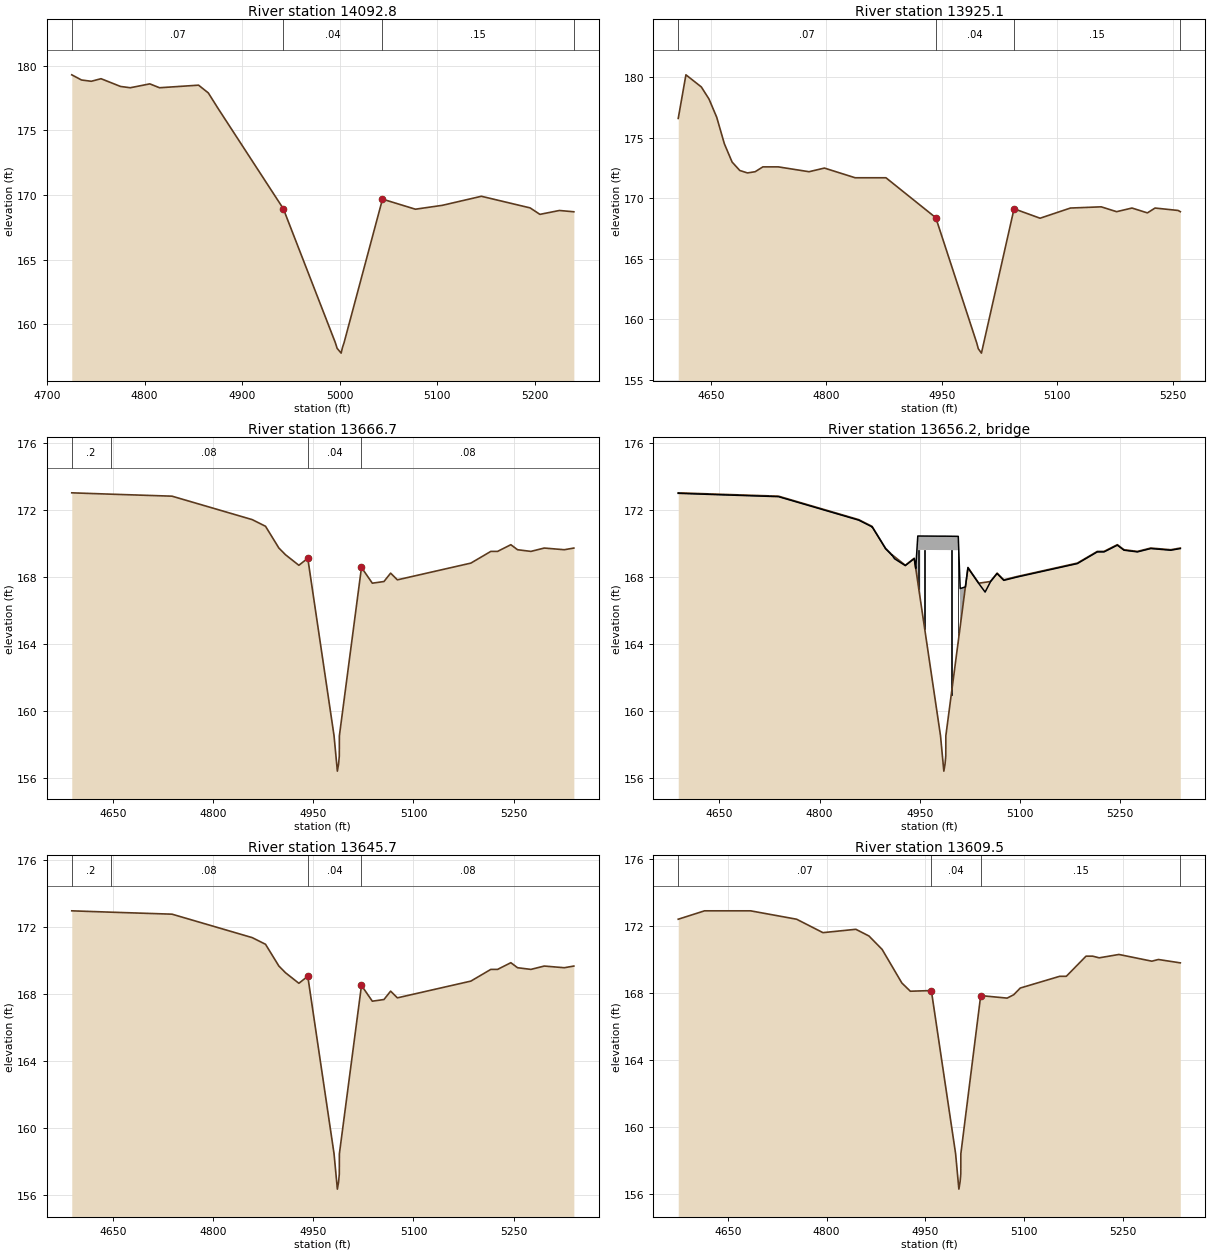
Type RM Length L Ch R = 1 ,14092.8 ,171.16,167.7,164.13
BEGIN DESCRIPTION:
Cross Section XS40
END DESCRIPTION:
XS GIS Cut Line= 2
    3039563.1945   13966566.8602     3039616.077   13966054.7342
#Sta/Elev= 26
  4725.4   179.3  4735.4   178.9  4745.4   178.8  4755.4     179  4775.4   178.4
  4785.4   178.3  4805.4   178.6  4815.4   178.3  4855.4   178.5  4865.4   177.9
  4875.4   176.7  4942.3  168.94  4995.5   158.6  4997.5  158.13  5001.6  157.76
  5002.9  158.18  5004.6  158.57    5044  169.68  5077.7   168.9  5077.8   168.9
  5105.4   169.2  5145.4   169.9  5195.4     169  5205.4   168.5  5225.4   168.8
  5240.2   168.7
#Mann= 4 ,-1 , 0
  4725.4     .07       0  4942.3     .04       0    5044     .15       0
  5240.2      .2       0
Bank Sta=4942.3,5044
XS Rating Curve= 0
Exp/Cntr=.3,.1

Type RM Length L Ch R = 1 ,13925.1 ,212.03,258.4,221.33
BEGIN DESCRIPTION:
Cross Section XS39.5
END DESCRIPTION:
XS GIS Cut Line= 3
     3039760.867   13966694.0585    3039753.2676   13966414.3991
    3039771.5062   13966042.0265
#Sta/Elev= 30
  4607.5   176.6  4617.5   180.2  4637.5   179.2  4647.5   178.2  4657.5   176.7
  4667.5   174.5  4677.5     173  4687.5   172.3  4697.5   172.1  4707.5   172.2
  4717.5   172.6  4737.5   172.6  4777.5   172.2  4797.5   172.5  4837.5   171.7
  4877.5   171.7  4942.3   168.4  4995.5  158.06  4997.5  157.59  5001.6  157.22
    5044  169.14  5077.8  168.36  5117.3   169.2  5157.3   169.3  5177.3   168.9
  5197.3   169.2  5217.3   168.8  5227.3   169.2  5257.3     169  5260.1   168.9
#Mann= 4 ,-1 , 0
  4607.5     .07       0  4942.3     .04       0    5044     .15       0
  5260.1      .2       0
Bank Sta=4942.3,5044
XS Rating Curve= 0
Exp/Cntr=.5,.3

Type RM Length L Ch R = 1 ,13666.7 ,21,21,21
BEGIN DESCRIPTION:
Upstream Section of Bridge/Culvert/Weir
END DESCRIPTION:
XS GIS Cut Line= 2
    3039969.9956   13966722.8553    3040056.8208   13965976.1583
#Sta/Elev= 28
  4588.4  173.03  4646.4  172.95  4738.5  172.83  4858.5  171.43  4878.5  171.03
  4898.5  169.73  4908.4  169.33  4928.4   168.7 4941.76  169.12 4981.06  158.52
 4986.06   156.4 4987.86  156.82 4988.96  157.31 4989.06  158.51 5022.16  168.57
  5038.4  167.63  5055.8  167.73  5065.8  168.23  5075.9  167.83  5185.9  168.83
  5215.8  169.53  5225.9  169.53  5245.8  169.93  5255.8  169.63  5275.8  169.53
  5295.8  169.73  5325.8  169.63  5340.1  169.73
#Mann= 4 ,-1 , 0
  4588.4      .2       0  4646.4     .08       0 4941.76     .04       0
 5022.16     .08       0
#XS Ineff= 2 , 0
       0 4931.76  168.68 5032.16       0   167.1
Permanent Ineff=
       F       F
Bank Sta=4941.76,5022.16
XS Rating Curve= 0
Exp/Cntr=.5,.3

Type RM Length L Ch R = 3 ,13656.2 ,,,
BEGIN DESCRIPTION:
12" Pipeline crossing
END DESCRIPTION:
Bridge Culvert--1,0,-1,-1, 0
Deck Dist Width WeirC Skew NumUp NumDn MinLoCord MaxHiCord MaxSubmerge Is_Ogee
10,1,2.6,0, 61, 61, , , .95, 0, 1,1,,
  4588.4  4588.5  4646.4  4738.4  4738.5  4858.4  4858.5  4878.4  4878.5  4898.4
  4898.5  4908.4  4908.5 4912.26  4928.4  4938.5 4941.76 4943.76 4943.87 4943.96
 4947.06 4981.06 4986.06 4987.86 4988.96 4989.06 5007.66 5010.35 5010.46 5010.56
  5018.4 5022.16  5028.5  5038.4 5047.86  5055.8  5055.9  5065.8  5065.9  5075.8
  5075.9  5095.8  5095.9  5185.8  5185.9  5215.8  5215.9  5225.8  5225.9  5245.8
  5245.9  5255.8  5255.9  5275.8  5275.9  5295.8  5295.9  5325.8  5325.9    5340
  5340.1
     173     173  172.92   172.8   172.8   171.4   171.4     171  171.01  169.72
   169.7   169.3  169.31  169.09  168.68     169   169.1  168.56  168.53  168.51
  170.45  170.44  170.44  170.44  170.44  170.44  170.43   167.5  167.38  167.31
  167.41  168.55  168.18  167.61   167.1  167.71  167.72  168.21   168.2   167.8
   167.8     168     168   168.8   168.8   169.5   169.5   169.5   169.5   169.9
   169.9   169.6   169.6   169.5   169.5   169.7   169.7   169.6   169.6   169.7
   169.7
                                                                                
                                                                                
  169.62  169.61  169.61  169.61  169.61  169.61   169.6  166.67  164.98  165.01
                                                                                
                                                                                
                                                                                
        
  4588.4  4588.5  4646.4  4738.4  4738.5  4858.4  4858.5  4878.4  4878.5  4898.4
  4898.5  4908.4  4908.5 4912.26  4928.4  4938.5 4941.76 4943.76 4943.87 4943.96
 4947.06 4981.06 4986.06 4987.86 4988.96 4989.06 5007.66 5010.35 5010.46 5010.56
  5018.4 5022.16  5028.5  5038.4 5047.86  5055.8  5055.9  5065.8  5065.9  5075.8
  5075.9  5095.8  5095.9  5185.8  5185.9  5215.8  5215.9  5225.8  5225.9  5245.8
  5245.9  5255.8  5255.9  5275.8  5275.9  5295.8  5295.9  5325.8  5325.9    5340
  5340.1
     173     173  172.92   172.8   172.8   171.4   171.4     171  171.01  169.72
   169.7   169.3  169.31  169.09  168.68     169   169.1  168.56  168.53  168.51
  170.45  170.44  170.44  170.44  170.44  170.44  170.43   167.5  167.38  167.31
  167.41  168.55  168.18  167.61   167.1  167.71  167.72  168.21   168.2   167.8
   167.8     168     168   168.8   168.8   169.5   169.5   169.5   169.5   169.9
   169.9   169.6   169.6   169.5   169.5   169.7   169.7   169.6   169.6   169.7
   169.7
                                                                                
                                                                                
  169.62  169.61  169.61  169.61  169.61  169.61   169.6  166.67  164.98
                                                                                
                                                                                
                                                                                
        
Pier Skew, UpSta & Num, DnSta & Num=  ,4948.5, 2 ,4948.5, 2 , 0 , 0 , 0 ,,
       1       1
  166.15  170.62
       1       1
  166.15  170.62
Pier Skew, UpSta & Num, DnSta & Num=  ,4957.4, 2 ,4957.4, 2 , 0 , 0 , 0 ,,
       1       1
  163.75  170.62
       1       1
  163.75  170.62
Pier Skew, UpSta & Num, DnSta & Num=  ,4997.1, 2 ,4997.1, 2 , 0 , 0 , 0 ,,
       1       1
  159.76  170.61
       1       1
  159.76  170.61
Pier Skew, UpSta & Num, DnSta & Num=  ,5007.4, 2 ,5007.4, 2 , 0 , 0 , 0 ,,
       1       1
  162.89   170.6
       1       1
  162.89   170.6
BR Coef= 1 , 1 , 1 ,1.25, 0 ,,,.8,0,2,0,
WSPro=,,,, 1 ,,,, 0 ,,,, 0 ,,,,-1 ,-1 ,-1 , 0 , 0 , 0 , 0 , 0
BR U #Sta/Elev= 59
  4588.4  173.03  4588.5  173.03  4646.4  172.95  4738.4  172.83  4738.5  172.83
  4858.4  171.43  4858.5  171.43  4878.4  171.03  4878.5  171.03  4898.4  169.74
  4898.5  169.73  4908.4  169.33  4908.5  169.33  4928.4   168.7  4938.5  169.02
 4941.76  169.12 4943.76  168.58 4943.87  168.55 4943.96  168.53 4947.06  167.69
 4981.06  158.52 4986.06   156.4 4987.86  156.82 4988.96  157.31 4989.06  158.51
 5007.66  164.16 5010.35  164.98 5010.46  165.01 5010.56  165.04  5018.4  167.43
 5022.16  168.57  5028.5   168.2  5038.4  167.63  5055.8  167.73  5055.9  167.74
  5065.8  168.23  5065.9  168.23  5075.8  167.83  5075.9  167.83  5095.8  168.03
  5095.9  168.03  5185.8  168.83  5185.9  168.83  5215.8  169.53  5215.9  169.53
  5225.8  169.53  5225.9  169.53  5245.8  169.93  5245.9  169.93  5255.8  169.63
  5255.9  169.63  5275.8  169.53  5275.9  169.53  5295.8  169.73  5295.9  169.73
  5325.8  169.63  5325.9  169.63    5340  169.73  5340.1  169.73
BR U #Mann= 4
  4588.4      .2  4646.4     .08 4941.76    .035 5022.16     .08
BR D #Sta/Elev= 59
  4588.4  172.99  4588.5  172.99  4646.4  172.91  4738.4  172.79  4738.5  172.79
  4858.4  171.39  4858.5  171.39  4878.4  170.99  4878.5  170.99  4898.4   169.7
  4898.5  169.69  4908.4  169.29  4908.5  169.29  4928.4  168.66  4938.5  168.98
 4941.76  169.08 4943.76  168.54 4943.87  168.51 4943.96  168.49 4947.06  167.65
 4981.06  158.48 4986.06  156.36 4987.86  156.78 4988.96  157.27 4989.06  158.47
 5007.66  164.12 5010.35  164.94 5010.46  164.97 5010.56     165  5018.4  167.39
 5022.16  168.53  5028.5  168.16  5038.4  167.59  5055.8  167.69  5055.9   167.7
  5065.8  168.19  5065.9  168.19  5075.8  167.79  5075.9  167.79  5095.8  167.99
  5095.9  167.99  5185.8  168.79  5185.9  168.79  5215.8  169.49  5215.9  169.49
  5225.8  169.49  5225.9  169.49  5245.8  169.89  5245.9  169.89  5255.8  169.59
  5255.9  169.59  5275.8  169.49  5275.9  169.49  5295.8  169.69  5295.9  169.69
  5325.8  169.59  5325.9  169.59    5340  169.69  5340.1  169.69
BR D #Mann= 4
  4588.4      .2  4646.4     .08 4941.76    .035 5022.16     .08
BC Design=,, 0 ,, 0 ,,,,,,

Type RM Length L Ch R = 1 ,13645.7 ,36.2,36.2,36.2
BEGIN DESCRIPTION:
Downstream Section of Bridge/Culvert/Weir
END DESCRIPTION:
XS GIS Cut Line= 3
    3039988.2922   13966723.2205    3040046.8053   13966269.0478
    3040080.1594   13965977.1994
#Sta/Elev= 28
  4588.4  172.99  4646.4  172.91  4738.5  172.79  4858.5  171.39  4878.5  170.99
  4898.5  169.69  4908.4  169.29  4928.4  168.66 4941.76  169.08 4981.06  158.48
 4986.06  156.36 4987.86  156.78 4988.96  157.27 4989.06  158.47 5022.16  168.53
  5038.4  167.59  5055.8  167.69  5065.8  168.19  5075.9  167.79  5185.9  168.79
  5215.8  169.49  5225.9  169.49  5245.8  169.89  5255.8  169.59  5275.8  169.49
  5295.8  169.69  5325.8  169.59  5340.1  169.69
#Mann= 4 ,-1 , 0
  4588.4      .2       0  4646.4     .08       0 4941.76     .04       0
 5022.16     .08       0
#XS Ineff= 2 , 0
       0 4935.09  168.68 5028.83       0   167.1
Permanent Ineff=
       F       F
Bank Sta=4941.76,5022.16
XS Rating Curve= 0
Exp/Cntr=.5,.3

Type RM Length L Ch R = 1 ,13609.5 ,222.83,260.3,288.74
BEGIN DESCRIPTION:
Cross Section XS39
END DESCRIPTION:
XS GIS Cut Line= 2
    3040008.5214   13966733.8578    3040125.4198   13965979.5852
#Sta/Elev= 29
  4574.4   172.4  4614.4   172.9  4684.4   172.9  4754.4   172.4  4794.4   171.6
  4844.4   171.8  4864.4   171.4  4884.4   170.6  4914.4   168.6 4927.26  168.11
  4959.2  168.15 4996.06  158.44 5001.06  156.32 5002.86  156.74 5003.96  157.23
 5004.06  158.43 5034.23  167.85  5074.4   167.7  5084.4   167.9  5094.4   168.3
  5154.4     169  5164.4     169  5194.4   170.2  5204.4   170.2  5214.4   170.1
  5244.4   170.3  5294.4   169.9  5304.4     170  5337.7   169.8
#Mann= 4 ,-1 , 0
  4574.4     .07       0  4959.2     .04       0 5034.23     .15       0
  5337.7      .2       0
Bank Sta=4959.2,5034.23
XS Rating Curve= 0
Exp/Cntr=.3,.1