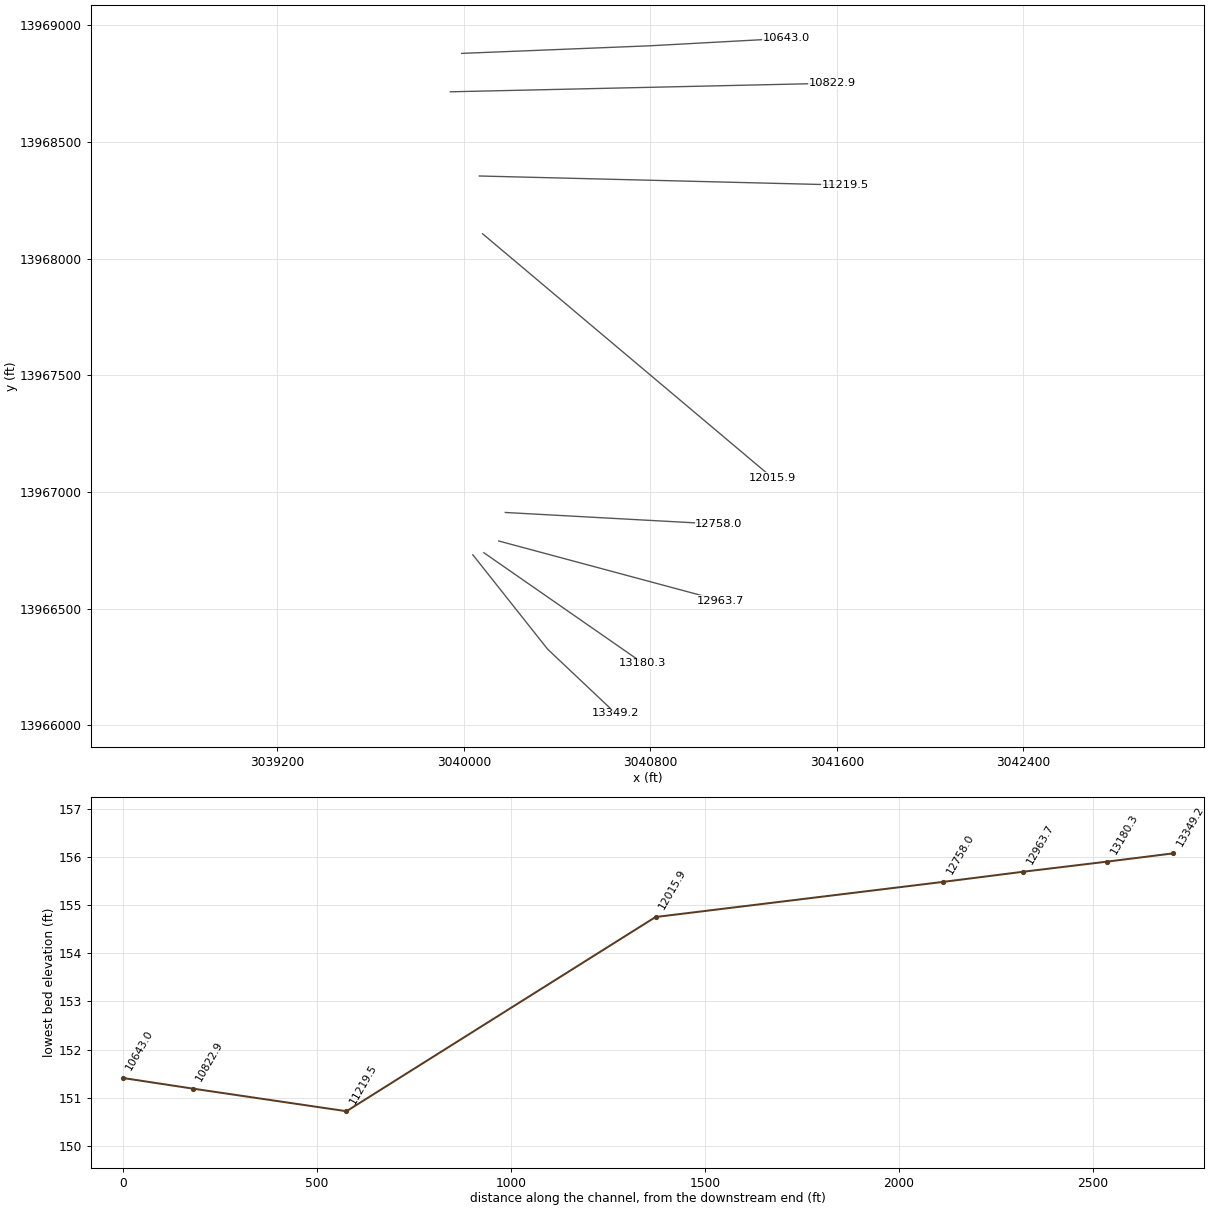
HEC-RAS study J131-00-00.PRJ: J131-00-00

--- J131-00-00.g01 (geometry) --- (continued)

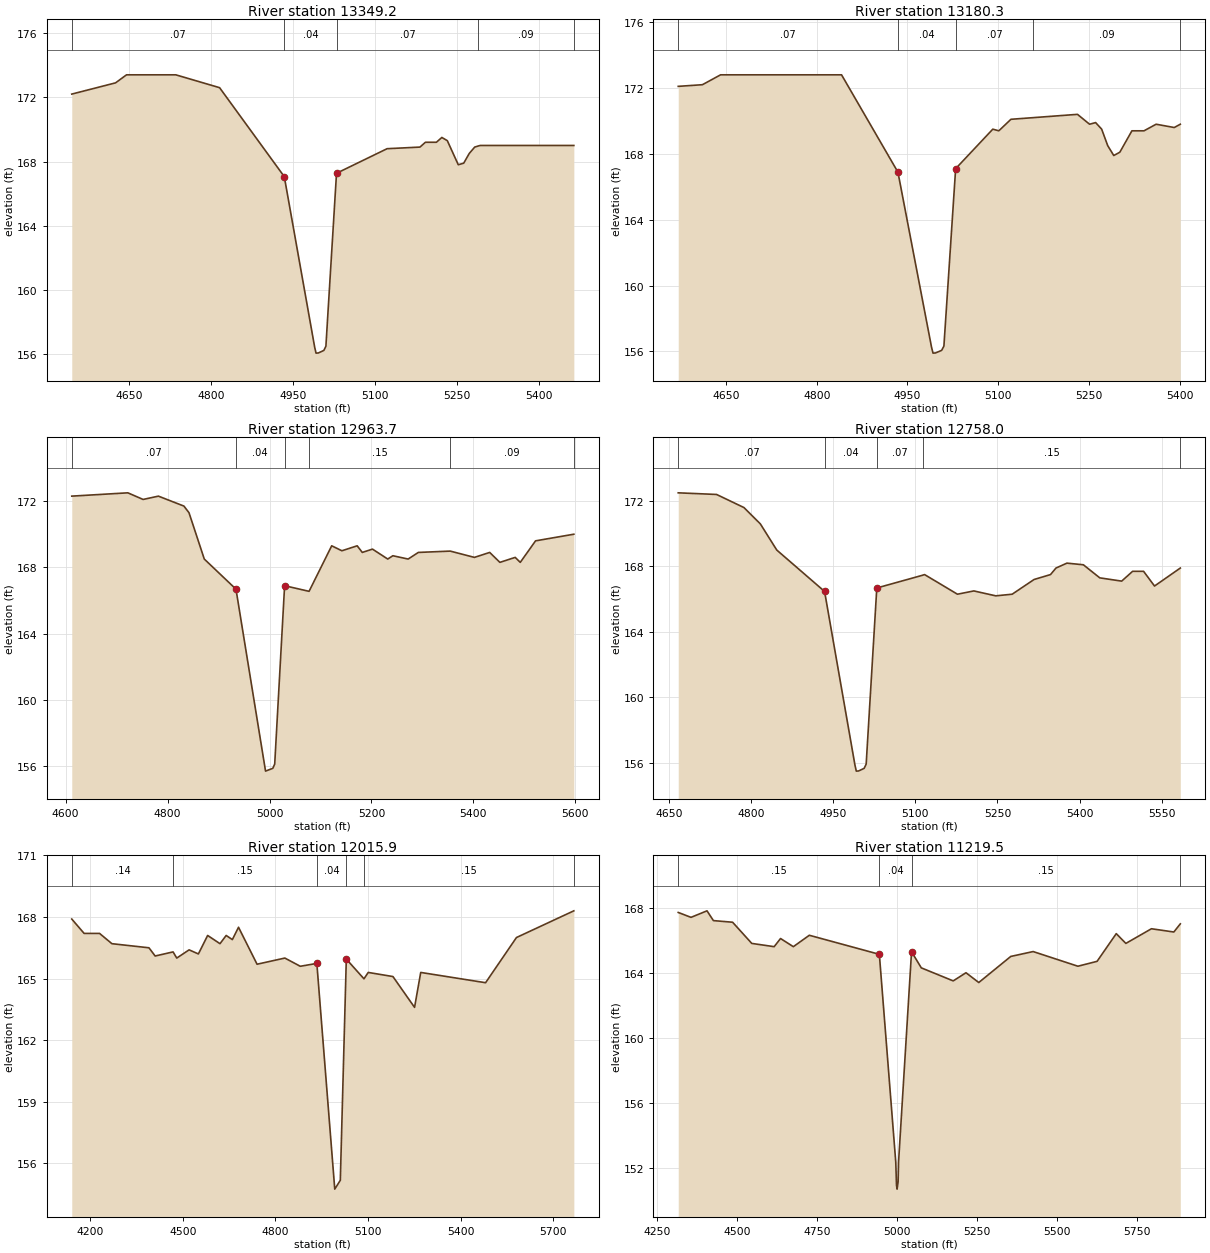
Type RM Length L Ch R = 1 ,13349.2 ,148.29,168.9,184.51
BEGIN DESCRIPTION:
Cross Section XS38
END DESCRIPTION:
XS GIS Cut Line= 3
    3040039.0066   13966730.5358     3040359.703   13966326.2456
    3040651.5215   13966051.1458
#Sta/Elev= 25
    4546   172.2    4626   172.9    4646   173.4    4736   173.4    4816   172.6
  4934.2  167.06  4989.8  156.42  4992.2  156.07  4996.4  156.08  5006.5  156.24
  5010.2   156.5  5029.6  167.27    5122   168.8    5182   168.9    5192   169.2
    5212   169.2    5222   169.5    5232   169.3    5252   167.8    5262   167.9
    5272   168.5    5282   168.9  5288.6  168.97    5292     169  5463.1     169
#Mann= 5 ,-1 , 0
    4546     .07       0  4934.2     .04       0  5029.6     .07       0
  5288.6     .09       0  5463.1      .2       0
#Block Obstruct= 2 , 0
       0                    5230       0   168.5
Bank Sta=4934.2,5029.6
XS Rating Curve= 0
Exp/Cntr=.3,.1

Type RM Length L Ch R = 1 ,13180.3 ,190.09,216.6,238.54
BEGIN DESCRIPTION:
Cross Section XS37
END DESCRIPTION:
XS GIS Cut Line= 2
    3040086.4536   13966739.4244    3040768.3606   13966266.2645
#Sta/Elev= 27
    4571   172.1    4611   172.2    4641   172.8    4841   172.8  4934.2  166.89
  4989.8  156.25  4992.2   155.9  4996.4  155.91  5006.5  156.07  5010.2  156.33
  5029.6   167.1    5091   169.5    5101   169.4    5121   170.1    5158   170.2
    5231   170.4    5251   169.8    5261   169.9    5271   169.5    5281   168.5
    5291   167.9    5301   168.1    5321   169.4    5341   169.4    5361   169.8
    5391   169.6    5401   169.8
#Mann= 5 ,-1 , 0
    4571     .07       0  4934.2     .04       0  5029.6     .07       0
    5158     .09       0    5401      .2       0
#Block Obstruct= 2 , 0
       0                    5270       0   168.5
Bank Sta=4934.2,5029.6
XS Rating Curve= 0
Exp/Cntr=.3,.1

Type RM Length L Ch R = 1 ,12963.7 ,187.2,205.7,211.52
BEGIN DESCRIPTION:
Cross Section XS36.5
END DESCRIPTION:
XS GIS Cut Line= 2
    3040149.9584   13966789.8115    3041101.4084   13966534.4703
#Sta/Elev= 30
    4612   172.3    4722   172.5    4752   172.1    4782   172.3    4832   171.7
    4842   171.3    4872   168.5  4934.2  166.68  4992.2  155.69  5006.5  155.86
  5010.2  156.12  5029.6  166.89  5077.6  166.55    5122   169.3    5142     169
    5172   169.3    5182   168.9    5202   169.1    5232   168.5    5242   168.7
    5272   168.5    5292   168.9  5354.6  168.98    5402   168.6    5432   168.9
    5452   168.3    5482   168.6    5492   168.3    5522   169.6  5597.1     170
#Mann= 6 ,-1 , 0
    4612     .07       0  4934.2     .04       0  5029.6     .07       0
  5077.6     .15       0  5354.6     .09       0  5597.1      .2       0
Bank Sta=4934.2,5029.6
XS Rating Curve= 0
Exp/Cntr=.3,.1

Type RM Length L Ch R = 1 ,12758.0 ,774.6,742.1,664.61
BEGIN DESCRIPTION:
Cross Section XS36
END DESCRIPTION:
XS GIS Cut Line= 2
    3040178.3023   13966911.9886    3041094.0059   13966861.8893
#Sta/Elev= 30
  4666.9   172.5  4736.9   172.4  4786.9   171.6  4816.9   170.6  4846.9     169
  4934.2  166.47  4989.8  155.83  4992.2  155.48  4996.4  155.49  5006.5  155.65
  5010.2  155.91  5029.6  166.68  5106.9   167.4  5113.2  167.46  5116.9   167.5
  5176.9   166.3  5206.9   166.5  5246.9   166.2  5276.9   166.3  5316.9   167.2
  5346.9   167.5  5356.9   167.9  5376.9   168.2  5406.9   168.1  5436.9   167.3
  5476.9   167.1  5496.9   167.7  5516.9   167.7  5536.9   166.8    5584   167.9
#Mann= 5 ,-1 , 0
  4666.9     .07       0  4934.2     .04       0  5029.6     .07       0
  5113.2     .15       0    5584      .2       0
#Block Obstruct= 2 , 0
       0                    5160       0   166.5
Bank Sta=4934.2,5029.6
XS Rating Curve= 0
Exp/Cntr=.3,.1

Type RM Length L Ch R = 1 ,12015.9 ,751.63,796.4,835.79
BEGIN DESCRIPTION:
Cross Section XS35
END DESCRIPTION:
XS GIS Cut Line= 2
    3040080.8871   13968106.0215    3041325.0192   13967059.5031
#Sta/Elev= 30
  4140.6   167.9  4180.6   167.2  4230.6   167.2  4270.6   166.7  4390.6   166.5
  4410.6   166.1  4468.6   166.3  4480.6     166  4520.6   166.4  4550.6   166.2
  4580.6   167.1  4620.6   166.7  4640.6   167.1  4660.6   166.9  4680.6   167.5
  4740.6   165.7  4830.6     166  4880.6   165.6  4934.2  165.74  4992.2  154.75
  5010.2  155.18  5029.6  165.95  5086.8  164.99  5100.6   165.3  5180.6   165.1
  5250.6   163.6  5270.6   165.3  5480.6   164.8  5580.6     167  5766.4   168.3
#Mann= 6 ,-1 , 0
  4140.6     .14       0  4468.6     .15       0  4934.2     .04       0
  5029.6     .08       0  5086.8     .15       0  5766.4      .2       0
Bank Sta=4934.2,5029.6
XS Rating Curve= 0
Exp/Cntr=.3,.1

Type RM Length L Ch R = 1 ,11219.5 ,392.93,396.6,402.26
BEGIN DESCRIPTION:
Cross Section XS34
END DESCRIPTION:
XS GIS Cut Line= 2
    3040066.9706   13968353.7346    3041636.7481   13968314.7685
#Sta/Elev= 30
  4315.2   167.7  4355.2   167.4  4405.2   167.8  4425.2   167.2  4485.2   167.1
  4545.2   165.8  4615.2   165.6  4635.2   166.1  4675.2   165.6  4725.2   166.3
  4944.2  165.13  4995.6  152.37  4997.8  150.98  4999.7  150.72  5002.9  151.17
  5004.3  152.38  5044.9  165.29  5075.4   164.3  5175.2   163.5  5215.2     164
  5255.2   163.4  5355.2     165  5425.2   165.3  5565.2   164.4  5625.2   164.7
  5685.2   166.4  5715.2   165.8  5795.2   166.7  5865.2   166.5  5885.5     167
#Mann= 4 ,-1 , 0
  4315.2     .15       0  4944.2     .04       0  5044.9     .15       0
  5885.5      .2       0
Bank Sta=4944.2,5044.9
XS Rating Curve= 0
Exp/Cntr=.3,.1

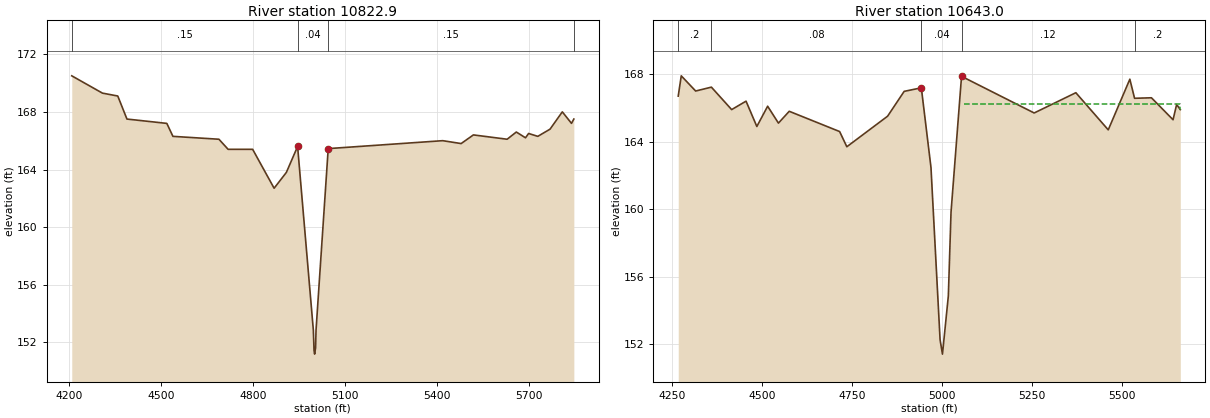
Type RM Length L Ch R = 1 ,10822.9 ,173.45,179.9,177.18
BEGIN DESCRIPTION:
Cross Section XS33
END DESCRIPTION:
XS GIS Cut Line= 2
      3039942.53     13968714.51    3041579.7122   13968751.1975
#Sta/Elev= 30
  4207.6   170.5  4307.6   169.3  4357.6   169.1  4387.6   167.5  4517.6   167.2
  4537.6   166.3  4687.6   166.1  4717.6   165.4  4797.6   165.4  4867.6   162.7
  4907.6   163.8  4944.2   165.6  4995.6  152.84  4997.8  151.45  4999.7  151.19
  5002.9  151.64  5004.3  152.85 5044.04  165.45  5417.6     166  5477.6   165.8
  5517.6   166.4  5627.6   166.1  5657.6   166.6  5687.6   166.2  5697.6   166.5
  5727.6   166.3  5767.6   166.8  5807.6     168  5837.6   167.2  5845.2   167.5
#Mann= 4 ,-1 , 0
  4207.6     .15       0  4944.2     .04       0  5044.9     .15       0
  5845.2      .2       0
Bank Sta=4944.2,5044.04
XS Rating Curve= 0
Exp/Cntr=.5,.3

Type RM Length L Ch R = 1 ,10643.0 ,58,58,58
BEGIN DESCRIPTION:
Upstream Section of Bridge/Culvert/Weir
END DESCRIPTION:
XS GIS Cut Line= 3
    3039991.3702   13968879.0869    3040797.7229   13968911.6199
    3041384.7202   13968943.5964
#Sta/Elev= 30
  4267.1  166.69  4275.5  167.89  4315.5  166.99  4359.2  167.22  4415.5  165.89
  4455.5  166.39  4485.5  164.89  4515.5  166.09  4545.5  165.09  4575.5  165.79
  4715.5  164.59  4735.5  163.69  4848.8   165.5  4894.8  166.97  4942.5  167.18
  4969.3  162.46  4994.6  152.26  5001.2  151.41  5017.5  154.85    5025  159.82
  5054.2  167.86    5256  165.69  5371.8  166.89  5461.8  164.69  5521.8  167.69
  5534.9  166.56  5581.8  166.59  5641.8  165.29  5651.8  166.19    5662  165.89
#Mann= 5 ,-1 , 0
  4267.1      .2       0  4359.2     .08       0  4942.5     .04       0
  5054.2     .12       0  5534.9      .2       0
#XS Ineff= 2 , 0
       0  4941.1   165.7  5060.2       0   166.2
Permanent Ineff=
       F       F
#Block Obstruct= 2 , 0
       0                    5350       0     166
Bank Sta=4942.5,5054.2
XS Rating Curve= 0
Exp/Cntr=.5,.3