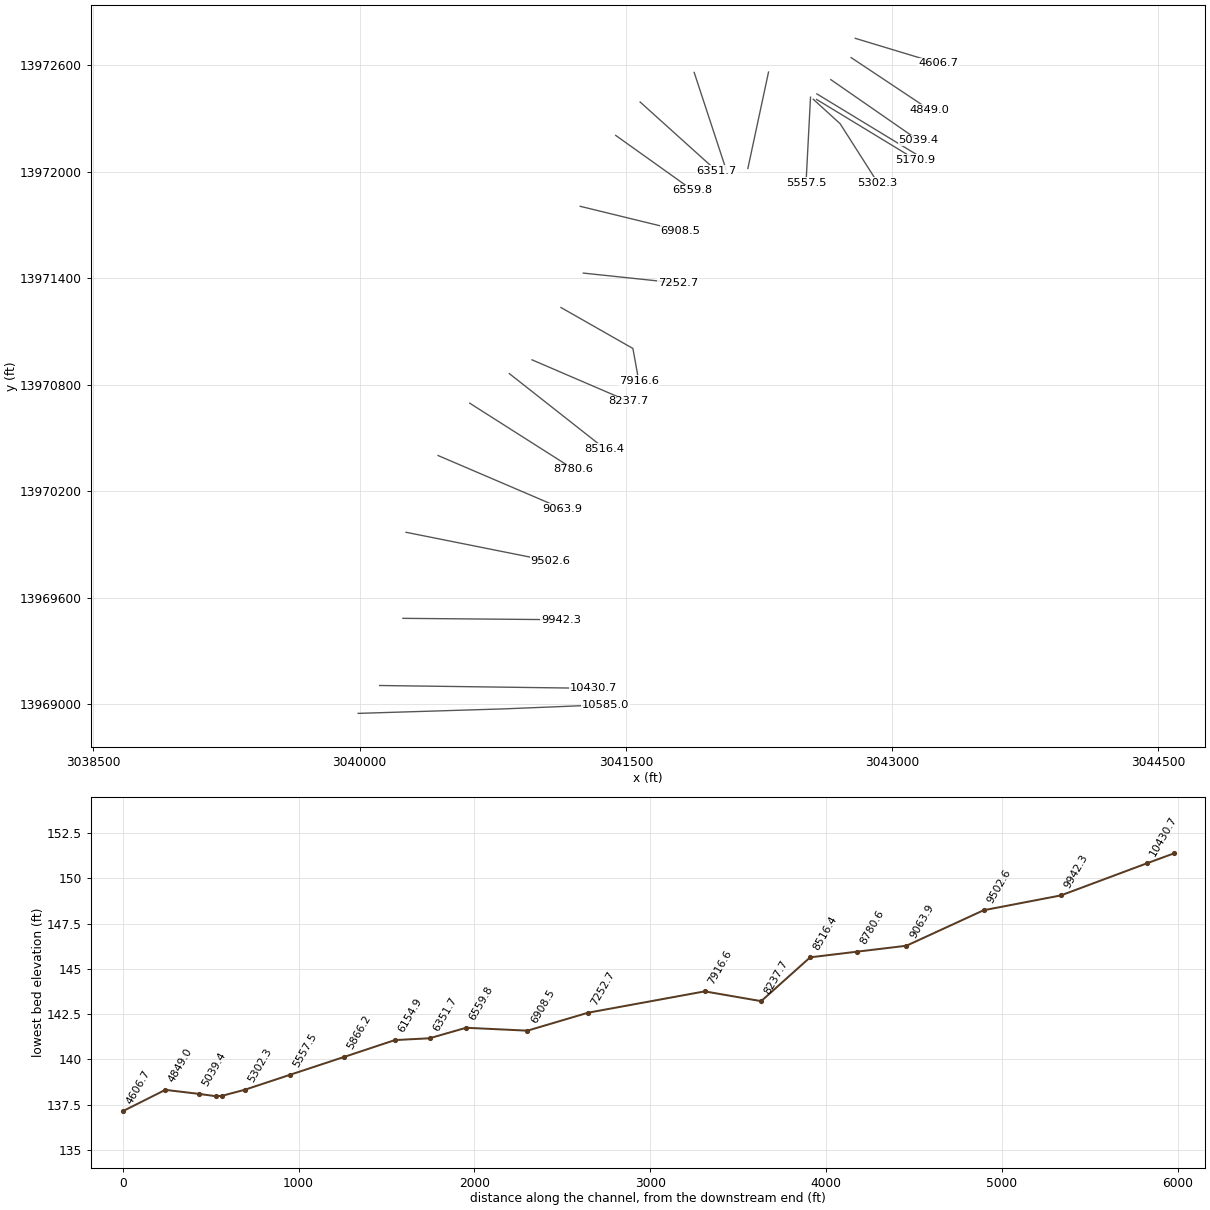
HEC-RAS study J131-00-00.PRJ: J131-00-00

--- J131-00-00.g01 (geometry) --- (continued)

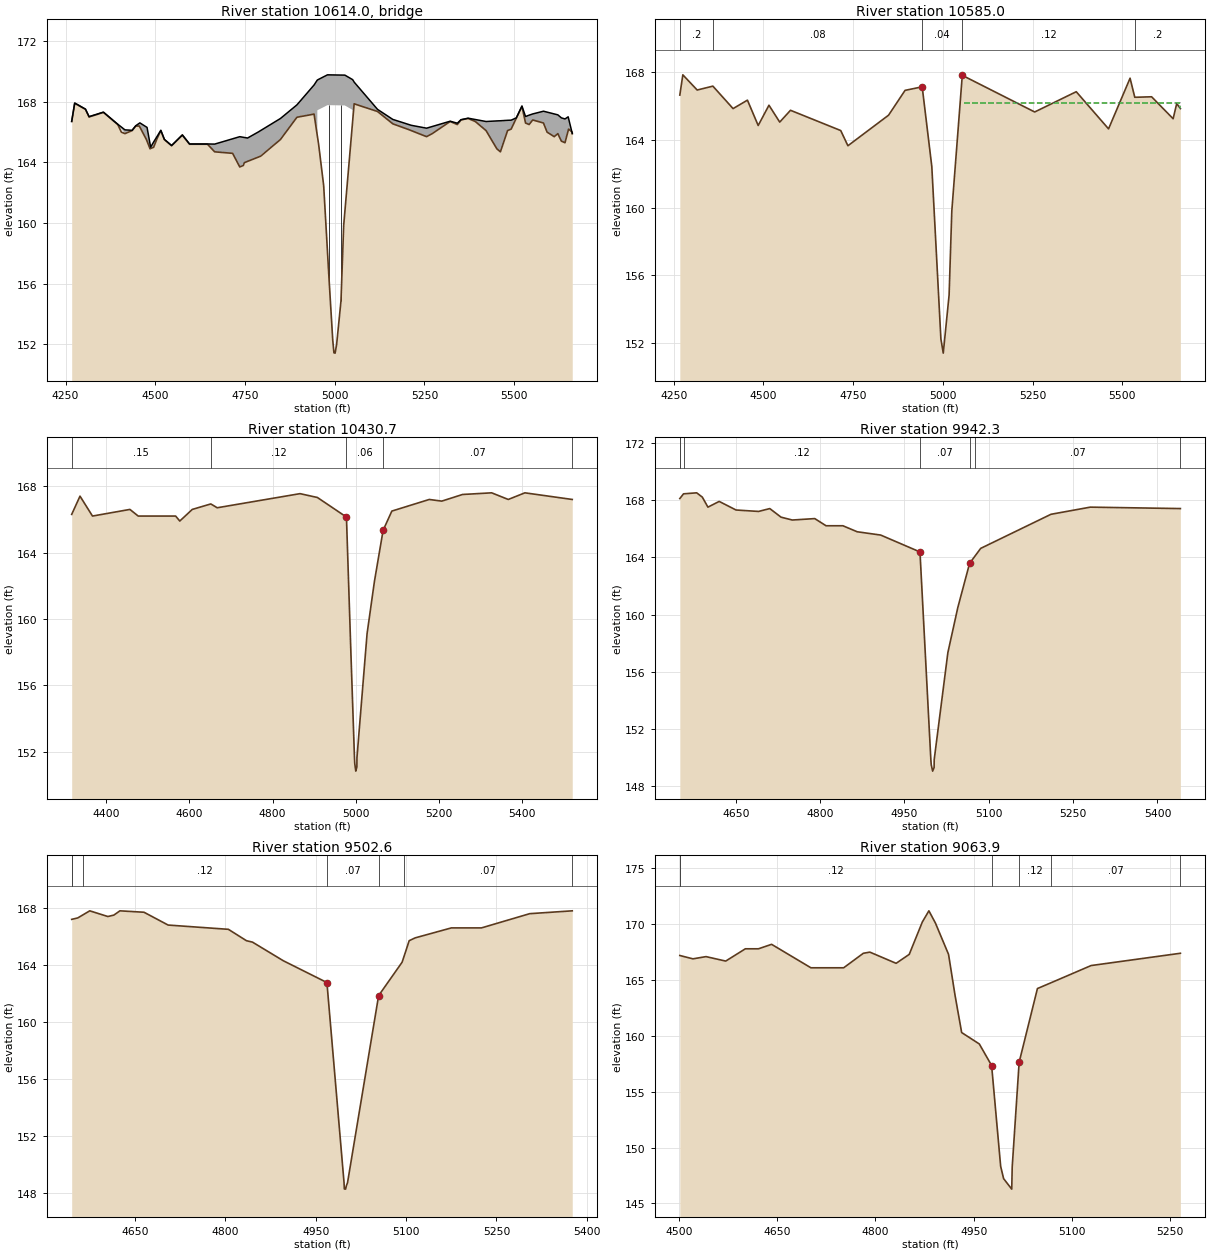
Type RM Length L Ch R = 3 ,10614.0 ,,,
BEGIN DESCRIPTION:
ZION ROAD
Structure ID: J131-00-00-03
END DESCRIPTION:
Bridge Culvert--1,0,-1,-1, 0
Deck Dist Width WeirC Skew NumUp NumDn MinLoCord MaxHiCord MaxSubmerge Is_Ogee
10,38,2.6,0, 60, 60, , , .95, 0, 1,1,,
  4267.1  4275.5  4305.5  4315.5  4355.5  4395.5  4415.5  4435.5  4445.5  4457.1
  4477.1  4487.1  4495.5  4515.5  4525.5  4545.5  4575.5  4595.5  4645.5  4665.5
  4715.5  4735.5  4757.1  4787.1  4848.8  4894.8  4942.5 4951.61  4951.7  4979.9
  5028.4 5050.19  5050.3  5054.2  5119.4  5161.8  5213.4    5256  5321.8  5341.8
  5351.8  5371.8  5421.8  5451.8  5461.8  5481.8  5491.8  5506.1  5521.8  5531.8
  5541.8  5551.8  5581.8  5591.8  5611.8  5621.8  5631.8  5641.8  5650.6    5662
   166.7  167.91  167.51  167.01  167.31  166.51  166.14  166.11  166.41   166.6
   166.3     165  165.34  166.11  165.51  165.11  165.81  165.21  165.21   165.2
  165.55  165.69   165.6     166  166.89  167.79   169.1  169.43  169.43  169.77
  169.75  169.45  169.45  169.29  167.49  166.83  166.44  166.25  166.71  166.58
  166.81  166.91  166.69  166.73  166.74  166.77  166.78  166.93  167.71  167.02
  167.11  167.19  167.37  167.31  167.19  167.13  166.93  166.86     167   165.9
   166.7   167.9   167.5     167   167.3   166.5   165.9   166.1   166.4  166.33
   165.4  164.92     165   166.1   165.5   165.1   165.8   165.2   165.2   164.7
   164.6   163.7  164.07  164.35  165.51  166.98  167.19  165.76  167.43  167.77
  167.75  167.45   166.8  167.87  167.36  166.55   166.1   165.7   166.7   166.5
   166.8   166.9   166.1   164.9   164.7   166.1   166.2  166.92   167.7   166.6
   166.5   166.8   166.6     166   165.7   165.9   165.4   165.3  166.09   165.9
  4267.1  4275.5  4305.5  4315.5  4355.5  4395.5  4415.5  4435.5  4445.5  4457.1
  4477.1  4487.1  4495.5  4515.5  4525.5  4545.5  4575.5  4595.5  4645.5  4665.5
  4715.5  4735.5  4757.1  4787.1  4848.8  4894.8  4942.5 4951.61  4951.7  4979.9
  5028.4 5050.19  5050.3  5054.2  5119.4  5161.8  5213.4    5256  5321.8  5341.8
  5351.8  5371.8  5421.8  5451.8  5461.8  5481.8  5491.8  5506.1  5521.8  5531.8
  5541.8  5551.8  5581.8  5591.8  5611.8  5621.8  5631.8  5641.8  5650.6    5662
   166.7  167.91  167.51  167.01  167.31  166.51  166.14  166.11  166.41   166.6
   166.3     165  165.34  166.11  165.51  165.11  165.81  165.21  165.21   165.2
  165.55  165.69   165.6     166  166.89  167.79   169.1  169.43  169.43  169.77
  169.75  169.45  169.45  169.29  167.49  166.83  166.44  166.25  166.71  166.58
  166.81  166.91  166.69  166.73  166.74  166.77  166.78  166.93  167.71  167.02
  167.11  167.19  167.37  167.31  167.19  167.13  166.93  166.86     167   165.9
   166.7   167.9   167.5     167   167.3   166.5   165.9   166.1   166.4  166.33
   165.4  164.92     165   166.1   165.5   165.1   165.8   165.2   165.2   164.7
   164.6   163.7  164.07  164.35  165.51  166.98  167.19  165.76  167.43  167.77
  167.75  167.45   166.8  167.87  167.36  166.55   166.1   165.7   166.7   166.5
   166.8   166.9   166.1   164.9   164.7   166.1   166.2  166.92   167.7   166.6
   166.5   166.8   166.6     166   165.7   165.9   165.4   165.3  166.09   165.9
Pier Skew, UpSta & Num, DnSta & Num=  ,4984.7, 2 ,4984.7, 2 , 0 , 0 , 0 ,,
     1.3     1.3
  154.88  168.77
     1.3     1.3
  154.88  168.77
Pier Skew, UpSta & Num, DnSta & Num=  ,5017.5, 2 ,5017.5, 2 , 0 , 0 , 0 ,,
     1.3     1.3
  153.71  168.75
     1.3     1.3
  153.71  168.75
Abutment Skew #Up #Dn= , 2 , 2
  4951.5  4994.6
  167.43  152.27
  4951.5  4994.6
  167.43  152.27
Abutment Skew #Up #Dn= , 2 , 2
  5005.5 5050.39
  152.02  167.45
  5005.5 5050.39
  152.02  167.45
BR Coef= 1 , 1 , 1 ,1.25, 0 ,,,.8,0,2,0,
WSPro=,,,, 1 ,,,, 0 ,,,, 0 ,,,,-1 ,-1 ,-1 , 0 , 0 , 0 , 0 , 0
BR U #Sta/Elev= 125
  4267.1  166.69  4275.5  167.89  4287.1  167.74  4305.5  167.49  4307.1  167.41
  4315.5  166.99  4327.1  167.08  4337.1  167.15  4347.1  167.23  4355.5  167.29
  4359.2  167.22  4367.1  167.06  4395.5  166.49  4405.5  165.99  4415.5  165.89
  4435.5  166.09  4445.5  166.39  4447.1  166.39  4455.5  166.39  4457.1  166.32
  4475.5  165.49  4477.1  165.39  4485.5  164.89  4487.1  164.91  4495.5  164.99
  4497.1  165.09  4505.5  165.59  4507.1  165.67  4515.5  166.09  4517.1  165.99
  4525.5  165.49  4537.1  165.26  4545.5  165.09  4547.1  165.13  4557.1  165.36
  4575.5  165.79  4577.1  165.74  4587.1  165.44  4595.5  165.19  4597.1  165.19
  4607.1  165.19  4617.1  165.19  4627.1  165.19  4637.1  165.19  4645.5  165.19
  4665.5  164.69  4715.5  164.59  4735.5  163.69  4737.1  163.71  4745.5  163.79
  4748.1  163.97  4757.1  164.06  4787.1  164.34    4794  164.41  4817.1  164.87
  4827.1  165.07  4828.7   165.1  4848.8   165.5  4877.6  166.42  4894.8  166.97
  4931.7  167.13  4942.5  167.18  4951.4  165.78  4951.5  165.77 4951.61  165.75
  4951.7  165.74  4955.3  165.17  4969.3  162.46  4979.9   158.1  4984.7  156.12
  4994.5   152.3  4994.6  152.26  4997.9  151.43  5001.2  151.41  5005.4  151.99
  5005.5  152.01  5017.5  154.85    5025  159.82  5028.4  160.76 5050.19  166.76
  5050.3  166.79  5050.4  166.81  5050.5  166.84  5054.2  167.86  5070.3  167.73
  5118.3  167.36  5119.4  167.35  5161.8  166.54  5166.1   166.5    5207  166.15
  5213.4  166.09    5256  165.69  5266.1  165.82  5271.8  165.89  5286.1  166.12
  5321.8  166.69  5341.8  166.49  5351.8  166.79  5371.8  166.89  5391.8  166.69
  5421.8  166.09  5451.8  164.89  5461.8  164.69  5481.8  166.09  5491.8  166.19
  5506.1  166.91  5521.8  167.69  5531.8  166.59  5534.9  166.56  5541.8  166.49
  5551.8  166.79  5576.1  166.63  5581.8  166.59  5591.8  165.99  5611.8  165.69
  5621.8  165.89  5626.1  165.67  5631.8  165.39  5636.1  165.35  5641.8  165.29
  5646.1  165.68  5650.6  166.08  5651.8  166.19  5661.8  165.99    5662  165.89
BR U #Mann= 5
  4267.1      .2  4359.2     .08  4942.5    .035  5054.2     .12  5534.9      .2
BR D #Sta/Elev= 125
  4267.1  166.66  4275.5  167.86  4287.1  167.71  4305.5  167.46  4307.1  167.38
  4315.5  166.96  4327.1  167.05  4337.1  167.12  4347.1   167.2  4355.5  167.26
  4359.2  167.19  4367.1  167.03  4395.5  166.46  4405.5  165.96  4415.5  165.86
  4435.5  166.06  4445.5  166.36  4447.1  166.36  4455.5  166.36  4457.1  166.29
  4475.5  165.46  4477.1  165.36  4485.5  164.86  4487.1  164.88  4495.5  164.96
  4497.1  165.06  4505.5  165.56  4507.1  165.64  4515.5  166.06  4517.1  165.96
  4525.5  165.46  4537.1  165.23  4545.5  165.06  4547.1   165.1  4557.1  165.33
  4575.5  165.76  4577.1  165.71  4587.1  165.41  4595.5  165.16  4597.1  165.16
  4607.1  165.16  4617.1  165.16  4627.1  165.16  4637.1  165.16  4645.5  165.16
  4665.5  164.66  4715.5  164.56  4735.5  163.66  4737.1  163.68  4745.5  163.76
  4748.1  163.94  4757.1  164.03  4787.1  164.31    4794  164.38  4817.1  164.84
  4827.1  165.04  4828.7  165.07  4848.8  165.47  4877.6  166.39  4894.8  166.94
  4931.7   167.1  4942.5  167.15  4951.4  165.75  4951.5  165.74 4951.61  165.72
  4951.7  165.71  4955.3  165.14  4969.3  162.43  4979.9  158.07  4984.7  156.09
  4994.5  152.27  4994.6  152.23  4997.9   151.4  5001.2  151.38  5005.4  151.96
  5005.5  151.98  5017.5  154.82    5025  159.79  5028.4  160.73 5050.19  166.73
  5050.3  166.76  5050.4  166.78  5050.5  166.81  5054.2  167.83  5070.3   167.7
  5118.3  167.33  5119.4  167.32  5161.8  166.51  5166.1  166.47    5207  166.12
  5213.4  166.06    5256  165.66  5266.1  165.79  5271.8  165.86  5286.1  166.09
  5321.8  166.66  5341.8  166.46  5351.8  166.76  5371.8  166.86  5391.8  166.66
  5421.8  166.06  5451.8  164.86  5461.8  164.66  5481.8  166.06  5491.8  166.16
  5506.1  166.88  5521.8  167.66  5531.8  166.56  5534.9  166.53  5541.8  166.46
  5551.8  166.76  5576.1   166.6  5581.8  166.56  5591.8  165.96  5611.8  165.66
  5621.8  165.86  5626.1  165.64  5631.8  165.36  5636.1  165.32  5641.8  165.26
  5646.1  165.65  5650.6  166.05  5651.8  166.16  5661.8  165.96    5662  165.86
BR D #Mann= 5
  4267.1      .2  4359.2     .08  4942.5    .035  5054.2     .12  5534.9      .2
BC Design=,, 0 ,, 0 ,,,,,,

Type RM Length L Ch R = 1 ,10585.0 ,154.3,154.3,154.3
BEGIN DESCRIPTION:
Downstream Section of Bridge/Culvert/Weir
END DESCRIPTION:
XS GIS Cut Line= 3
     3039991.482   13968949.5964    3040809.2735   13968974.7944
    3041385.5347   13968998.2197
#Sta/Elev= 30
  4267.1  166.66  4275.5  167.86  4315.5  166.96  4359.2  167.19  4415.5  165.86
  4455.5  166.36  4485.5  164.86  4515.5  166.06  4545.5  165.06  4575.5  165.76
  4715.5  164.56  4735.5  163.66  4848.8  165.47  4894.8  166.94  4942.5  167.15
  4969.3  162.43  4994.6  152.23  5001.2  151.38  5017.5  154.82    5025  159.79
  5054.2  167.83    5256  165.66  5371.8  166.86  5461.8  164.66  5521.8  167.66
  5534.9  166.53  5581.8  166.56  5641.8  165.26  5651.8  166.16    5662  165.86
#Mann= 5 ,-1 , 0
  4267.1      .2       0  4359.2     .08       0  4942.5     .04       0
  5054.2     .12       0  5534.9      .2       0
#XS Ineff= 2 , 0
       0  4941.1   165.7  5060.2       0   166.2
Permanent Ineff=
       F       F
#Block Obstruct= 2 , 0
       0                    5350       0     166
Bank Sta=4942.5,5054.2
XS Rating Curve= 0
Exp/Cntr=.5,.3

Type RM Length L Ch R = 1 ,10430.7 ,389.25,488.4,393.27
BEGIN DESCRIPTION:
Cross Section XS32
END DESCRIPTION:
XS GIS Cut Line= 2
    3040112.2099   13969106.6083    3041316.0204   13969090.5574
#Sta/Elev= 30
  4316.9   166.3  4336.9   167.4  4366.9   166.2  4456.9   166.6  4476.9   166.2
  4566.9   166.2  4576.9   165.9  4606.9   166.6  4651.5  166.93  4666.9   166.7
    4866  167.55  4907.8  167.32  4977.7  166.14  4988.2  158.12    4997  151.65
  4997.7  151.28  5000.2  150.83  5002.8  151.08    5003  151.64  5027.3  159.11
    5045  162.26  5065.9  165.34  5086.9   166.5  5176.9   167.2  5206.9   167.1
  5256.9   167.5  5326.9   167.6  5366.9   167.2  5406.9   167.6  5520.8   167.2
#Mann= 5 ,-1 , 0
  4316.9     .15       0  4651.5     .12       0  4977.7     .06       0
  5065.9     .07       0  5520.8      .2       0
Bank Sta=4977.7,5065.9
XS Rating Curve= 0
Exp/Cntr=.3,.1

Type RM Length L Ch R = 1 ,9942.3  ,422.97,439.7,390.55
BEGIN DESCRIPTION:
Cross Section XS31
END DESCRIPTION:
XS GIS Cut Line= 2
    3040243.7326   13969484.9975    3041133.8572   13969477.2404
#Sta/Elev= 30
  4550.6   168.1  4557.2  168.43  4580.6   168.5  4590.6   168.2  4600.6   167.5
  4620.6   167.9  4650.6   167.3  4690.6   167.2  4710.6   167.4  4730.6   166.8
  4750.6   166.6  4790.6   166.7  4810.6   166.2  4840.6   166.2    4866  165.78
  4907.8  165.55  4977.7  164.37    4997  149.88  4997.7  149.51  5000.2  149.06
  5002.8  149.31    5003  149.87  5027.3  157.34    5045  160.49  5065.9  163.57
  5075.5  164.08  5085.7  164.62  5210.6     167  5280.6   167.5  5440.8   167.4
#Mann= 7 , 1 , 0
  4550.6      .2       0  4550.6     .09       0  4557.2     .12       0
  4977.7     .07       0  5065.9     .12       0  5075.5     .07       0
  5440.8      .2       0
Bank Sta=4977.7,5065.9
XS Rating Curve= 0
Exp/Cntr=.3,.1

Type RM Length L Ch R = 1 ,9502.6  ,427.35,438.7,370.66
BEGIN DESCRIPTION:
Cross Section J131-00-00-X19
Located At: 2ND DS ZION RD
Cross Section XS30
END DESCRIPTION:
XS GIS Cut Line= 2
    3040261.1861   13969969.8148    3041075.6791   13969806.9162
#Sta/Elev= 28
  4545.2   167.2  4555.2   167.3    4564  167.52  4575.2   167.8  4605.2   167.4
  4615.2   167.5  4625.2   167.8  4665.2   167.7  4705.2   166.8  4805.2   166.5
  4835.2   165.7  4845.2   165.6  4896.4  164.29  4968.7  162.76  4997.1   148.7
  4997.6  148.25  4999.7  148.24    5001  148.48  5002.9  148.69  5054.5  161.84
  5093.5  164.19    5096  164.51  5105.2   165.7  5115.2   165.9  5175.2   166.6
  5225.2   166.6  5305.2   167.6  5375.8   167.8
#Mann= 7 , 1 , 0
  4545.2      .2       0  4545.2     .09       0    4564     .12       0
  4968.7     .07       0  5054.5     .12       0    5096     .07       0
  5375.8      .2       0
Bank Sta=4968.7,5054.5
XS Rating Curve= 0
Exp/Cntr=.3,.1

Type RM Length L Ch R = 1 ,9063.9  ,289.59,283.3,255.85
BEGIN DESCRIPTION:
Cross Section XS29
END DESCRIPTION:
XS GIS Cut Line= 2
    3040441.5381   13970402.2718    3041143.5535   13970101.6851
#Sta/Elev= 30
  4501.7   167.2  4521.7   166.9  4541.7   167.1  4571.7   166.7  4601.7   167.8
  4621.7   167.8  4641.7   168.2  4701.7   166.1  4751.7   166.1  4781.7   167.4
  4791.7   167.5  4831.7   166.5  4851.7   167.3  4871.7   170.2  4881.7   171.2
  4891.7   170.1  4911.7   167.3  4921.7   163.6  4931.7   160.3  4958.6  159.28
  4977.4  157.35  4991.2  148.32  4995.7  147.22  5008.1  146.28  5008.8  148.25
  5019.4  157.64  5047.3  164.24  5067.7  164.75  5129.2   166.3  5265.4   167.4
#Mann= 6 , 1 , 0
  4501.7      .2       0  4501.7     .12       0  4977.4     .07       0
  5019.4     .12       0  5067.7     .07       0  5265.4      .2       0
Bank Sta=4977.4,5019.4
XS Rating Curve= 0
Exp/Cntr=.3,.1

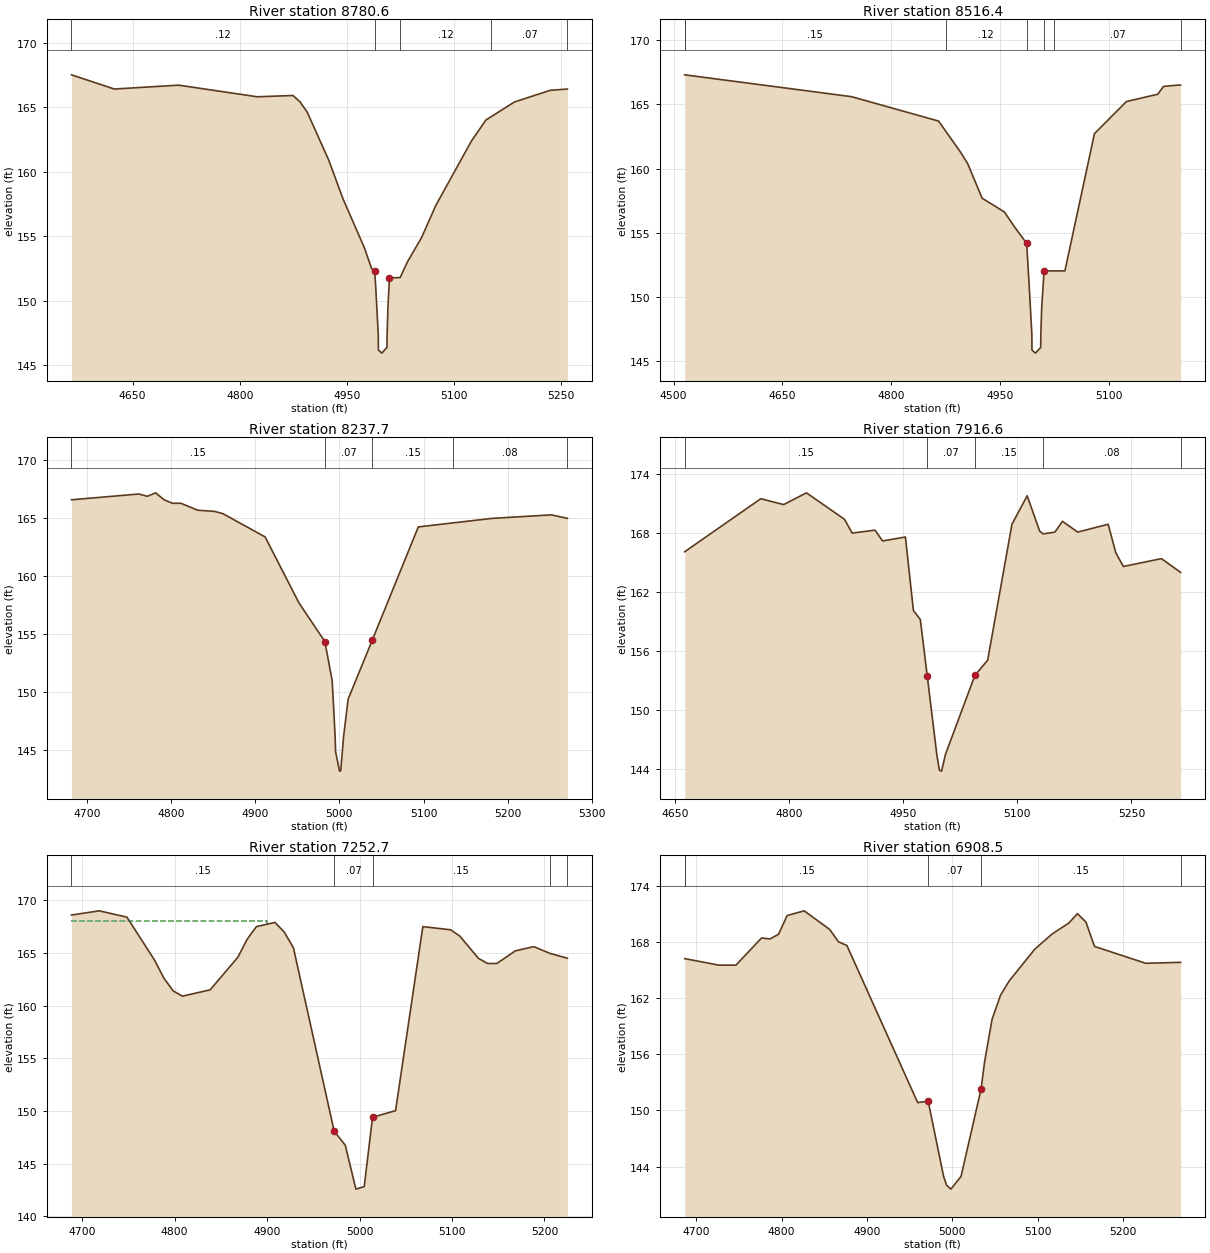
Type RM Length L Ch R = 1 ,8780.6  ,240.25,264.2,227.76
BEGIN DESCRIPTION:
Cross Section XS28
END DESCRIPTION:
XS GIS Cut Line= 2
    3040619.9508   13970697.0407    3041205.6101    13970324.701
#Sta/Elev= 30
  4564.5   167.5  4624.5   166.4  4714.5   166.7  4824.5   165.8  4874.5   165.9
  4884.5   165.4  4894.5   164.6  4924.5   160.9  4944.5   157.9  4974.5   154.1
  4984.5   152.5 4988.84   152.3  4990.2  151.15  4993.8  147.45    4994  146.19
  4998.8  145.95    5006  146.39  5006.2  147.36  5007.4   149.5 5009.52  151.78
  5024.5   151.8  5034.5     153  5054.5   154.9  5074.5   157.4  5124.5   162.4
  5144.5     164  5152.2  164.27  5184.5   165.4  5234.5   166.3  5258.5   166.4
#Mann= 5 ,-1 , 0
  4564.5     .12       0 4988.84     .07       0  5024.5     .12       0
  5152.2     .07       0  5258.5      .2       0
Bank Sta=4988.84,5009.52
XS Rating Curve= 0
Exp/Cntr=.3,.1

Type RM Length L Ch R = 1 ,8516.4  ,209.1,278.7,282.61
BEGIN DESCRIPTION:
Cross Section XS27
END DESCRIPTION:
XS GIS Cut Line= 2
    3040842.9668   13970863.8179    3041380.1444   13970441.0572
#Sta/Elev= 26
  4515.3   167.3  4745.3   165.6  4865.3   163.7  4874.9  162.93  4895.3   161.3
  4905.3   160.4  4925.3   157.7  4955.9  156.63  4970.9  155.39  4986.7  154.18
  4990.2  150.84  4993.8  147.14    4994  145.88  4998.8  145.64    5006  146.08
  5006.2  147.05  5007.4  149.19  5010.7  152.04  5024.6  152.04  5039.4  152.04
  5080.1  162.72  5124.2  165.22  5167.4  165.79  5175.3   166.4  5195.3   166.5
  5198.9   166.5
#Mann= 7 , 1 , 0
  4515.3      .2       0  4515.3     .15       0  4874.9     .12       0
  4986.7     .07       0  5010.7     .12       0  5024.6     .07       0
  5198.9      .2       0
Bank Sta=4986.7,5010.7
XS Rating Curve= 0
Exp/Cntr=.3,.1

Type RM Length L Ch R = 1 ,8237.7  ,328.7,321.1,304.94
BEGIN DESCRIPTION:
Cross Section XS26
END DESCRIPTION:
XS GIS Cut Line= 2
    3040970.9586   13970941.3886    3041512.0147   13970708.6763
#Sta/Elev= 26
  4681.8   166.6  4761.8   167.1  4771.8   166.9  4781.8   167.2  4791.8   166.6
  4801.8   166.3  4811.8   166.3  4831.8   165.7  4851.8   165.6  4861.8   165.4
  4911.8   163.4  4951.8  157.74  4982.8  154.38  4991.5  150.98    4995  146.13
  4995.5  144.89  5000.2  143.22  5001.6  143.25    5005   146.2  5010.4  149.42
  5039.2  154.53  5093.7  164.26    5135  164.61  5181.8     165  5251.8   165.3
  5270.8     165
#Mann= 5 ,-1 , 0
  4681.8     .15       0  4982.8     .07       0  5039.2     .15       0
    5135     .08       0  5270.8      .2       0
Bank Sta=4982.8,5039.2
XS Rating Curve= 0
Exp/Cntr=.3,.1

Type RM Length L Ch R = 1 ,7916.6  ,353.81,663.9,518.35
BEGIN DESCRIPTION:
Cross Section XS25
END DESCRIPTION:
XS GIS Cut Line= 3
    3041133.8572   13971236.1575    3041539.1644   13971005.3845
     3041572.132   13970823.0932
#Sta/Elev= 30
    4663   166.1    4763   171.5    4793   170.9    4823   172.1    4873   169.4
    4883     168    4913   168.3    4923   167.2    4953   167.6  4963.5  160.12
  4972.6   159.2 4981.71  153.44  4994.3  145.43  4997.7  143.85  5000.5  143.76
  5005.6  145.46  5044.3  153.51  5061.1  155.06    5093   168.9    5113   171.8
  5129.4   168.2    5134  167.92  5149.4   168.1  5159.4   169.2  5179.4   168.1
  5219.4   168.9  5229.4     166  5239.4   164.6  5289.4   165.4  5314.6     164
#Mann= 5 ,-1 , 0
    4663     .15       0 4981.71     .07       0  5044.3     .15       0
    5134     .08       0  5314.6      .2       0
Bank Sta=4981.71,5044.3
XS Rating Curve= 0
Exp/Cntr=.3,.1

Type RM Length L Ch R = 1 ,7252.7  ,353.35,344.2,331.04
BEGIN DESCRIPTION:
Cross Section J131-00-00-X14
Located At: 6TH US UP RR
Cross Section XS24
END DESCRIPTION:
XS GIS Cut Line= 2
    3041259.9097   13971430.0845    3041793.2087   13971373.8457
#Sta/Elev= 30
  4688.5   168.6  4718.5     169  4748.5   168.4  4778.5   164.3  4788.5   162.6
  4798.5   161.4  4808.5   160.9  4838.5   161.5  4868.5   164.6  4878.5   166.3
  4888.5   167.5  4908.5   167.9  4918.5     167  4928.5   165.5  4972.6  148.08
  4984.6  146.75  4996.1  142.58  5005.1  142.82  5014.1   149.4    5039  150.03
  5068.5   167.5  5098.5   167.2  5108.5   166.6  5128.5   164.5  5138.5     164
  5148.5     164  5168.5   165.2  5188.5   165.6  5205.9  164.96  5224.8   164.5
#Mann= 5 ,-1 , 0
  4688.5     .15       0  4972.6     .07       0  5014.1     .15       0
  5205.9     .08       0  5224.8      .2       0
#XS Ineff= 2 , 0
       0    4900     168               0
Permanent Ineff=
       F       F
Bank Sta=4972.6,5014.1
XS Rating Curve= 0
Exp/Cntr=.3,.1

Type RM Length L Ch R = 1 ,6908.5  ,374.23,348.7,307.65
BEGIN DESCRIPTION:
Cross Section J131-00-00-X13
Located At: 5TH US UP RR
Cross Section XS23
END DESCRIPTION:
XS GIS Cut Line= 2
    3041242.4563   13971806.3027    3041806.7836   13971668.6146
#Sta/Elev= 30
  4686.5   166.2  4726.5   165.5  4746.5   165.5  4776.5   168.4  4786.5   168.3
  4796.5   168.8  4806.5   170.8  4826.5   171.3  4856.5   169.3  4866.5     168
  4876.5   167.6  4959.4  150.83  4971.7  150.98  4989.8  142.94  4993.2  142.02
  4998.3  141.59  5010.2  142.95  5033.7  152.28  5037.7  155.13  5046.5   159.7
  5056.5   162.3  5066.5   163.8  5096.5   167.2  5116.5   168.8  5136.5     170
  5146.5     171  5156.5   170.1  5166.5   167.5  5226.5   165.7  5267.4   165.8
#Mann= 5 , 1 , 0
  4686.5      .2       0  4686.5     .15       0  4971.7     .07       0
  5033.7     .15       0  5267.4      .2       0
Bank Sta=4971.7,5033.7
XS Rating Curve= 0
Exp/Cntr=.3,.1

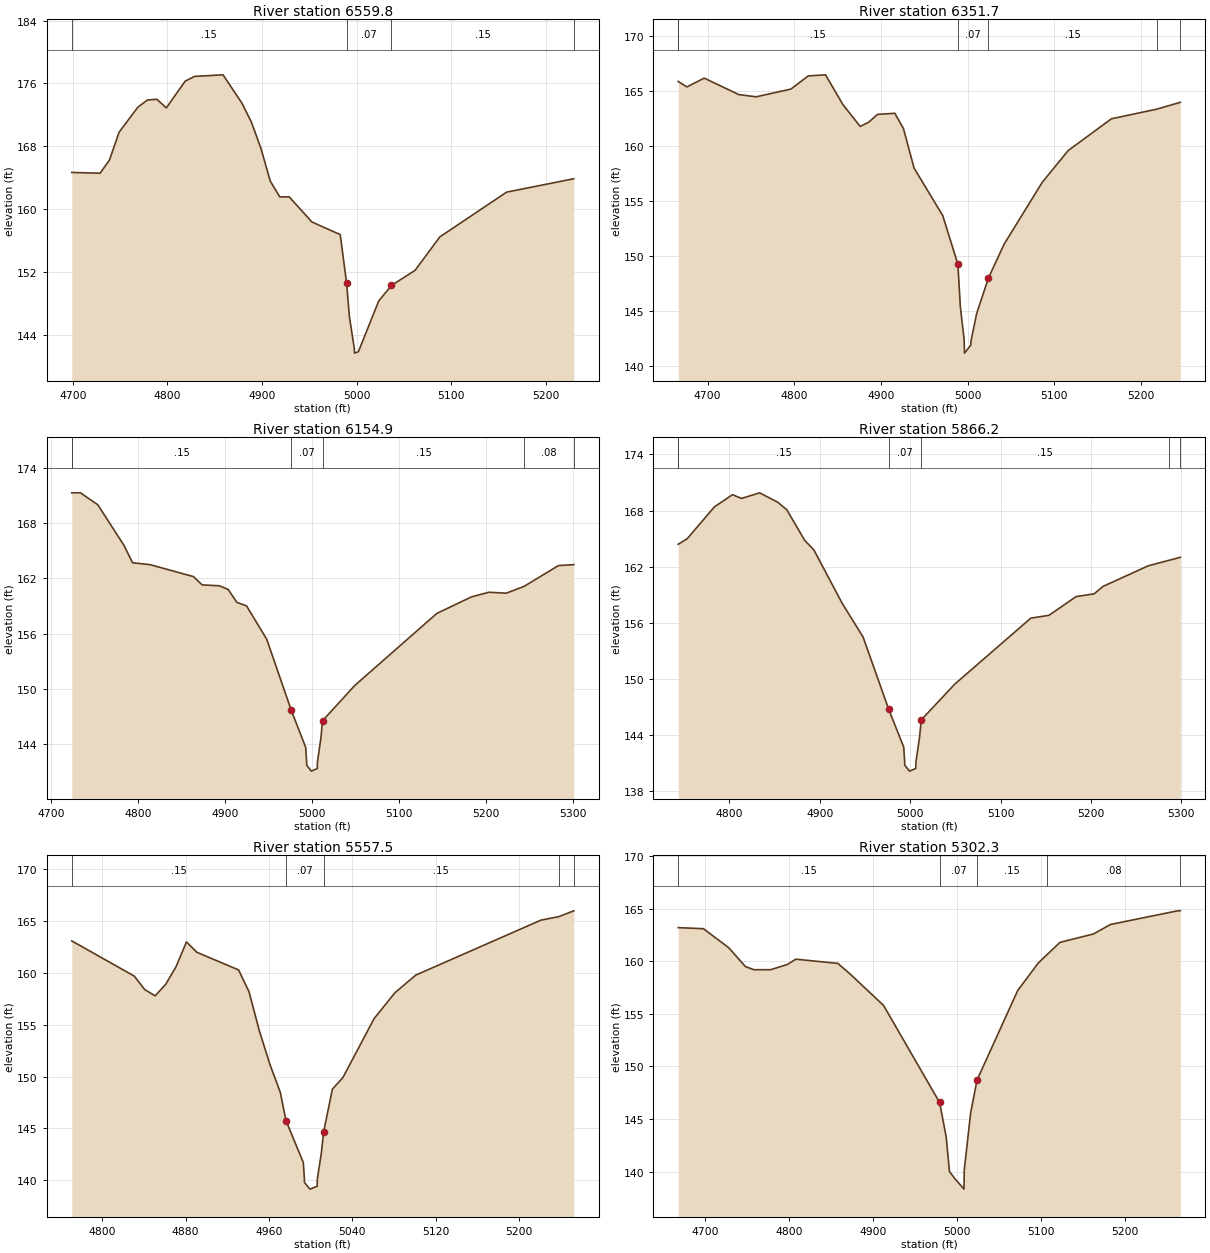
Type RM Length L Ch R = 1 ,6559.8  ,205.14,208.1,196.85
BEGIN DESCRIPTION:
Cross Section XS22
END DESCRIPTION:
XS GIS Cut Line= 2
     3041442.201   13972205.7921     3041874.658   13971897.4483
#Sta/Elev= 30
  4698.8   164.7  4728.8   164.6  4738.8   166.3  4748.8   169.8  4768.8     173
  4778.8   173.9  4788.8     174  4798.8   172.9  4818.8   176.3  4828.8   176.9
  4858.8   177.1  4878.8   173.5  4888.8   171.1  4898.8   167.8  4908.8   163.6
  4918.8   161.6  4928.8   161.6  4952.8  158.41  4982.8   156.8 4989.52  150.65
  4992.5  146.37  4997.7  142.31  4997.9  141.75    5002  141.93  5023.5  148.37
    5037  150.35  5061.9  152.26  5088.1  156.51  5158.8   162.2  5229.9   163.9
#Mann= 4 ,-1 , 0
  4698.8     .15       0 4989.52     .07       0    5037     .15       0
  5229.9      .2       0
Bank Sta=4989.52,5037
XS Rating Curve= 0
Exp/Cntr=.3,.1

Type RM Length L Ch R = 1 ,6351.7  ,243.92,196.8,136.31
BEGIN DESCRIPTION:
Cross Section XS21
END DESCRIPTION:
XS GIS Cut Line= 2
    3041579.8891   13972393.9012    3042010.4068   13972006.0474
#Sta/Elev= 30
  4666.1   165.9  4676.1   165.4  4696.1   166.2  4736.1   164.7  4756.1   164.5
  4796.1   165.2  4816.1   166.4  4836.1   166.5  4856.1   163.8  4876.1   161.8
  4886.1   162.2  4896.1   162.9  4916.1     163  4926.1   161.6  4938.3  158.01
  4971.4  153.69  4988.9  149.25  4991.7  145.41  4996.1  142.39  4996.5  141.17
  5003.8   141.9    5004  142.27  5010.6  144.79  5024.2  148.02  5042.2  151.08
  5086.1   156.7  5116.1   159.6  5166.1   162.5  5218.7  163.38  5245.6     164
#Mann= 6 , 1 , 0
  4666.1      .2       0  4666.1     .15       0  4988.9     .07       0
  5024.2     .15       0  5218.7     .08       0  5245.6      .2       0
Bank Sta=4988.9,5024.2
XS Rating Curve= 0
Exp/Cntr=.3,.1

Type RM Length L Ch R = 1 ,6154.9  ,328.42,288.7,219.83
BEGIN DESCRIPTION:
Cross Section XS20
END DESCRIPTION:
XS GIS Cut Line= 2
    3041884.3543   13972560.6784    3042064.7064   13972011.8652
#Sta/Elev= 30
  4723.7   171.3  4733.7   171.3  4753.7     170  4783.7   165.6  4793.7   163.7
  4813.7   163.5  4863.7   162.2  4873.7   161.3  4893.7   161.2  4903.7   160.8
  4913.7   159.4  4924.8  159.02    4948   155.4  4976.3  147.67  4992.9  143.64
  4993.9  142.12    4994  141.71  4999.3  141.07  5006.2  141.35  5006.3     142
  5010.3  144.62  5012.3  146.55  5049.3  150.37  5143.7   158.2  5183.7     160
  5203.7   160.5  5223.7   160.4  5244.4  161.15  5283.7   163.4  5301.4   163.5
#Mann= 6 , 1 , 0
  4723.7      .2       0  4723.7     .15       0  4976.3     .07       0
  5012.3     .15       0  5244.4     .08       0  5301.4      .2       0
Bank Sta=4976.3,5012.3
XS Rating Curve= 0
Exp/Cntr=.3,.1

Type RM Length L Ch R = 1 ,5866.2  ,285.06,308.7,310.81
BEGIN DESCRIPTION:
Cross Section XS19
END DESCRIPTION:
XS GIS Cut Line= 2
    3042303.2365   13972562.6177    3042186.8803   13972019.6223
#Sta/Elev= 30
  4743.5   164.4  4753.5     165  4783.5   168.4  4803.5   169.7  4813.5   169.3
  4833.5   169.9  4853.5   168.9  4863.5   168.1  4883.5   164.8  4893.5   163.8
  4924.8  158.09    4948  154.47  4976.3  146.74  4992.9  142.71  4993.9  141.19
    4994  140.78  4999.3  140.14  5006.2  140.42  5006.3  141.07  5010.3  143.69
  5012.3  145.62  5049.3  149.44  5133.5   156.5  5153.5   156.8  5183.5   158.8
  5203.5   159.1  5213.5   159.9  5263.5   162.1  5286.1  162.68  5298.8     163
#Mann= 6 , 1 , 0
  4743.5      .2       0  4743.5     .15       0  4976.3     .07       0
  5012.3     .15       0  5286.1     .08       0  5298.8      .2       0
Bank Sta=4976.3,5012.3
XS Rating Curve= 0
Exp/Cntr=.3,.1

Type RM Length L Ch R = 1 ,5557.5  ,149.01,255.2,291.86
BEGIN DESCRIPTION:
Cross Section XS18
END DESCRIPTION:
XS GIS Cut Line= 2
    3042539.8273    13972421.051    3042514.6168   13971940.1122
#Sta/Elev= 30
  4770.8   163.1  4830.8   159.7  4840.8   158.4  4850.8   157.8  4860.8   158.9
  4870.8   160.6  4880.8     163  4890.8     162  4930.8   160.3  4940.8   158.2
  4950.8   154.4  4960.8   151.2  4970.8   148.5  4976.3  145.75  4992.9  141.72
  4993.9   140.2    4994  139.79  4999.3  139.15  5006.2  139.43  5006.3  140.08
  5010.3   142.7  5012.3  144.63  5020.8   148.8  5030.8   149.9  5060.8   155.6
  5080.8   158.1  5100.8   159.8  5220.8   165.1    5238  165.44  5252.4     166
#Mann= 5 ,-1 , 0
  4770.8     .15       0  4976.3     .07       0  5012.3     .15       0
    5238     .08       0  5252.4      .2       0
Bank Sta=4976.3,5012.3
XS Rating Curve= 0
Exp/Cntr=.3,.1

Type RM Length L Ch R = 1 ,5302.3  ,42.18,131.4,150.16
BEGIN DESCRIPTION:
Cross Section XS17
END DESCRIPTION:
XS GIS Cut Line= 3
    3042555.3415   13972409.4154    3042706.6045   13972271.7273
    3042917.9848   13971940.1122
#Sta/Elev= 28
  4668.4   163.2  4698.4   163.1  4728.4   161.3  4748.4   159.5  4758.4   159.2
  4778.4   159.2  4798.4   159.7  4808.4   160.2  4858.4   159.8  4872.9   158.8
  4912.9   155.8  4979.6  146.57  4987.4  143.33  4991.2  140.13  4991.3  140.02
    4998   139.3  5008.7  138.33  5008.9  140.11  5016.6   145.6  5024.2  148.71
  5072.6  157.22  5097.1  159.84  5107.6  160.64  5122.9   161.8  5162.9   162.6
  5182.9   163.5  5262.9   164.8  5266.2   164.8
#Mann= 5 ,-1 , 0
  4668.4     .15       0  4979.6     .07       0  5024.2     .15       0
  5107.6     .08       0  5266.2      .2       0
Bank Sta=4979.6,5024.2
XS Rating Curve= 0
Exp/Cntr=.5,.3

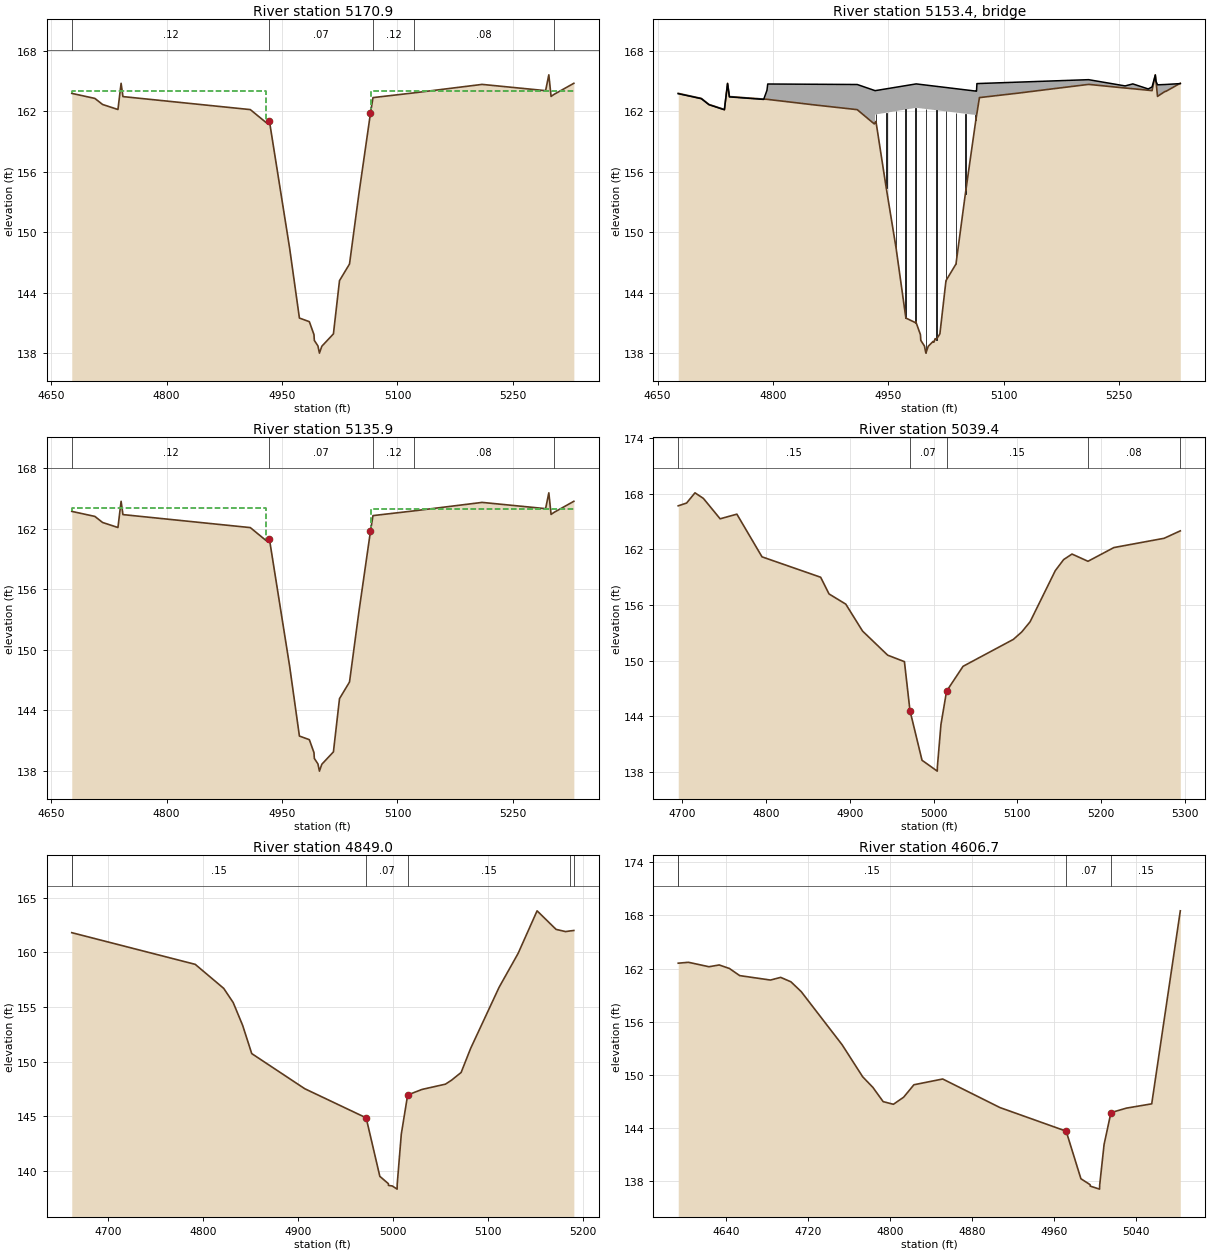
Type RM Length L Ch R = 1 ,5170.9  ,35,35,35
BEGIN DESCRIPTION:
Upstream Section of Bridge/Culvert/Weir
END DESCRIPTION:
XS GIS Cut Line= 2
    3042574.2827   13972408.3474    3043131.7439   13972069.4849
#Sta/Elev= 30
  4676.8  163.76  4706.8  163.26  4716.8  162.66  4736.8  162.16  4740.9  164.76
  4743.3  163.44  4908.8  162.15  4931.5  160.73  4933.7  160.98  4959.9   148.4
  4972.6  141.47  4985.5  141.11  4991.5  139.83    4992  139.25  4996.7   138.7
  4998.6  137.99  5001.7  138.67  5016.8   139.9  5024.7  145.18  5037.7  146.83
  5049.8  153.74  5064.9  161.77  5068.2  163.34  5121.5  163.81    5210  164.65
  5292.5  164.03  5296.7   165.6  5299.6  163.46  5303.7  163.67  5329.2  164.76
#Mann= 5 ,-1 , 0
  4676.8     .12       0  4933.7     .07       0  5068.2     .12       0
  5121.5     .08       0  5303.7      .2       0
#XS Ineff= 2 , 0
       0 4929.03  164.03    5065       0  163.98
Permanent Ineff=
       F       F
Bank Sta=4933.7,5064.9
XS Rating Curve= 0
Exp/Cntr=.5,.3

Type RM Length L Ch R = 3 ,5153.4  ,,,
BEGIN DESCRIPTION:
UNION PACIFIC RAILROAD
Structure ID: J131-00-00-02
END DESCRIPTION:
Bridge Culvert--1,0,-1,-1, 0
Deck Dist Width WeirC Skew NumUp NumDn MinLoCord MaxHiCord MaxSubmerge Is_Ogee
10,15,2.6,0, 30, 30, , , .95, 0, 1,1,,
  4676.8  4706.8  4716.8  4736.8  4740.9  4743.3  4787.8  4792.1  4793.1  4909.4
  4931.5 4932.61  4932.7    4986 5064.16 5064.38 5064.49  5064.6  5064.9  5068.2
    5210  5257.5  5267.5  5287.5  5292.5  5296.7  5297.5  5299.6  5309.6  5329.2
  163.73  163.23  162.63  162.13  164.73  163.41  163.16  164.07  164.69  164.64
  164.06  164.03  164.03   164.7  163.98  163.98  164.14   164.3  164.73  164.74
  165.12   164.5   164.7   164.2   164.4  165.57  164.98  164.61  164.64  164.73
  163.73  163.23  162.63  162.13  164.73  163.41  163.16  163.14  163.13  162.11
   160.7  160.83  161.66  162.33  161.61  161.61  161.77   161.6  161.74  163.31
  164.62  164.26  164.19  164.04     164  165.57  164.98  163.43  163.93  164.73
  4676.8  4706.8  4716.8  4736.8  4740.9  4743.3  4787.8  4792.1  4793.1  4909.4
  4931.5 4932.61  4932.7    4986 5064.16 5064.38 5064.49  5064.6  5064.9  5068.2
    5210  5257.5  5267.5  5287.5  5292.5  5296.7  5297.5  5299.6  5309.6  5329.2
  163.73  163.23  162.63  162.13  164.73  163.41  163.16  164.07  164.69  164.64
  164.06  164.03  164.03   164.7  163.98  163.98  164.14   164.3  164.73  164.74
  165.12   164.5   164.7   164.2   164.4  165.57  164.98  164.61  164.64  164.73
  163.73  163.23  162.63  162.13  164.73  163.41  163.16  163.14  163.13  162.11
   160.7  160.83  161.66  162.33  161.61  161.61  161.77   161.6  161.74  163.31
  164.62  164.26  164.19  164.04     164  165.57  164.98  163.43  163.93  164.73
Pier Skew, UpSta & Num, DnSta & Num=  ,4933.8, 2 ,4933.8, 2 , 0 , 0 , 0 ,,
       1       1
  159.66  162.67
       1       1
  159.66  162.67
Pier Skew, UpSta & Num, DnSta & Num=  ,4947, 2 ,4947, 2 , 0 , 0 , 0 ,,
       1       1
  153.16  162.84
       1       1
  153.16  162.84
Pier Skew, UpSta & Num, DnSta & Num=  ,4959.9, 2 ,4959.9, 2 , 0 , 0 , 0 ,,
       1       1
   147.1  163.01
       1       1
   147.1  163.01
Pier Skew, UpSta & Num, DnSta & Num=  ,4972.6, 2 ,4972.6, 2 , 0 , 0 , 0 ,,
       1       1
  140.42  163.17
       1       1
  140.42  163.17
Pier Skew, UpSta & Num, DnSta & Num=  ,4985.4, 2 ,4985.4, 2 , 0 , 0 , 0 ,,
       1       1
  139.99  163.33
       1       1
  139.99  163.33
Pier Skew, UpSta & Num, DnSta & Num=  ,4998.6, 2 ,4998.6, 2 , 0 , 0 , 0 ,,
       1       1
  137.07  163.22
       1       1
  137.07  163.22
Pier Skew, UpSta & Num, DnSta & Num=  ,5012, 2 ,5012, 2 , 0 , 0 , 0 ,,
       1       1
  138.34  163.09
       1       1
  138.34  163.09
Pier Skew, UpSta & Num, DnSta & Num=  ,5024.7, 2 ,5024.7, 2 , 0 , 0 , 0 ,,
       1       1
  143.82  162.98
       1       1
  143.82  162.98
Pier Skew, UpSta & Num, DnSta & Num=  ,5037.7, 2 ,5037.7, 2 , 0 , 0 , 0 ,,
       1       1
  145.74  162.85
       1       1
  145.74  162.85
Pier Skew, UpSta & Num, DnSta & Num=  ,5049.8, 2 ,5049.8, 2 , 0 , 0 , 0 ,,
       1       1
  152.42  162.74
       1       1
  152.42  162.74
Pier Skew, UpSta & Num, DnSta & Num=  ,5063.5, 2 ,5063.5, 2 , 0 , 0 , 0 ,,
       1       1
  159.81  162.62
       1       1
  159.81  162.62
Abutment Skew #Up #Dn= , 2 , 2
  4932.5  4992.1
  161.66  139.21
  4932.5  4992.1
  161.66  139.21
Abutment Skew #Up #Dn= , 2 , 2
  5007.9 5064.69
  139.12  161.77
  5007.9 5064.69
  139.12  161.77
BR Coef= 1 , 1 , 1 ,1.25, 0 ,,,.8,0,2,0,
WSPro=,,,, 1 ,,,, 0 ,,,, 0 ,,,,-1 ,-1 ,-1 , 0 , 0 , 0 , 0 , 0
BR U #Sta/Elev= 74
  4676.8  163.76  4697.8  163.41  4706.8  163.26  4707.8   163.2  4716.8  162.66
  4736.8  162.16  4740.9  164.76  4743.3  163.44  4747.8  163.42  4757.8  163.36
  4767.8   163.3  4777.8  163.25  4787.8  163.19  4792.1  163.17  4793.1  163.16
  4848.7  162.66  4849.5  162.65  4908.8  162.15  4909.4  162.14  4931.5  160.73
  4932.5  160.84 4932.61  160.86  4932.7  160.87  4933.7  160.98 4933.79  160.94
  4933.9  160.88 4934.01  160.83    4947  154.42  4959.9   148.4  4972.6  141.47
  4985.4     141  4985.5  141.11    4986     141  4991.5  139.83    4992  139.25
  4992.1  139.24  4996.7   138.7  4998.6  137.99  5001.7  138.67  5007.8  139.14
  5007.9  139.15    5009  139.08  5010.7  139.43    5012  139.33  5016.8   139.9
  5024.7  145.18  5037.7  146.83  5049.8  153.74  5063.5  161.11 5064.16  161.42
 5064.27  161.48 5064.38  161.53 5064.49  161.58  5064.6  161.63  5064.9  161.77
  5068.2  163.34  5121.5  163.81  5126.9  163.86  5128.6  163.88    5210  164.65
  5210.2  164.65  5237.5  164.44  5257.5  164.29  5267.5  164.22  5287.5  164.07
  5292.5  164.03  5296.7   165.6  5297.5  165.01  5299.6  163.46  5303.7  163.67
  5309.6  163.96  5310.5  163.96  5327.5  164.69  5329.2  164.76
BR U #Mann= 5
  4676.8     .12  4933.7     .06  5064.9     .12  5121.5     .08  5303.7      .2
BR D #Sta/Elev= 74
  4676.8  163.74  4697.8  163.39  4706.8  163.24  4707.8  163.18  4716.8  162.64
  4736.8  162.14  4740.9  164.74  4743.3  163.42  4747.8   163.4  4757.8  163.34
  4767.8  163.28  4777.8  163.23  4787.8  163.17  4792.1  163.15  4793.1  163.14
  4848.7  162.64  4849.5  162.63  4908.8  162.13  4909.4  162.12  4931.5  160.71
  4932.5  160.82 4932.61  160.84  4932.7  160.85  4933.7  160.96 4933.79  160.92
  4933.9  160.86 4934.01  160.81    4947   154.4  4959.9  148.38  4972.6  141.45
  4985.4  140.98  4985.5  141.09    4986  140.98  4991.5  139.81    4992  139.23
  4992.1  139.22  4996.7  138.68  4998.6  137.97  5001.7  138.65  5007.8  139.12
  5007.9  139.13    5009  139.06  5010.7  139.41    5012  139.31  5016.8  139.88
  5024.7  145.16  5037.7  146.81  5049.8  153.72  5063.5  161.09 5064.16   161.4
 5064.27  161.46 5064.38  161.51 5064.49  161.56  5064.6  161.61  5064.9  161.75
  5068.2  163.32  5121.5  163.79  5126.9  163.84  5128.6  163.86    5210  164.63
  5210.2  164.63  5237.5  164.42  5257.5  164.27  5267.5   164.2  5287.5  164.05
  5292.5  164.01  5296.7  165.58  5297.5  164.99  5299.6  163.44  5303.7  163.65
  5309.6  163.94  5310.5  163.94  5327.5  164.67  5329.2  164.74
BR D #Mann= 5
  4676.8     .12  4933.7     .06  5064.9     .12  5121.5     .08  5303.7      .2
BC Design=,, 0 ,, 0 ,,,,,,

Type RM Length L Ch R = 1 ,5135.9  ,96.5,96.5,96.5
BEGIN DESCRIPTION:
Downstream Section of Bridge/Culvert/Weir
END DESCRIPTION:
XS GIS Cut Line= 2
    3042575.6923    13972439.582    3043133.1807   13972100.6772
#Sta/Elev= 30
  4676.8  163.74  4706.8  163.24  4716.8  162.64  4736.8  162.14  4740.9  164.74
  4743.3  163.42  4908.8  162.13  4931.5  160.71  4933.7  160.96  4959.9  148.38
  4972.6  141.45  4985.5  141.09  4991.5  139.81    4992  139.23  4996.7  138.68
  4998.6  137.97  5001.7  138.65  5016.8  139.88  5024.7  145.16  5037.7  146.81
  5049.8  153.72  5064.9  161.75  5068.2  163.32  5121.5  163.79    5210  164.63
  5292.5  164.01  5296.7  165.58  5299.6  163.44  5303.7  163.65  5329.2  164.74
#Mann= 5 ,-1 , 0
  4676.8     .12       0  4933.7     .07       0  5068.2     .12       0
  5121.5     .08       0  5303.7      .2       0
#XS Ineff= 2 , 0
       0 4929.03  164.03    5065       0  163.98
Permanent Ineff=
       F       F
Bank Sta=4933.7,5064.9
XS Rating Curve= 0
Exp/Cntr=.5,.3

Type RM Length L Ch R = 1 ,5039.4  ,180.71,190.4,176.31
BEGIN DESCRIPTION:
Cross Section XS16
END DESCRIPTION:
XS GIS Cut Line= 2
    3042654.2442   13972519.9537    3043146.8186   13972178.6424
#Sta/Elev= 30
  4695.3   166.7  4705.3     167  4715.3   168.1  4725.3   167.5  4745.3   165.3
  4765.3   165.8  4795.3   161.2  4865.3     159  4875.3   157.2  4895.3   156.1
  4915.3   153.2  4945.3   150.6  4965.3   149.9  4971.9  144.63  4986.3  139.27
  5004.5   138.1  5004.6  138.54  5008.9  143.13  5015.6  146.72  5035.3   149.4
  5095.3   152.3  5105.3   153.1  5115.3   154.2  5145.3   159.7  5155.3   160.9
  5165.3   161.5  5184.4  160.72  5215.3   162.2  5275.3   163.2  5294.6     164
#Mann= 5 ,-1 , 0
  4695.3     .15       0  4971.9     .07       0  5015.6     .15       0
  5184.4     .08       0  5294.6      .2       0
Bank Sta=4971.9,5015.6
XS Rating Curve= 0
Exp/Cntr=.3,.1

Type RM Length L Ch R = 1 ,4849.0  ,193.5,242.3,248.86
BEGIN DESCRIPTION:
Cross Section XS15
END DESCRIPTION:
XS GIS Cut Line= 2
    3042768.6611    13972644.067    3043208.8752   13972351.2373
#Sta/Elev= 29
  4661.9   161.8  4791.9   158.9  4821.9   156.7  4831.9   155.4  4841.9   153.3
  4851.4  150.73  4907.3  147.51  4971.8  144.85  4971.9  144.85  4986.3  139.49
  4995.3  138.82  4995.4  138.66  4999.4  138.61  5004.5  138.32  5004.6  138.76
  5008.9  143.35  5015.6  146.94  5030.8  147.45  5055.4  147.93  5061.9   148.3
  5071.9     149  5081.9   151.2  5111.9   156.8  5131.9   159.9  5151.9   163.8
  5171.9   162.1  5181.9   161.9  5186.7  161.96  5190.6     162
#Mann= 6 , 1 , 0
  4661.9      .2       0  4661.9     .15       0  4971.8     .07       0
  5015.6     .15       0  5186.7     .08       0  5190.6      .2       0
Bank Sta=4971.8,5015.6
XS Rating Curve= 0
Exp/Cntr=.3,.1

Type RM Length L Ch R = 1 ,4606.7  ,462.42,449.3,301.67
BEGIN DESCRIPTION:
Cross Section XS14
END DESCRIPTION:
XS GIS Cut Line= 2
    3042791.9323    13972752.666    3043260.2507   13972610.9145
#Sta/Elev= 30
  4593.3   162.6  4603.3   162.7  4623.3   162.2  4633.3   162.4  4643.3     162
  4653.3   161.2  4683.3   160.7  4693.3     161  4703.3   160.5  4713.3   159.4
  4753.3   153.4  4773.3   149.8  4783.3   148.6  4793.3     147  4803.3   146.7
  4813.3   147.5  4823.3   148.9  4851.4  149.55  4907.3  146.33  4971.9  143.67
  4986.3  138.31  4995.3  137.64  4995.4  137.48  5004.5  137.14  5004.6  137.58
  5008.9  142.17  5015.6  145.76  5030.8  146.27  5055.4  146.75  5083.3   168.5
#Mann= 4 , 1 , 0
  4593.3      .2       0  4593.3     .15       0  4971.9     .07       0
  5015.6     .15       0
Bank Sta=4971.9,5015.6
XS Rating Curve= 0
Exp/Cntr=.3,.1