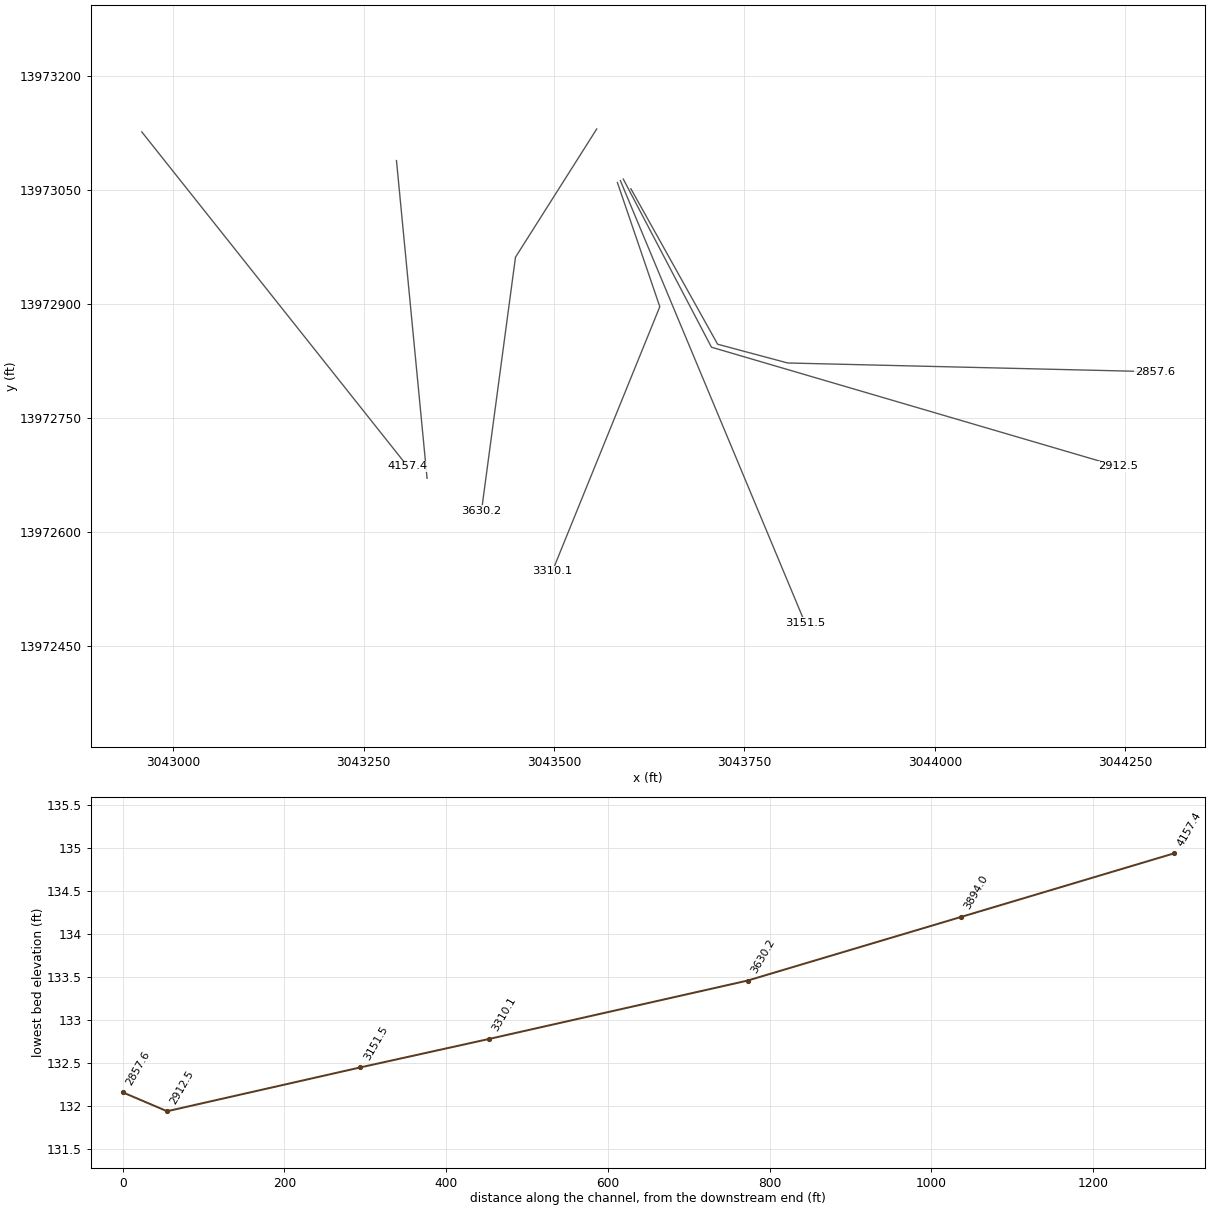
HEC-RAS study J131-00-00.PRJ: J131-00-00

--- J131-00-00.g01 (geometry) --- (continued)

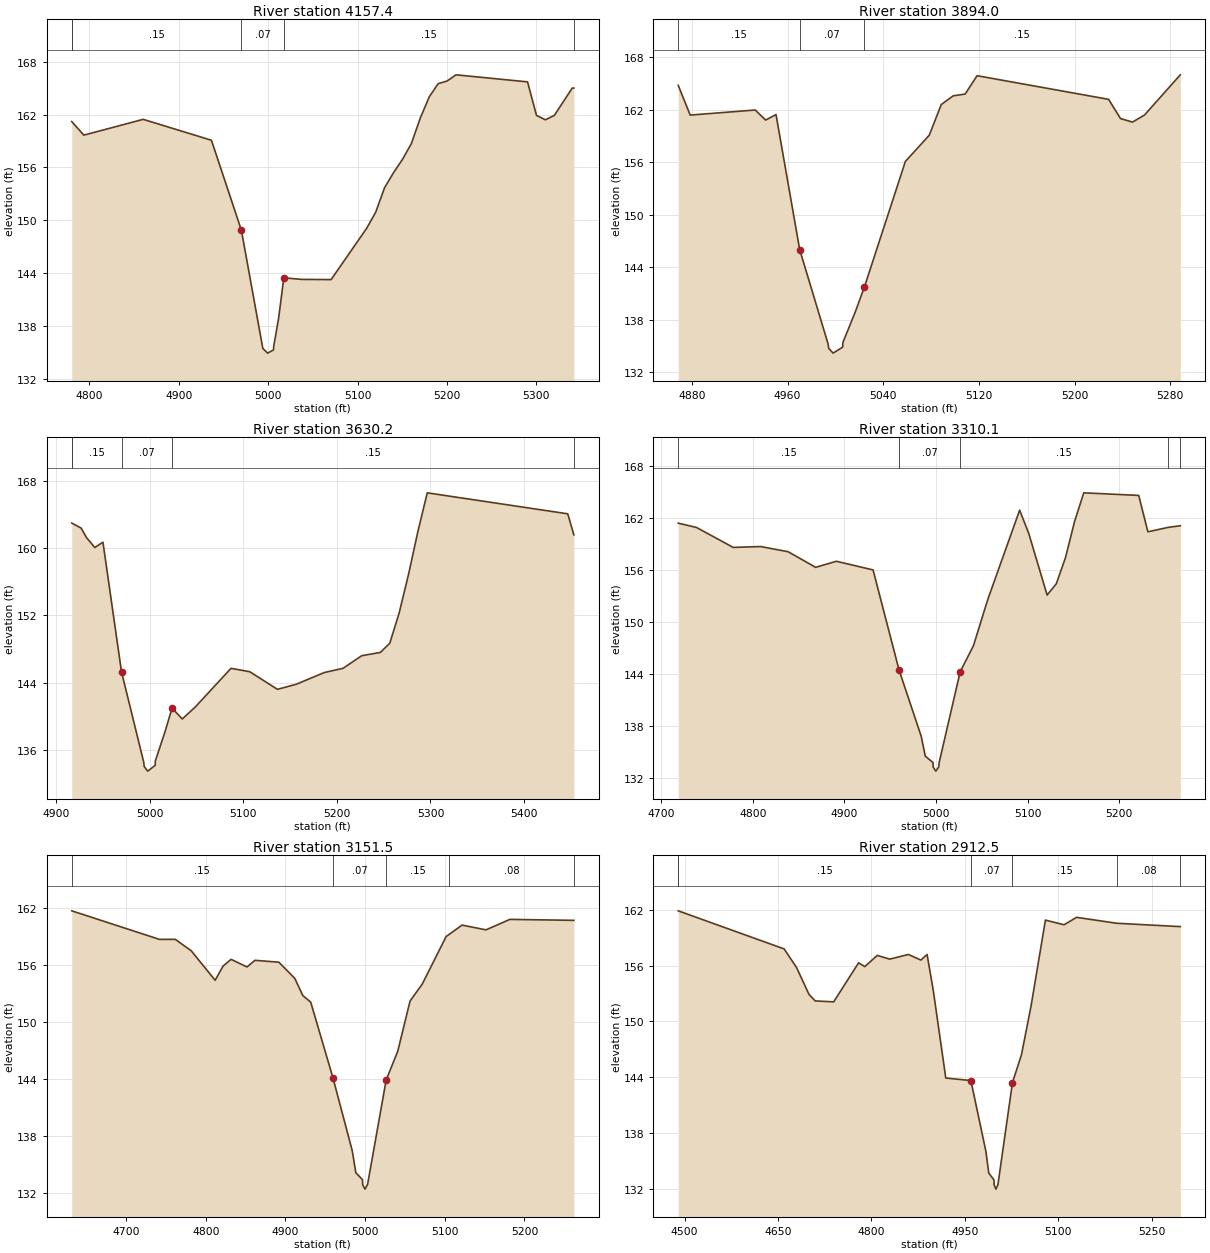
Type RM Length L Ch R = 1 ,4157.4  ,276.34,263.4,141.2
BEGIN DESCRIPTION:
Cross Section XS13
END DESCRIPTION:
XS GIS Cut Line= 2
    3042958.7095    13973126.945    3043307.7779   13972686.7309
#Sta/Elev= 30
  4780.2   161.2  4793.7  159.66  4860.1  161.45  4936.5  159.08    4970  148.87
    4994  135.47  4999.3  134.94  5005.9   135.3  5006.2  135.73  5011.6  138.86
  5017.5  143.48  5037.5   143.3  5070.4  143.28  5110.2   149.1  5120.2   150.9
  5130.2   153.7  5140.2   155.4  5150.2   156.9  5160.2   158.7  5170.2   161.6
  5180.2     164  5190.2   165.5  5200.2   165.8  5210.2   166.5  5290.2   165.7
  5300.2   161.9  5310.2   161.4  5320.2   161.9  5340.2     165    5342     165
#Mann= 5 , 1 , 0
  4780.2      .2       0  4780.2     .15       0    4970     .07       0
  5017.5     .15       0    5342      .2       0
Bank Sta=4970,5017.5
XS Rating Curve= 0
Exp/Cntr=.3,.1

Type RM Length L Ch R = 1 ,3894.0  ,269.81,263.8,134.38
BEGIN DESCRIPTION:
Cross Section XS12
END DESCRIPTION:
XS GIS Cut Line= 2
    3043293.0815   13973089.2731    3043333.2538   13972671.1846
#Sta/Elev= 24
  4868.5   164.8  4878.5   161.4  4932.9  161.98  4941.6  160.83  4950.3  161.46
  4970.1  146.03  4993.8  135.28  4994.4  134.74  4998.1   134.2  5006.1  134.89
  5006.2   135.4  5016.5  138.87  5024.1   141.7  5058.5   156.1  5078.5   159.1
  5088.5   162.6  5098.5   163.6  5108.5   163.8  5118.5   165.9  5228.5   163.2
  5238.5     161  5248.5   160.6  5258.5   161.4  5288.5     166
#Mann= 3 ,-1 , 0
  4868.5     .15       0  4970.1     .07       0  5024.1     .15       0
Bank Sta=4970.1,5024.1
XS Rating Curve= 0
Exp/Cntr=.3,.1

Type RM Length L Ch R = 1 ,3630.2  ,255.25,320.1,186.76
BEGIN DESCRIPTION:
Cross Section XS11
END DESCRIPTION:
XS GIS Cut Line= 3
    3043556.0044   13973130.8235    3043449.3446   13972962.1071
    3043404.7414   13972628.5528
#Sta/Elev= 30
    4917     163    4927   162.4  4932.9  161.24  4941.6  160.09  4950.3  160.72
  4970.1  145.29  4993.8  134.54  4994.4     134  4998.1  133.46  5006.1  134.15
  5006.2  134.66  5016.5  138.13  5024.1  140.96    5035  139.67    5049  141.11
    5087   145.7    5107   145.3  5136.6   143.2  5156.6   143.8  5186.6   145.2
  5206.6   145.7  5226.6   147.2  5246.6   147.6  5256.6   148.7  5266.6   152.3
  5276.6   156.9  5286.6     162  5296.6   166.6  5446.6   164.1  5453.1   161.6
#Mann= 5 , 1 , 0
    4917      .2       0    4917     .15       0  4970.1     .07       0
  5024.1     .15       0  5453.1      .2       0
Bank Sta=4970.1,5024.1
XS Rating Curve= 0
Exp/Cntr=.3,.1

Type RM Length L Ch R = 1 ,3310.1  ,84.25,158.6,191.9
BEGIN DESCRIPTION:
Cross Section XS10
END DESCRIPTION:
XS GIS Cut Line= 3
    3043583.1343   13973060.4453    3043638.8369   13972896.9703
    3043497.8263   13972549.0428
#Sta/Elev= 30
  4718.6   161.4  4738.6   160.9  4778.6   158.6  4808.6   158.7  4838.6   158.1
  4868.6   156.3  4891.3     157  4931.3     156  4959.6  144.47  4983.8  136.82
  4988.3  134.51  4996.7  133.77  4996.9  133.25  4999.8  132.78  5003.1  133.28
  5003.3   133.7  5026.4  144.25  5040.9  147.26  5056.4  152.55  5091.3   162.9
  5101.3   160.2  5121.3   153.1  5131.3   154.4  5141.3   157.4  5151.3   161.6
  5161.3   164.9  5221.3   164.6  5231.3   160.4  5253.8  160.92  5266.7   161.1
#Mann= 5 ,-1 , 0
  4718.6     .15       0  4959.6     .07       0  5026.4     .15       0
  5253.8     .08       0  5266.7      .2       0
Bank Sta=4959.6,5026.4
XS Rating Curve= 0
Exp/Cntr=.3,.1

Type RM Length L Ch R = 1 ,3151.5  ,123.76,239,288.02
BEGIN DESCRIPTION:
Cross Section XS09
END DESCRIPTION:
XS GIS Cut Line= 2
    3043587.0327   13973062.9491    3043829.4413   13972481.1683
#Sta/Elev= 30
  4631.7   161.7  4741.7   158.7  4761.7   158.7  4781.7   157.5  4811.7   154.4
  4821.7   155.9  4831.7   156.6  4851.7   155.8  4861.7   156.5  4891.7   156.3
  4911.7   154.6  4921.7   152.8  4931.7   152.1  4959.6  144.14  4983.8  136.49
  4988.3  134.18  4996.7  133.44  4996.9  132.92  4999.8  132.45  5003.1  132.95
  5026.4  143.92  5040.9  146.93  5056.4  152.22  5071.7     154  5101.7     159
  5105.7  159.24  5121.7   160.2  5151.7   159.7  5181.7   160.8    5262   160.7
#Mann= 5 ,-1 , 0
  4631.7     .15       0  4959.6     .07       0  5026.4     .15       0
  5105.7     .08       0    5262      .2       0
Bank Sta=4959.6,5026.4
XS Rating Curve= 0
Exp/Cntr=.3,.1

Type RM Length L Ch R = 1 ,2912.5  ,39.81,54.9,87.52
BEGIN DESCRIPTION:
Cross Section XS08
END DESCRIPTION:
XS GIS Cut Line= 3
    3043590.9112   13973064.8884    3043706.6488   13972843.6896
    3044240.5664   13972686.7309
#Sta/Elev= 30
  4489.7   161.9  4659.7   157.8  4679.7   155.8  4699.7   152.9  4709.7   152.2
  4739.3   152.1  4779.3   156.3  4789.3   155.9  4809.3   157.1  4829.3   156.7
  4859.3   157.2  4879.3   156.6  4889.3   157.2  4899.3   153.3  4919.3   143.9
  4959.6  143.63  4983.8  135.98  4988.3  133.67  4996.7  132.93  4996.9  132.41
  4999.8  131.94  5003.1  132.44  5026.4  143.41  5040.9  146.42  5056.4  151.71
  5079.3   160.9  5109.3   160.4  5129.3   161.2  5193.9  160.56  5295.9   160.2
#Mann= 6 , 1 , 0
  4489.7      .2       0  4489.7     .15       0  4959.6     .07       0
  5026.4     .15       0  5193.9     .08       0  5295.9      .2       0
Bank Sta=4959.6,5026.4
XS Rating Curve= 0
Exp/Cntr=.5,.3

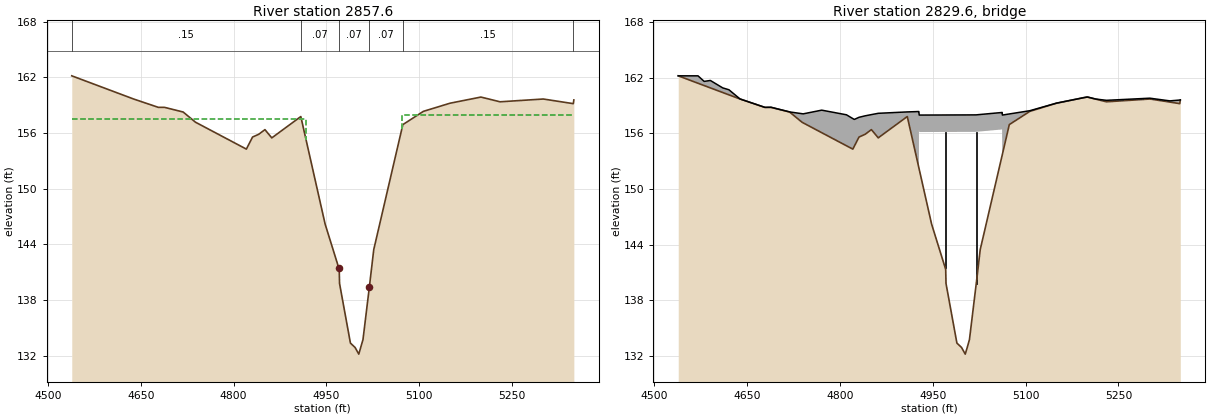
Type RM Length L Ch R = 1 ,2857.6  ,56,56,56
BEGIN DESCRIPTION:
Upstream Section of Bridge/Culvert/Weir
END DESCRIPTION:
XS GIS Cut Line= 4
    3043600.8926   13973052.1503    3043714.7514   13972847.6128
    3043806.7217   13972822.9333    3044288.7269   13972811.4321
#Sta/Elev= 30
  4538.5  162.16  4638.5  159.66  4678.5  158.76  4688.5  158.76  4718.5  158.26
  4738.5  157.16  4820.7  154.26  4830.7  155.56  4840.7  155.86  4850.7  156.36
  4861.8  155.47  4908.7  157.77    4948  146.18  4970.2  141.42  4970.8  141.29
  4971.3  139.78  4988.9  133.35  4996.4  132.88  5002.4  132.16  5009.2  133.73
  5019.6  139.45  5026.6  143.43  5073.6   156.9  5106.8  158.33    5150  159.21
  5199.8  159.87  5230.7  159.36  5300.7  159.66  5349.1  159.16    5350  159.56
#Mann= 6 ,-1 , 0
  4538.5     .15       0  4908.7     .07       0  4970.2     .07       0
  5019.6     .07       0  5073.6     .15       0  5349.1      .2       0
#XS Ineff= 2 , 0
       0  4917.3   157.5    5072       0  157.99
Permanent Ineff=
       F       F
Bank Sta=4970.2,5019.6
XS Rating Curve= 0
Exp/Cntr=.5,.3

Type RM Length L Ch R = 3 ,2829.6  ,,,
BEGIN DESCRIPTION:
LIVE OAK LANE
Structure ID: J131-00-00-01
END DESCRIPTION:
Bridge Culvert--1,0,-1,-1, 0
Deck Dist Width WeirC Skew NumUp NumDn MinLoCord MaxHiCord MaxSubmerge Is_Ogee
10,36,2.6,0, 38, 37, , , .95, 0, 1,1,,
  4538.5  4570.4  4580.4  4590.4  4610.4  4620.4  4638.5  4678.5  4688.5  4718.5
  4740.4  4770.4  4810.4  4820.7  4823.1  4830.7  4840.7  4850.7  4861.8  4908.7
  4927.4 4927.51  4927.6    4928  5019.6 5061.99  5062.1  5062.4  5073.6  5106.8
    5150  5199.8  5213.1  5230.7  5300.7  5333.1  5349.1    5350
   162.2   162.2   161.6   161.7   160.9   160.7   159.7   158.8  158.81  158.31
   158.1   158.5     158  157.59   157.5  157.73  157.89  158.02  158.16  158.31
  158.35  158.28  158.22  157.97  157.99  158.25  158.25  157.97  158.09  158.44
  159.26  159.92   159.7  159.56  159.79   159.5  159.59   159.6
   162.2   161.4  161.15   160.9   160.4  160.15   159.7   158.8   158.8   158.3
  157.13  156.07  154.66   154.3  154.61   155.6   155.9   156.4  155.51  157.81
   152.3  152.26  156.39  156.14  156.16  156.42  153.64  153.73  156.94  158.37
  159.25  159.91  159.69   159.4   159.7  159.37   159.2   159.6
  4538.5  4570.4  4580.4  4590.4  4610.4  4620.4  4638.5  4678.5  4688.5  4718.5
  4738.5  4770.4  4810.4  4820.7  4823.1  4830.7  4840.7  4850.7  4861.8  4908.7
  4927.4 4927.51  4927.6    4928  5019.6 5061.99  5062.1  5062.4  5073.6  5106.8
    5150  5199.8  5230.7  5300.7  5333.1  5349.1    5350
  162.49   162.2   161.6   161.7   160.9   160.7  159.99  159.09  159.09  158.59
   158.1   158.5     158  157.59   157.5  157.73  157.89  158.02  158.16  158.31
  158.35  158.28  158.22  157.97  157.99  158.25  158.25  157.97  158.09  158.66
  159.54   160.2  159.69  159.99  159.66  159.59  159.89
  162.49  161.69  161.44  161.19  160.69  160.44  159.99  159.09  159.09  158.59
  157.49  156.36  154.95  154.59   154.9  155.89  156.19  156.69   155.8   158.1
  152.59  152.55  156.68  156.43  156.45  156.71  153.93  154.02  157.23  158.66
  159.54   160.2  159.69  159.99  159.66  159.49  159.89
Pier Skew, UpSta & Num, DnSta & Num=  ,4970, 2 ,4970, 2 , 0 , 0 , 0 ,,
     1.3     1.3
  140.36  157.17
     1.3     1.3
  140.65  157.46
Pier Skew, UpSta & Num, DnSta & Num=  ,5020.1, 2 ,5020.1, 2 , 0 , 0 , 0 ,,
     1.3     1.3
  138.41  157.17
     1.3     1.3
   138.7  157.46
Abutment Skew #Up #Dn= , 2 , 2
  4927.4  4995.1
  156.39     133
  4927.4  4995.1
  156.68  133.29
Abutment Skew #Up #Dn= , 2 , 2
  5004.8 5062.19
  132.74  156.42
  5004.8 5062.19
  133.03  156.71
BR Coef= 1 , 1 , 1 ,1.25, 0 ,,,.8,0,2,0,
WSPro=,,,, 1 ,,,, 0 ,,,, 0 ,,,,-1 ,-1 ,-1 , 0 , 0 , 0 , 0 , 0
BR U #Sta/Elev= 70
  4538.5   162.2  4570.4   161.4  4580.4  161.15  4590.4   160.9  4610.4   160.4
  4620.4  160.15  4638.5   159.7  4640.4  159.66  4660.4  159.21  4670.4  158.98
  4678.5   158.8  4680.4   158.8  4688.5   158.8  4700.4   158.6  4718.5   158.3
  4738.5   157.2  4740.4  157.13  4770.4  156.07  4810.4  154.66  4820.7   154.3
  4823.1  154.61  4830.7   155.6  4833.1  155.67  4840.7   155.9  4850.7   156.4
  4861.8  155.51  4866.8  155.76  4908.7  157.81  4927.4   152.3 4927.51  152.26
  4927.6  152.24    4928  152.12 4928.09  152.09  4928.2  152.06 4928.31  152.03
    4948  146.22  4970.2  141.46  4970.8  141.33  4971.3  139.82  4988.9  133.39
  4995.1     133  4996.4  132.92  5002.4   132.2  5004.8  132.74  5006.1  133.03
  5009.2  133.77  5019.6  139.49  5021.4  140.48  5026.6  143.47 5061.49  153.47
  5061.6   153.5 5061.71  153.53 5061.99  153.61  5062.1  153.64  5062.2  153.67
  5062.4  153.73  5073.6  156.94  5106.8  158.37  5109.3  158.42    5150  159.25
  5153.8   159.3  5194.5  159.86  5199.8  159.91  5213.1  159.69  5230.7   159.4
  5300.7   159.7  5303.1  159.68  5333.1  159.37  5349.1   159.2    5350   159.6
BR U #Mann= 6
  4538.5     .15  4908.7     .07  4970.2     .06  5019.6     .07  5073.6     .15
  5349.1      .2
BR U Banks=4970.2,5019.6
BR D #Sta/Elev= 70
  4538.5  162.49  4570.4  161.69  4580.4  161.44  4590.4  161.19  4610.4  160.69
  4620.4  160.44  4638.5  159.99  4640.4  159.95  4660.4   159.5  4670.4  159.27
  4678.5  159.09  4680.4  159.09  4688.5  159.09  4700.4  158.89  4718.5  158.59
  4738.5  157.49  4740.4  157.42  4770.4  156.36  4810.4  154.95  4820.7  154.59
  4823.1   154.9  4830.7  155.89  4833.1  155.96  4840.7  156.19  4850.7  156.69
  4861.8   155.8  4866.8  156.05  4908.7   158.1  4927.4  152.59 4927.51  152.55
  4927.6  152.53    4928  152.41 4928.09  152.38  4928.2  152.35 4928.31  152.32
    4948  146.51  4970.2  141.75  4970.8  141.62  4971.3  140.11  4988.9  133.68
  4995.1  133.29  4996.4  133.21  5002.4  132.49  5004.8  133.03  5006.1  133.32
  5009.2  134.06  5019.6  139.78  5021.4  140.77  5026.6  143.76 5061.49  153.76
  5061.6  153.79 5061.71  153.82 5061.99   153.9  5062.1  153.93  5062.2  153.96
  5062.4  154.02  5073.6  157.23  5106.8  158.66  5109.3  158.71    5150  159.54
  5153.8  159.59  5194.5  160.15  5199.8   160.2  5213.1  159.98  5230.7  159.69
  5300.7  159.99  5303.1  159.97  5333.1  159.66  5349.1  159.49    5350  159.89
BR D #Mann= 6
  4538.5     .15  4908.7     .07  4970.2     .06  5019.6     .07  5073.6     .15
  5349.1      .2
BR D Banks=4970.2,5019.6
BC Design=,, 0 ,, 0 ,,,,,,