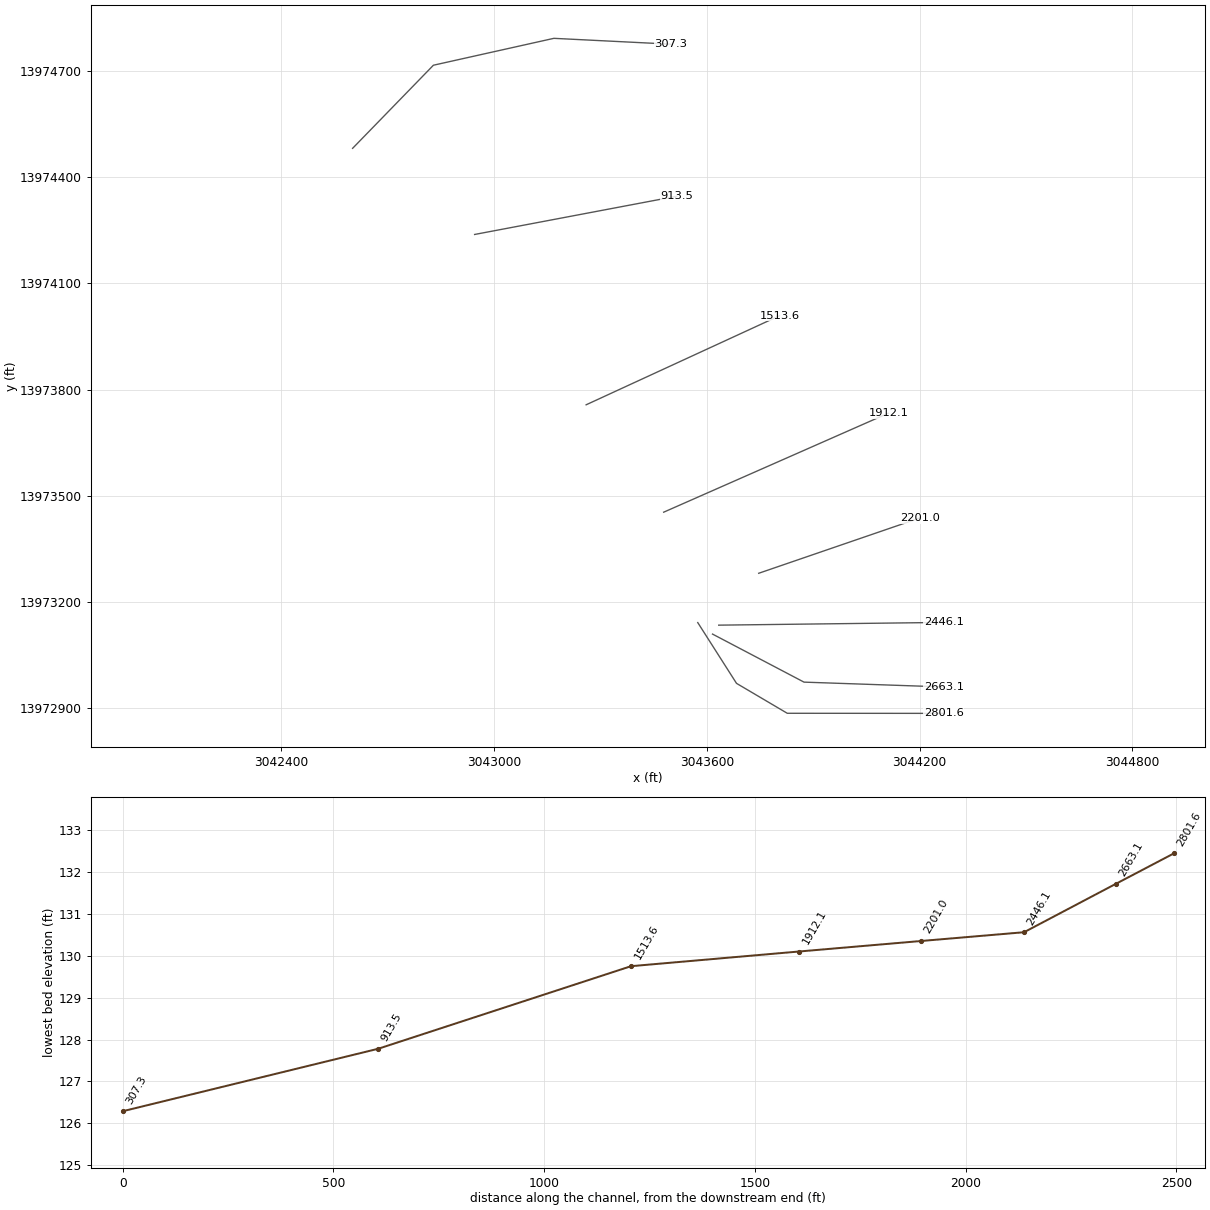
HEC-RAS study J131-00-00.PRJ: J131-00-00

--- J131-00-00.g01 (geometry) --- (continued)

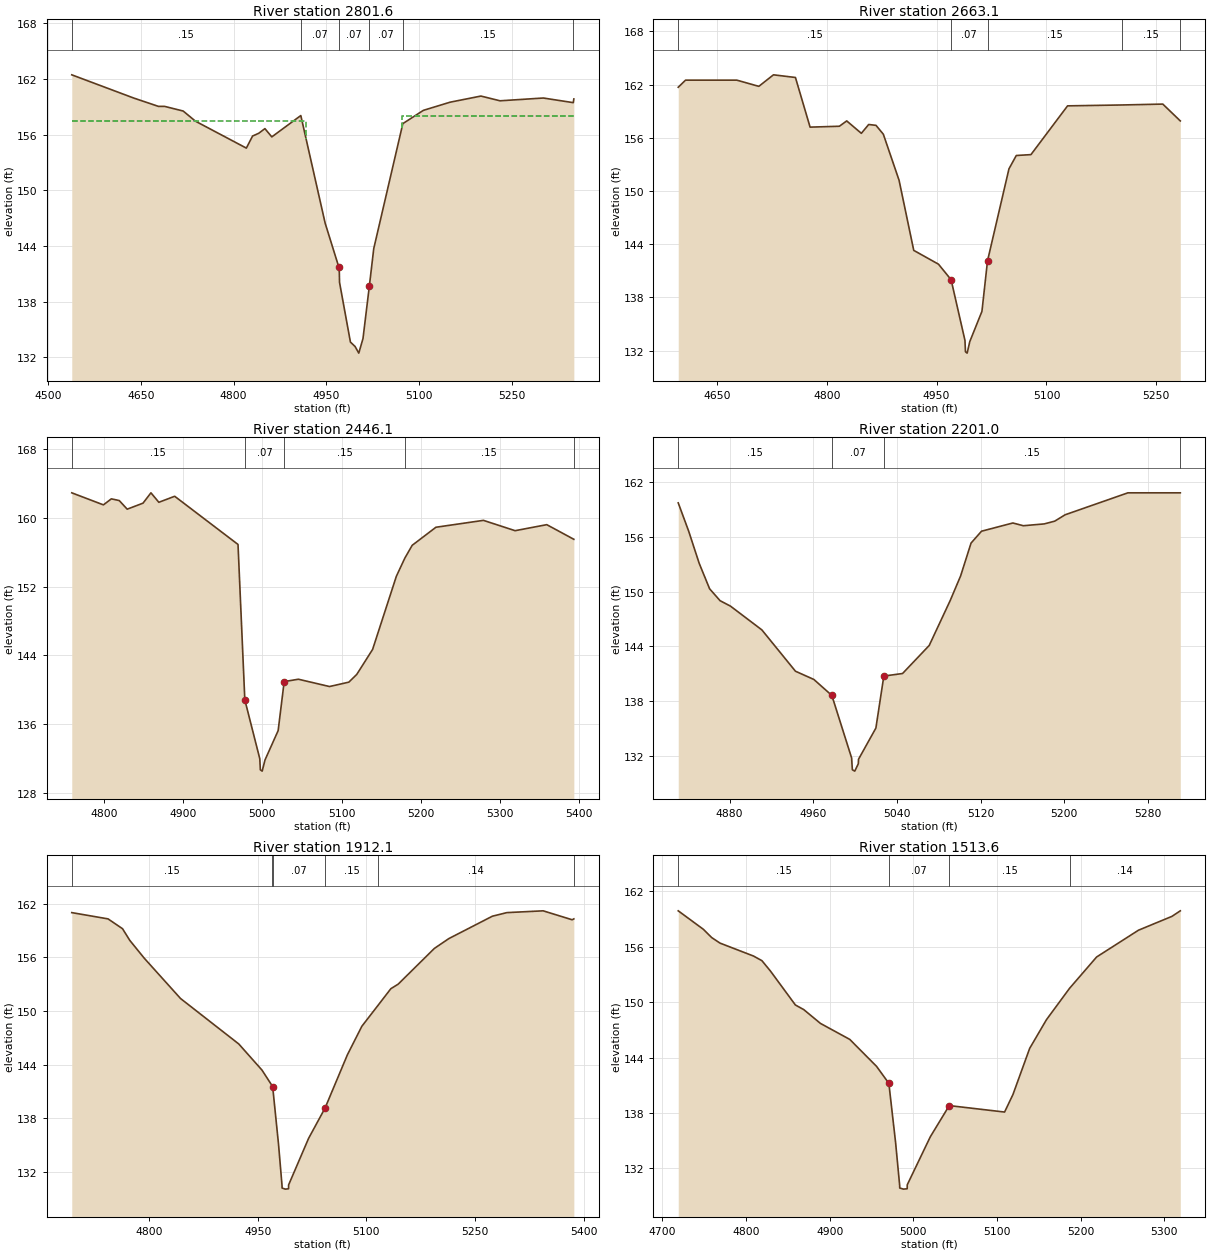
Type RM Length L Ch R = 1 ,2801.6  ,138.5,138.5,138.5
BEGIN DESCRIPTION:
Downstream Section of Bridge/Culvert/Weir
END DESCRIPTION:
XS GIS Cut Line= 4
    3043574.5167   13973141.9476    3043683.7719   13972970.2609
    3043826.8667   13972885.7272    3044268.6501   13972885.4629
#Sta/Elev= 30
  4538.5  162.44  4638.5  159.94  4678.5  159.04  4688.5  159.04  4718.5  158.54
  4738.5  157.44  4820.7  154.54  4830.7  155.84  4840.7  156.14  4850.7  156.64
  4861.8  155.75  4908.7  158.05    4948  146.46  4970.2   141.7  4970.8  141.57
  4971.3  140.06  4988.9  133.63  4996.4  133.16  5002.4  132.44  5009.2  134.01
  5019.6  139.73  5026.6  143.71  5073.6  157.18  5106.8  158.61    5150  159.49
  5199.8  160.15  5230.7  159.64  5300.7  159.94  5349.1  159.44    5350  159.84
#Mann= 6 ,-1 , 0
  4538.5     .15       0  4908.7     .07       0  4970.2     .07       0
  5019.6     .07       0  5073.6     .15       0  5349.1      .2       0
#XS Ineff= 2 , 0
       0  4917.3   157.5    5072       0  157.99
Permanent Ineff=
       F       F
Bank Sta=4970.2,5019.6
XS Rating Curve= 0
Exp/Cntr=.5,.3

Type RM Length L Ch R = 1 ,2663.1  ,145.64,217,176.58
BEGIN DESCRIPTION:
Cross Section XS07
END DESCRIPTION:
XS GIS Cut Line= 3
    3043616.1217   13973109.4916    3043874.0445   13972973.7427
    3044267.7162   13972960.1678
#Sta/Elev= 30
  4597.3   161.7  4607.3   162.5  4677.3   162.5  4707.3   161.8  4727.3   163.1
  4757.3   162.8  4777.3   157.2  4817.3   157.3  4827.3   157.9  4847.3   156.5
  4857.3   157.5  4867.3   157.4  4877.3   156.4  4898.8   151.2  4918.8   143.3
  4952.6  141.74  4969.8  139.99  4988.7  133.15  4989.4  131.86  4991.7  131.71
  4995.3  133.01  5011.9  136.42  5019.5  142.11  5048.8   152.5  5058.8     154
  5078.8   154.1  5128.8   159.6  5203.2   159.7  5258.8   159.8  5282.7   157.9
#Mann= 5 ,-1 , 0
  4597.3     .15       0  4969.8     .07       0  5019.5     .15       0
  5203.2     .15       0  5282.7      .2       0
Bank Sta=4969.8,5019.5
XS Rating Curve= 0
Exp/Cntr=.3,.1

Type RM Length L Ch R = 1 ,2446.1  ,171.97,245.1,217.15
BEGIN DESCRIPTION:
Cross Section XS06
END DESCRIPTION:
XS GIS Cut Line= 2
    3043633.5751   13973134.7021    3044267.7162   13973142.4591
#Sta/Elev= 30
  4759.2   162.9  4799.2   161.5  4809.2   162.2  4819.2     162  4829.2     161
  4849.2   161.7  4859.2   162.9  4869.2   161.8  4889.2   162.5  4969.2   156.9
  4977.8  138.84  4996.7     132  4997.4  130.71  4999.7  130.56  5003.3  131.86
  5019.9  135.27  5027.5  140.96  5045.4  141.24  5084.8  140.39  5109.2   140.9
  5119.2   141.8  5139.2   144.7  5169.2   153.2  5179.9  155.31  5189.2   156.8
  5219.2   158.9  5279.2   159.7  5319.2   158.5  5359.2   159.2  5393.4   157.5
#Mann= 5 ,-1 , 0
  4759.2     .15       0  4977.8     .07       0  5027.5     .15       0
  5179.9     .15       0  5393.4      .2       0
Bank Sta=4977.8,5027.5
XS Rating Curve= 0
Exp/Cntr=.3,.1

Type RM Length L Ch R = 1 ,2201.0  ,277.94,288.9,286.17
BEGIN DESCRIPTION:
Cross Section XS05
END DESCRIPTION:
XS GIS Cut Line= 2
    3043746.2832   13973281.2726    3044199.8417    13973437.228
#Sta/Elev= 30
  4830.9   159.7  4840.9   156.6  4850.9   153.1  4860.9   150.3  4870.9     149
  4880.9   148.4  4910.9   145.8    4943  141.28  4960.6  140.38  4977.8  138.63
  4996.7  131.79  4997.4   130.5  4999.7  130.35  5003.1  131.16  5003.3  131.65
  5019.9  135.06  5027.5  140.75  5045.4  141.03  5070.9   144.1  5090.9     149
  5100.9   151.7  5110.9   155.3  5120.9   156.6  5150.9   157.5  5160.9   157.2
  5180.9   157.4  5190.9   157.7  5200.9   158.4  5260.9   160.8    5311   160.8
#Mann= 4 ,-1 , 0
  4830.9     .15       0  4977.8     .07       0  5027.5     .15       0
    5311      .2       0
Bank Sta=4977.8,5027.5
XS Rating Curve= 0
Exp/Cntr=.3,.1

Type RM Length L Ch R = 1 ,1912.1  ,385.45,398.5,379.26
BEGIN DESCRIPTION:
Cross Section XS04
END DESCRIPTION:
XS GIS Cut Line= 2
    3043478.4596   13973453.8695    3044111.7736   13973733.5147
#Sta/Elev= 30
  4693.7     161  4743.7   160.3  4763.7   159.2  4773.7   157.9  4793.7   155.9
  4843.7   151.4    4924  146.32    4956   143.4  4970.3  141.61  4970.7  141.56
  4978.8  135.11  4983.6  130.52  4983.7  130.22  4988.2   130.1  4992.6  130.14
  4992.7  130.57  5020.3  135.78  5042.9  139.15  5073.7   145.1  5093.7   148.3
  5116.4  150.68  5133.7   152.5  5143.7     153  5193.7     157  5213.7   158.1
  5273.7   160.6  5293.7     161  5343.7   161.2  5383.7   160.2    5386   160.3
#Mann= 6 , 1 , 0
  4693.7     .15       0  4970.3     .15       0  4970.7     .07       0
  5042.9     .15       0  5116.4     .14       0    5386      .2       0
Bank Sta=4970.7,5042.9
XS Rating Curve= 0
Exp/Cntr=.3,.1

Type RM Length L Ch R = 1 ,1513.6  ,540.61,600.1,470.48
BEGIN DESCRIPTION:
Cross Section XS03
END DESCRIPTION:
XS GIS Cut Line= 2
    3043259.8032   13973757.2664    3043804.6998   13974008.7571
#Sta/Elev= 30
    4719   159.9    4749   157.9    4759     157    4769   156.4    4809     155
    4819   154.5    4829   153.4    4859   149.7    4869   149.2    4889   147.7
    4924  145.97    4956  143.05  4970.7  141.21  4978.8  134.76  4983.6  130.17
  4983.7  129.87  4988.2  129.75  4992.6  129.79  4992.7  130.22  5020.3  135.43
  5042.9   138.8    5109   138.1    5119     140    5139     145    5159   148.1
  5186.6   151.5    5219   154.9    5269   157.8    5309   159.3    5319   159.9
#Mann= 4 ,-1 , 0
    4719     .15       0  4970.7     .07       0  5042.9     .15       0
  5186.6     .14       0
Bank Sta=4970.7,5042.9
XS Rating Curve= 0
Exp/Cntr=.3,.1

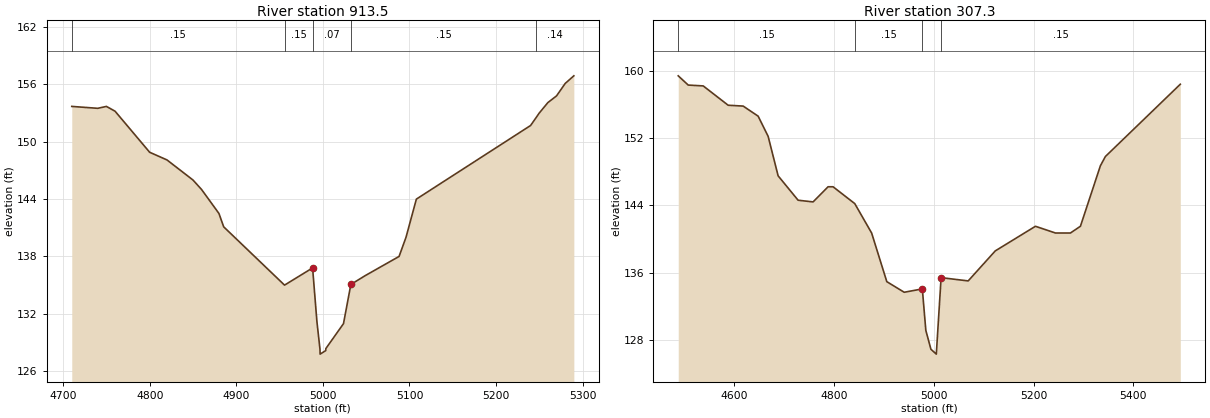
Type RM Length L Ch R = 1 ,913.5   ,505.94,606.2,526.47
BEGIN DESCRIPTION:
Cross Section XS02
END DESCRIPTION:
XS GIS Cut Line= 2
    3042945.4297   13974238.4835    3043515.1345   13974346.5309
#Sta/Elev= 30
  4709.9   153.7  4739.9   153.5  4749.9   153.7  4759.9   153.2  4799.9   148.9
  4819.9   148.1  4849.9     146  4859.9     145  4879.9   142.5  4885.4   141.1
  4955.7     135  4988.1   136.8  4993.1  131.19  4996.6  128.33  4996.8  127.78
  5003.3  128.15  5003.4  128.36  5023.8  130.97  5032.3  135.07    5049     136
    5088     138    5096     140    5108     144  5239.9   151.7  5246.4  152.54
  5249.9     153  5259.9   154.1  5269.9   154.8  5279.9   156.1  5289.9   156.9
#Mann= 5 ,-1 , 0
  4709.9     .15       0  4955.7     .15       0  4988.1     .07       0
  5032.3     .15       0  5246.4     .14       0
Bank Sta=4988.1,5032.3
XS Rating Curve= 0
Exp/Cntr=.3,.1

Type RM Length L Ch R = 1 ,307.3   ,0,0,0
BEGIN DESCRIPTION:
Cross Section XS01
END DESCRIPTION:
XS GIS Cut Line= 4
    3042601.4479   13974481.8364    3042829.2422   13974716.6398
    3043168.8672   13974792.6086    3043498.4785    13974776.128
#Sta/Elev= 30
  4488.7   159.4  4508.7   158.3  4538.7   158.2  4588.7   155.9  4618.7   155.8
  4648.7   154.6  4668.7   152.2  4688.7   147.5  4728.7   144.6  4758.7   144.4
  4788.7   146.2  4798.7   146.2  4842.1   144.2  4875.9   140.7  4906.3  134.91
  4941.1  133.65  4977.4  134.05  4984.4  129.12  4994.6  126.87  5005.4  126.29
    5015  135.39  5069.2     135  5123.4  138.57  5203.9   141.5  5243.9   140.7
  5273.9   140.7  5293.9   141.5  5333.9   148.7  5343.9   149.8  5493.9   158.4
#Mann= 4 , 1 , 0
  4488.7     .15       0  4842.1     .15       0  4977.4     .07       0
    5015     .15       0
Bank Sta=4977.4,5015
XS Rating Curve= 0
Exp/Cntr=.3,.1

Chan Stop Cuts=-1